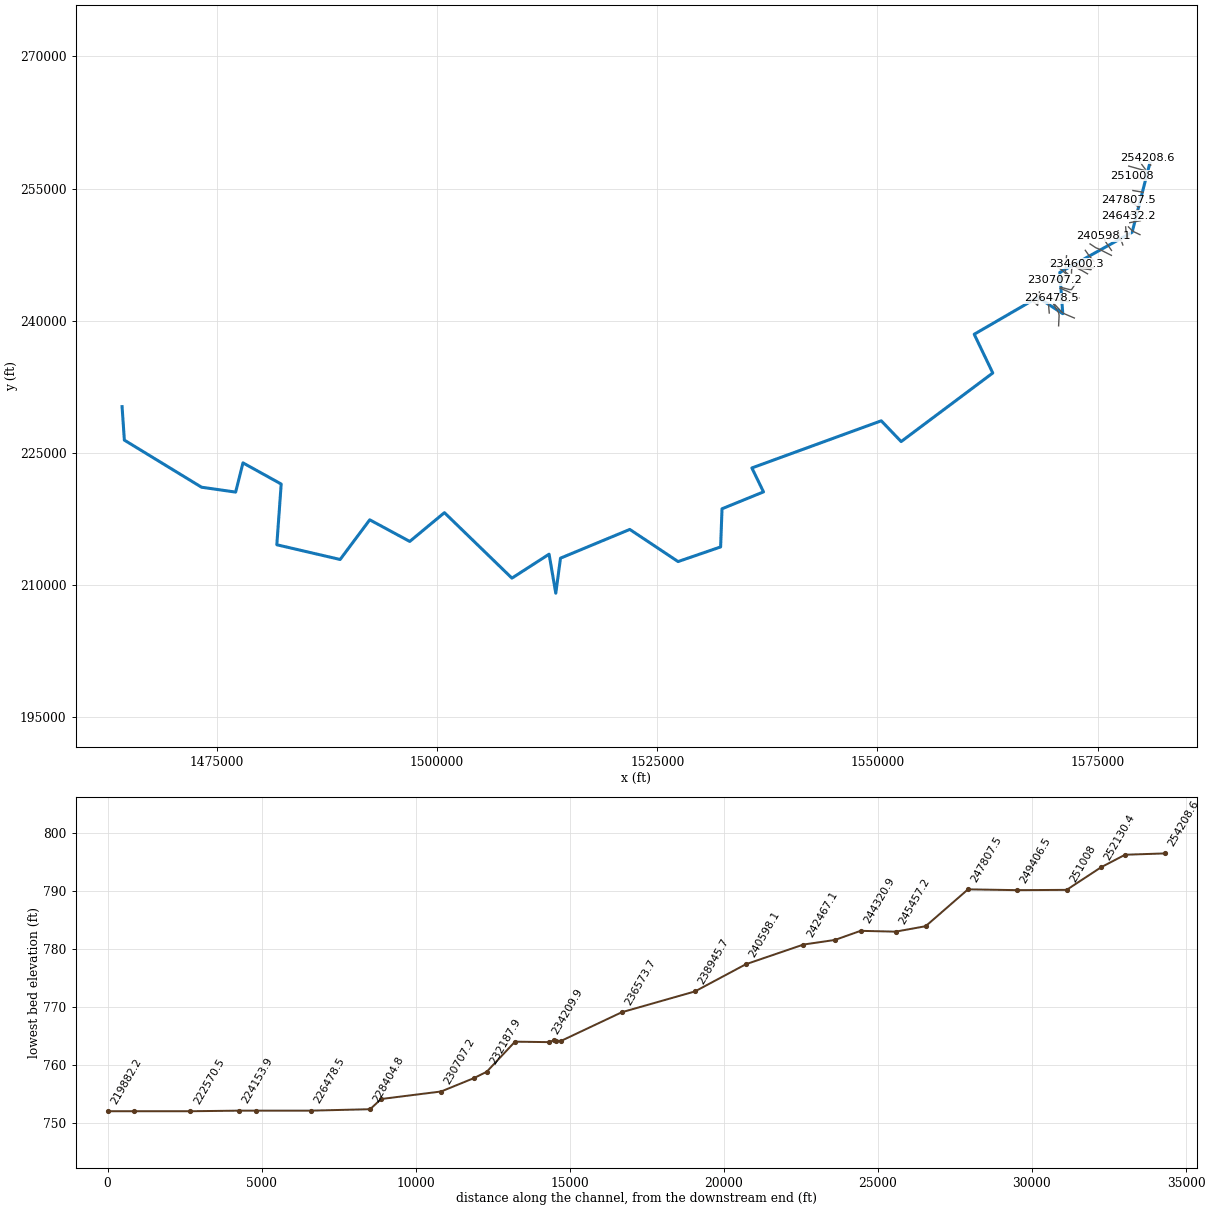
--- SFHGHSRV.prj (project) ---

Proj Title=SFHGHSRV
Current Plan=p01
Default Exp/Contr=0,0
English Units
Geom File=g01
Flow File=f01
Plan File=p01
BEGIN DESCRIPTION:
END DESCRIPTION:
DSS Export Rating Curves= 0
DSS Export Rating Curve Sorted= 0
DSS Export Volume Flow Curves= 0
DXF OffsetX= 0
DXF OffsetY= 0
DXF ScaleX= 0
DXF ScaleY= 0

--- SFHGHSRV.p01 (plan) ---

Plan Title=Floodplain
Program Version=4.00
Geom File=g01
Flow File=f01
K Sum by GR=0
Std Step Tol=0.01
Critical Tol=0.01
Num of Std Step Trials=20
Max Error Tol=0.3
Flow Tol Ratio=0.001
Split Flow NTrial=30
Split Flow Tol=0.02
Split Flow Ratio=0.02
Log Output Level=0
Friction Slope Method=1
Unsteady Friction Slope Method=2
Unsteady Bridges Friction Slope Method=1
Global Log Level=0
CheckData=False
Run HTab=0
Run UNet=0
Run PostProcess=0
UNET Theta=0
UNET Theta Warmup=0
UNET ZTol=0
UNET ZSATol=0
UNET MxIter=0
UNET MaxInSteps=0
UNET DtIC=0
UNET DtMin=0
UNET MaxCRTS=0
UNET WFStab=0
UNET SFStab=0
UNET WFX=0
UNET SFX=0
UNET DSS MLevel=0
UNET DZMax Abort=0
UNET Convert EG Bridges=0
UNET Use Existing IB Tables=0
UNET Froude Limit=0
UNET Froude Power=0
Write IC File=0
Echo Input=False
Echo Output=False
Write Detailed=0

--- SFHGHSRV.f01 (steady flow) ---

Flow Title=NFF Regression Equation
Program Version=4.10
Number of Profiles= 1
Profile Names=P100yr
River Rch & RM=SFHGHSRV,Main            ,254208.6
3607.195
River Rch & RM=SFHGHSRV,Main            ,242467.1
 3874.19
River Rch & RM=SFHGHSRV,Main            ,232187.9
 4129.66
River Rch & RM=SFHGHSRV,Main            ,231772.3
5233.778
River Rch & RM=SFHGHSRV,Main            ,224685.3
5302.683
River Rch & RM=SFHGHSRV,Main            ,224153.9
7942.372
River Rch & RM=SFHGHSRV,Main            ,204684.2
8310.752
River Rch & RM=SFHGHSRV,Main            ,203716.6
8781.642
River Rch & RM=SFHGHSRV,Main            ,188027.9
8994.296
River Rch & RM=SFHGHSRV,Main            ,187328.5
10785.16
River Rch & RM=SFHGHSRV,Main            ,169952.7
10972.95
River Rch & RM=SFHGHSRV,Main            ,169029.8
12136.39
River Rch & RM=SFHGHSRV,Main            ,160288.5
12404.03
River Rch & RM=SFHGHSRV,Main            ,143226.8
12987.89
River Rch & RM=SFHGHSRV,Main            ,141730.4
14867.14
River Rch & RM=SFHGHSRV,Main            ,129115.7
15626.88
River Rch & RM=SFHGHSRV,Main            ,127528.4
15820.71
River Rch & RM=SFHGHSRV,Main            ,107445.4
 16181.4
River Rch & RM=SFHGHSRV,Main            ,106322.5
17487.57
River Rch & RM=SFHGHSRV,Main            ,80621.2
17924.36
River Rch & RM=SFHGHSRV,Main            ,79172
 20253.9
River Rch & RM=SFHGHSRV,Main            ,55487.3
 20453.9
River Rch & RM=SFHGHSRV,Main            ,53390.6
 20784.8
River Rch & RM=SFHGHSRV,Main            ,18941.8
21982.24
River Rch & RM=SFHGHSRV,Main            ,18101.6
22403.44
River Rch & RM=SFHGHSRV,Main            ,7700.9
22895.24
River Rch & RM=SFHGHSRV,Main            ,158.5
23043.71
Boundary for River Rch & Prof#=SFHGHSRV,Main            , 1
Up Type= 0
Dn Type= 1
Dn Known WS=642.98
DSS Import GetInterval= 0
DSS Import GetPeak= 0
DSS Import FillOption= 0

--- SFHGHSRV.g01 (geometry) ---

Geom Title=USGS 10m DEM
Program Version=4.10

River Reach=SFHGHSRV        ,Main
Reach XY= 30
     1580932.886      257891.317     1578917.657      250034.185
     1570707.371      245476.894     1571043.474      240787.721
     1568217.085      242648.832     1560987.918      238452.651
     1563095.557      234056.818     1552691.043      226266.887
     1550432.363      228626.263     1535738.397      223272.288
     1537058.845      220554.349     1532348.464      218634.671
     1532190.096      214303.089     1527357.113      212641.372
     1521875.342      216291.545     1514006.419      213027.657
     1513470.395      209045.452     1512710.846      213479.045
     1508489.925      210759.862     1500824.633      218194.612
     1496887.133      214926.383     1492345.255      217382.704
     1488983.727        212877.9     1481792.755      214549.124
     1482288.455      221446.172     1477949.262      223849.601
      1477115.47      220528.983     1473244.474      221083.817
     1464478.864      226433.087     1464219.451      230234.383

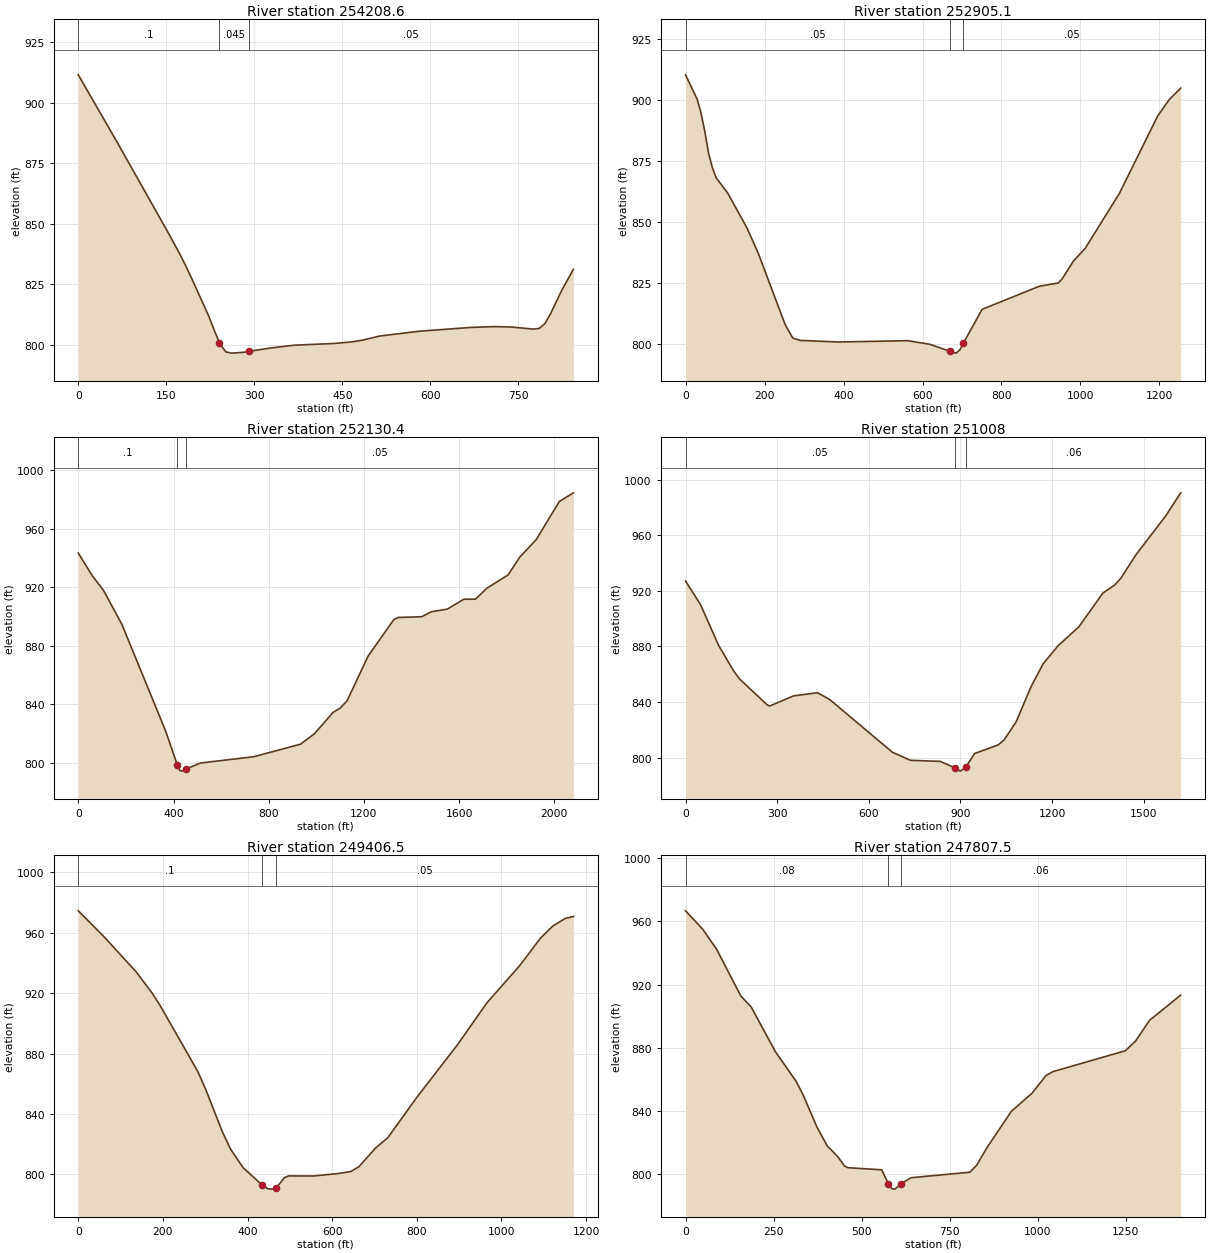
Type RM Length L Ch R = 1 ,254208.6,1300.2,1303.5,1304.3
XS GIS Cut Line= 3
     1581030.584      257658.113      1580931.61      257878.579
      1580659.49      258415.492
#Sta/Elev= 30
       0  911.59    67.7   883.1   154.7  845.67     174  837.06   183.7  832.33
   193.3  827.37   222.3  811.84     232  805.77   240.5800.9153   241.7  800.23
   251.4  797.06   261.1  796.55   280.5  796.86   290.2  797.27     329  798.71
   367.9  799.83   435.8  800.54     465  801.17   484.4  801.92   513.5  803.62
   581.5  805.62   668.8  807.17   707.7  807.51   736.8  807.36   775.6  806.48
   785.4  806.77     795  808.76   804.8   812.9   824.2  822.76   843.6  831.18
#Mann= 3 , 0 , 0
       0      .1       0   240.5    .045       0   290.2     .05       0
Bank Sta=240.5,290.2
XS Rating Curve= 0 ,0
Exp/Cntr=0.3,0.1

Type RM Length L Ch R = 1 ,252905.1,754.8,774.7,793.4
XS GIS Cut Line= 4
      1580411.66      257204.554     1580071.382      257652.471
     1579963.743      257829.554     1579633.882      258183.721
#Sta/Elev= 30
       0  910.29    29.1  900.42    38.8  894.95    48.5  887.39    58.2  878.29
    67.9  872.32    77.6  868.11   106.7  861.88   155.2  847.71   184.3  837.15
   252.2  808.02   271.6  802.47     291  801.52   387.9  800.88   562.5  801.42
     619  799.92   668.4797.1221     685  796.32   694.4   797.6   703.8   800.5
   750.9  814.24   895.6   823.7     944  825.06   953.7  826.74   982.7  834.14
  1011.7  839.16  1098.8   861.8  1195.6  893.47  1224.7  900.11  1253.7  904.84
#Mann= 3 , 0 , 0
       0     .05       0   668.4    .045       0   703.8     .05       0
Bank Sta=668.4,703.8
XS Rating Curve= 0 ,0
Exp/Cntr=0.3,0.1

Type RM Length L Ch R = 1 ,252130.4,1125.6,1122.4,1117.6
XS GIS Cut Line= 4
     1580520.167      256955.422     1580203.327      257098.652
      1579947.25      257155.075      1578532.32      257554.381
#Sta/Elev= 30
       0  943.26      58  927.94   106.2   917.7   183.5  894.38   367.1   821.5
   415.7  798.56   425.4  794.75   435.1  794.17   454.5  795.74   512.8  799.72
   737.4  804.02   933.4  812.58   992.2  819.74  1070.6  834.36    1100  837.17
  1129.4  842.32  1217.6  872.81  1325.4  897.74    1345  899.24    1443  899.73
  1482.2  903.11  1550.8  904.97  1619.5  911.68  1668.5  911.74  1717.5  919.32
  1805.7  928.32  1854.7  940.46  1923.3  952.32  2021.3  978.57  2080.1  984.44
#Mann= 3 , 0 , 0
       0      .1       0   415.7    .045       0   454.5     .05       0
Bank Sta=415.7,454.5
XS Rating Curve= 0 ,0
Exp/Cntr=0.3,0.1

Type RM Length L Ch R = 1 ,251008  ,1594.9,1601.4,1607.7
XS GIS Cut Line= 4
     1580468.084      255965.839     1579676.036      256195.079
     1579539.264      256256.638     1578927.285      256464.971
#Sta/Elev= 30
       0  927.11    49.1  910.09     108  880.82   157.1  862.52   176.7  856.61
     265   838.4   274.8  837.04   353.4  844.38   431.9  846.69   471.2  841.92
   677.3  803.85   736.2  798.04   833.9  797.27   880.8  792.72   899.6  790.25
   918.3  793.38   946.4  802.92  1023.5  809.12  1043.1  812.74  1082.3   825.7
  1131.3  851.07  1170.4  867.36  1219.4  880.44    1288  894.18  1366.3   918.4
  1405.5  924.26  1425.1  929.06  1474.1   945.8    1572   973.9    1621  990.54
#Mann= 3 , 0 , 0
       0     .05       0   880.8    .045       0   918.3     .06       0
Bank Sta=880.8,918.3
XS Rating Curve= 0 ,0
Exp/Cntr=0.3,0.1

Type RM Length L Ch R = 1 ,249406.5,1607.3,1599,1588.9
XS GIS Cut Line= 4
     1580164.264      254585.631     1579799.681      254646.395
     1579634.401      254670.199      1579009.75      254776.603
#Sta/Elev= 30
       0  974.58    58.4  958.14   136.2  934.36   175.1  919.86   194.5  911.34
   282.1   868.3   301.5  856.05   340.4  828.25   359.9  816.69   389.3  804.51
   434.6792.8542   448.2  790.45     458   790.2   467.8  790.98   487.5  797.89
   497.3  798.96   556.1   798.9   614.6  800.56   643.8  801.83   663.3  805.07
   702.3  817.33   731.6   824.3   799.8  850.88   897.3  886.25   965.5  913.53
  1043.5  938.34  1092.3  956.46  1121.5  964.52  1150.8  969.53  1170.2  970.86
#Mann= 3 , 0 , 0
       0      .1       0   434.6    .045       0   467.8     .05       0
Bank Sta=434.6,467.8
XS Rating Curve= 0 ,0
Exp/Cntr=0.3,0.1

Type RM Length L Ch R = 1 ,247807.5,1350.9,1375.3,1399
XS GIS Cut Line= 4
     1579660.792      252910.284     1579215.391      253179.262
     1579113.917      253244.485     1578480.237      253674.172
#Sta/Elev= 30
       0   966.7    49.1     955    88.4   942.3   157.1  912.72   186.5  905.75
   255.2  877.49   314.2  858.68   333.8  850.14   373.1   829.8   402.5  817.75
     432  811.04   451.6  804.97   461.4  803.93   557.4  802.58     576  793.85
   585.3  790.76   594.6  790.34   613.1  793.82     641  797.58   807.8  801.07
   827.4  805.57   856.9  816.82   925.6  839.63   984.5  851.15  1023.8  862.25
  1043.4  864.79  1249.5  878.02    1279   884.3  1318.2  897.33  1406.6  913.26
#Mann= 3 , 0 , 0
       0     .08       0     576    .045       0   613.1     .06       0
Bank Sta=576,613.1
XS Rating Curve= 0 ,0
Exp/Cntr=0.3,0.1

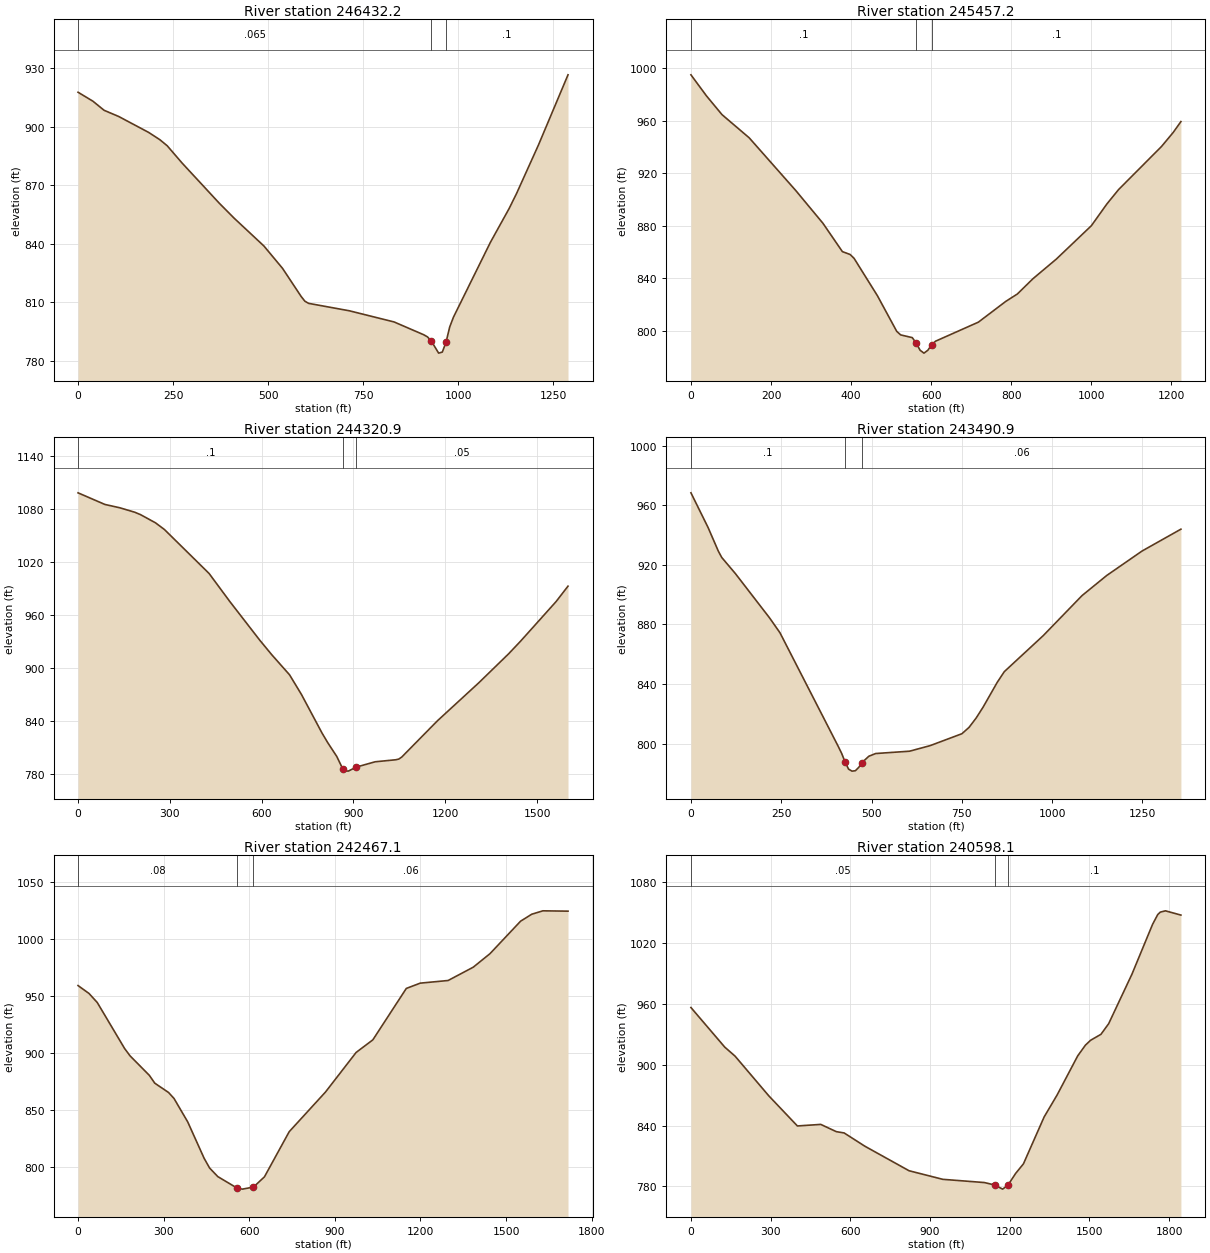
Type RM Length L Ch R = 1 ,246432.2,981.6,975,968.5
XS GIS Cut Line= 4
     1579575.162      252576.697      1578861.62      252113.155
     1578723.493      252040.408     1578470.995      251915.239
#Sta/Elev= 30
       0  917.67    39.1  913.08    68.5  908.42   107.6  905.18   185.8  897.07
   215.2  893.35   234.7  890.21   273.8  881.36   371.6  860.78   410.8  853.09
     489  838.86   537.9  827.41   586.8  813.03   596.6  810.59   606.4  809.48
     714  805.65   831.3  799.95   909.4  793.38   919.2  792.28     929  790.25
   948.5  783.97   958.2  784.51     968  789.62   977.7  797.42   987.5   802.4
  1084.8   840.8  1133.3  857.85  1152.8  865.49  1211.1  890.64  1288.8  926.59
#Mann= 3 , 0 , 0
       0    .065       0     929    .045       0     968      .1       0
Bank Sta=929,968
XS Rating Curve= 0 ,0
Exp/Cntr=0.3,0.1

Type RM Length L Ch R = 1 ,245457.2,1152.8,1136.3,1117.6
XS GIS Cut Line= 3
     1579856.412       251347.53     1579273.079      251248.572
     1578653.287      251123.572
#Sta/Elev= 30
       0  995.11    38.8  979.06    77.6  964.77   145.5  947.11   261.9  906.92
   329.8  881.95   378.3  860.38   397.7  858.19   407.4  855.31   465.6  826.88
   514.1  799.59   523.8  796.93   552.9  794.83   562.6  790.72   572.3  785.25
     582  783.03   591.7  785.19   601.4  789.44   611.1  792.14   718.1  806.65
   786.2   822.4   815.4  828.11   854.3  839.73   912.7  854.69  1000.2  880.12
  1039.1  896.75  1068.3  907.69  1175.3  940.46  1204.5  951.14  1223.9  959.47
#Mann= 3 , 0 , 0
       0      .1       0   562.6    .045       0   601.4      .1       0
Bank Sta=562.6,601.4
XS Rating Curve= 0 ,0
Exp/Cntr=0.3,0.1

Type RM Length L Ch R = 1 ,244320.9,841.2,830,817.2
XS GIS Cut Line= 4
     1579809.537      249764.197     1579149.815      250076.697
      1578924.12      250224.267     1578498.773      250649.614
#Sta/Elev= 30
       0 1097.84    87.6 1084.72   136.3 1080.95   184.9 1075.96   204.4 1073.14
   253.1 1063.93   282.3 1056.37   428.3 1006.64   496.4  974.77   593.7   931.3
   632.7  914.92   691.1  892.13     730  869.92   797.4  826.18   816.7  814.97
   845.6  799.72   864.8  785.91   874.4  783.17   884.1  783.31   908.3787.6299
   970.8  793.72  1038.5  796.02  1048.2   796.8  1057.9  799.08  1174.3  840.02
  1310.1  883.19  1407.1  915.82    1446  930.03  1562.4  974.93  1601.2  992.32
#Mann= 3 , 0 , 0
       0      .1       0   864.8    .045       0   908.3     .05       0
Bank Sta=864.8,908.3
XS Rating Curve= 0 ,0
Exp/Cntr=0.3,0.1

Type RM Length L Ch R = 1 ,243490.9,1019.7,1023.8,1028.7
XS GIS Cut Line= 5
     1578536.143      249368.697     1578422.606       249565.78
     1578318.083      249768.177     1578238.356      249937.808
     1578186.273      250649.614
#Sta/Elev= 30
       0  968.34    47.4  945.09    75.8  929.23    85.3  924.95   123.2   914.1
     218  884.31   246.4  874.47   407.8  798.18   417.3  793.46   426.8  787.66
   436.3  782.96   445.8   781.6   455.2  781.86   464.6  784.12   473.3787.3033
   492.7  791.62   511.5  793.41   605.2  794.97   662.2  798.71   750.2   806.7
   769.8  810.94   789.3  817.14   808.9  824.58     848  841.21   867.5  848.35
   975.1  872.48  1082.6  899.37  1151.1  912.89  1248.8  929.28  1356.4  943.95
#Mann= 3 , 0 , 0
       0      .1       0   426.8    .045       0   473.3     .06       0
Bank Sta=426.8,473.3
XS Rating Curve= 0 ,0
Exp/Cntr=0.3,0.1

Type RM Length L Ch R = 1 ,242467.1,1869.7,1869,1865.7
XS GIS Cut Line= 4
     1577865.093      248592.322     1577738.356      248955.169
     1577530.023      249219.058     1577344.259      250198.225
#Sta/Elev= 30
       0  959.22    38.4  952.31    67.3  944.39   163.4  903.98   182.6  897.54
   249.8  880.56     269  873.65   317.1  865.53   336.3   860.3   384.3  839.78
     442  807.78   461.2  799.27     490  791.74   557.2  781.76   576.5   780.8
   614.9  782.61   653.3  791.57   740.1  831.14   867.1  865.86   974.6   900.6
  1033.2  911.64  1150.5  956.71  1199.3  961.34    1297  963.66    1385  975.31
  1443.6  987.14  1551.1 1015.67  1590.2 1021.76  1629.2 1024.73  1717.2 1024.44
#Mann= 3 , 0 , 0
       0     .08       0   557.2    .045       0   614.9     .06       0
Bank Sta=557.2,614.9
XS Rating Curve= 0 ,0
Exp/Cntr=0.3,0.1

Type RM Length L Ch R = 1 ,240598.1,1637.6,1652.4,1665.8
XS GIS Cut Line= 4
     1576578.634      247976.003     1576002.259      248813.203
     1575856.412      249045.447     1575668.912       249566.28
#Sta/Elev= 30
       0  956.22     127  917.32   166.2  908.32   293.2  869.22   400.7   839.6
   488.7  841.13   547.3  833.98   576.6  832.72   654.8  819.63     821   795.5
     948  787.05  1104.6  783.87  1143.8  781.43  1173.1   777.4  1192.7  781.12
  1222.1  792.86  1251.5   802.3  1329.5  848.54  1378.1  870.05  1455.8  908.64
  1484.9  919.22  1504.3  923.98  1543.2  929.85  1572.3  940.32  1659.7  988.94
  1737.4 1038.06  1756.8  1047.7  1766.5 1050.16    1786 1051.45  1844.2 1047.25
#Mann= 3 , 0 , 0
       0     .05       0  1143.8    .045       0  1192.7      .1       0
Bank Sta=1143.8,1192.7
XS Rating Curve= 0 ,0
Exp/Cntr=0.3,0.1

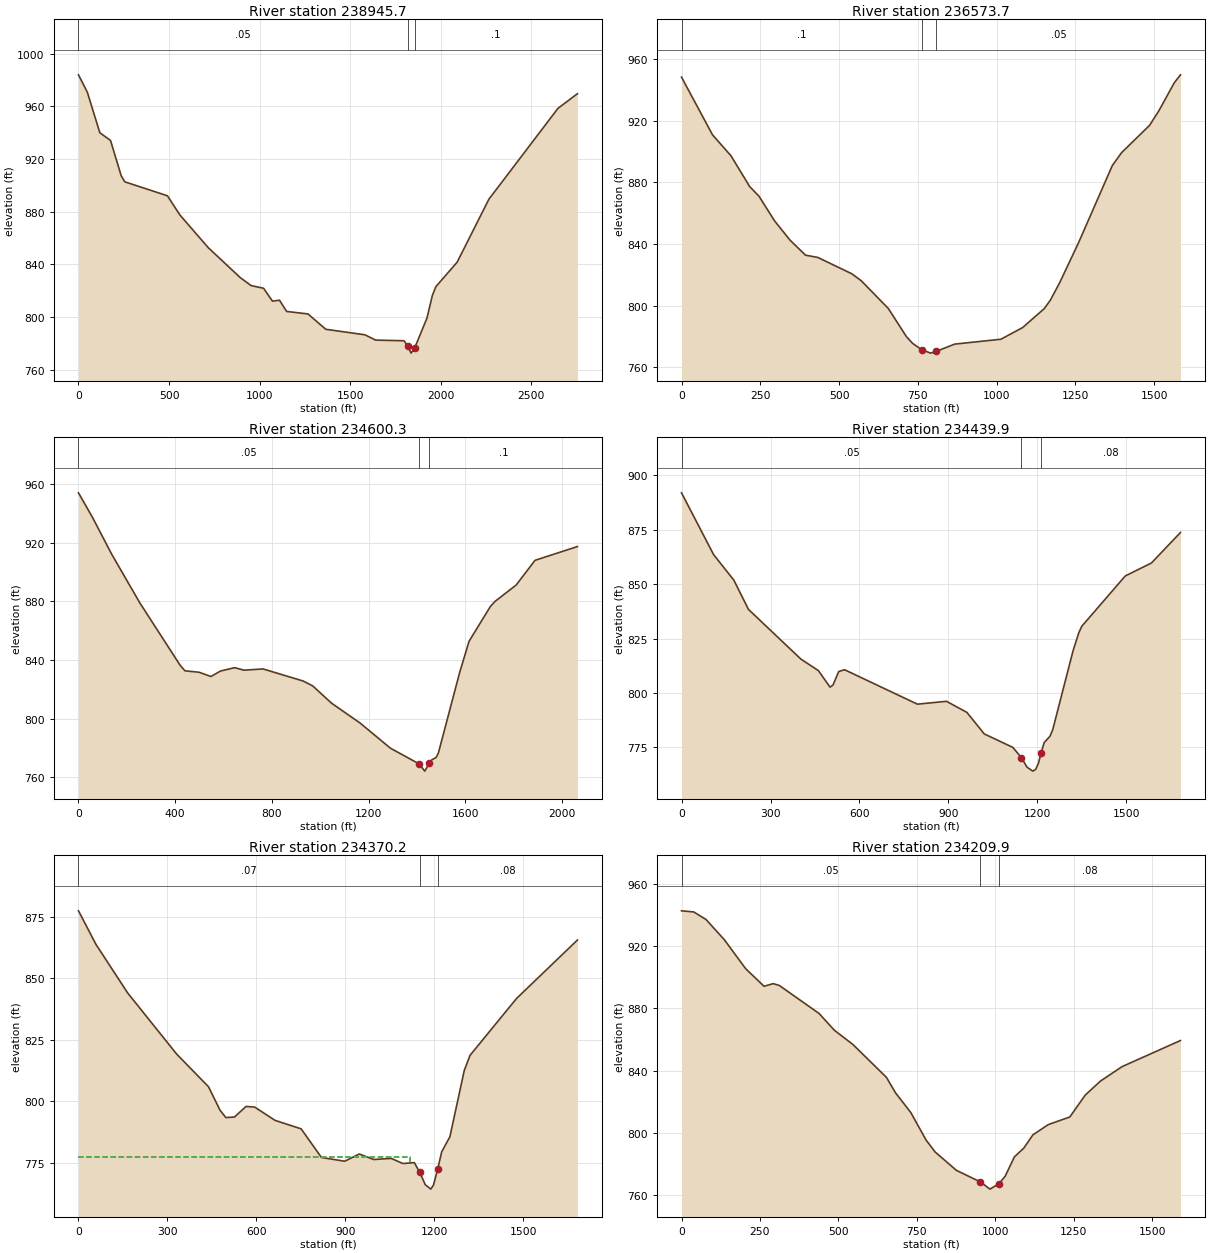
Type RM Length L Ch R = 1 ,238945.7,2383.1,2372,2359.6
XS GIS Cut Line= 4
     1576564.745      247413.503     1575064.745      248170.447
     1574800.856      248274.614     1574141.134      248712.114
#Sta/Elev= 30
       0  983.96    49.1  970.68   117.9  940.01   176.9  934.15   235.8  907.41
   255.5  902.75   491.3  892.14   560.1  877.58   717.3  852.66   894.1  829.94
   953.1  823.98  1021.9  821.96    1071  812.19  1110.3  812.84  1149.6  804.34
  1267.5  802.44  1365.8   790.8  1581.9  786.61  1640.9   782.6  1797.6  782.08
  1817.1  778.49  1836.7   772.7  1856.3  776.44  1924.7  799.39  1954.1  816.39
  1973.6  823.15  2090.9  841.68  2266.8  889.59    2648   958.5  2755.5  969.64
#Mann= 3 , 0 , 0
       0     .05       0  1817.1    .045       0  1856.3      .1       0
Bank Sta=1817.1,1856.3
XS Rating Curve= 0 ,0
Exp/Cntr=0.3,0.1

Type RM Length L Ch R = 1 ,236573.7,1960.8,1973.3,1985.1
XS GIS Cut Line= 4
     1574585.579       246753.78      1574196.69      247184.336
     1573995.301      247427.392     1573599.468      247989.892
#Sta/Elev= 30
       0  948.26    98.3  910.84   157.3  897.13   216.3  877.24   245.8     871
     295  855.07   344.2   842.5   393.3  832.72   432.7  831.21   540.8  820.59
   570.4   816.1   656.7  798.02   714.1  779.74   733.2  775.49   761.9  771.38
   790.6  769.11   808.4  770.26   867.1  774.96  1013.7  778.13  1082.5  785.69
  1151.3  797.98    1171   803.6  1200.4   814.9  1259.4  840.44  1367.5  890.94
    1397  899.31  1485.4  916.92  1514.9  926.36    1564  944.61  1583.6  949.76
#Mann= 3 , 0 , 0
       0      .1       0   761.9    .045       0   808.4     .05       0
Bank Sta=761.9,808.4
XS Rating Curve= 0 ,0
Exp/Cntr=0.3,0.1

Type RM Length L Ch R = 1 ,234600.3,155.4,160.4,164.9
XS GIS Cut Line= 4
     1574547.037      245974.614     1573289.225      246081.385
     1573078.287      246164.718     1572599.468      246482.947
#Sta/Elev= 30
       0  954.09    58.7  937.09     137  912.31   254.4  878.81   420.8  836.34
   440.4  832.61   499.1  831.62     548  828.73   587.1  832.44   645.8  834.76
     685  833.05   763.3   833.9   929.6  825.65   968.8  822.33    1047  810.51
  1164.5  797.03  1290.7  779.78  1409.5769.0458  1432.4  764.15  1451.3  769.42
  1460.8  771.77  1479.7  773.49  1489.1  776.64  1576.8  831.41  1615.8  852.78
  1703.5   876.4    1723  879.97  1810.7  891.18  1888.7  908.03  2064.1  917.42
#Mann= 3 , 0 , 0
       0     .05       0  1409.5    .045       0  1451.3      .1       0
Bank Sta=1409.5,1451.3
XS Rating Curve= 0 ,0
Exp/Cntr=0.3,0.1

Type RM Length L Ch R = 1 ,234439.9,71,69.7,68.8
XS GIS Cut Line= 4
     1574245.822      245847.878      1573242.35      245972.878
     1572995.822      246014.544     1572624.294      246212.461
#Sta/Elev= 30
       0   891.9     108  863.59   176.7  851.76   225.8  838.38   402.5  815.58
   461.4   810.3   500.7  802.71   510.5  803.62   530.2   809.9   549.8  810.69
   795.2  794.89   893.4   796.2   962.1  791.12  1020.8  781.22    1117  775.05
  1145.9  770.35  1165.1  765.95  1184.3  764.15  1193.9  764.94  1203.6  767.86
  1212.7772.6564  1222.8  777.28    1242  780.12  1251.6  783.18    1320  819.36
  1339.6  827.72  1349.4  830.63  1496.2  853.75  1584.3  859.69  1682.2  873.69
#Mann= 3 , 0 , 0
       0     .05       0  1145.9    .045       0  1212.7     .08       0
Bank Sta=1145.9,1212.7
XS Rating Curve= 0 ,0
Exp/Cntr=0.3,0.1

Type RM Length L Ch R = 1 ,234370.2,164.8,160.3,155.9
XS GIS Cut Line= 5
     1574221.516      245785.378     1573575.683      245880.169
     1573106.933      245923.572     1572971.516      245952.044
     1572599.988      246149.961
#Sta/Elev= 30
       0  877.35    58.5  863.81   165.6  844.02   331.2  819.12   438.4  805.88
   477.4  796.34   496.9  793.34   526.1  793.55   565.1  797.87   594.3   797.6
   662.6  792.22   750.8  788.76   819.5  777.12   897.9  775.59     947  778.54
     996  776.29  1054.9  776.75  1094.1  774.66  1132.7  775.03  1151.2  771.02
  1169.6  766.07  1188.1  764.26  1197.3  765.92  1211.6772.4637    1225  779.43
  1252.7  785.56    1301  812.43  1320.6  818.63  1477.3  841.71  1682.8  865.49
#Mann= 3 , 0 , 0
       0     .07       0  1151.2    .045       0  1211.6     .08       0
#XS Ineff= 2 , 0
         1116.97  777.31
Permanent Ineff=
       F       F
Bank Sta=1151.2,1211.6
XS Rating Curve= 0 ,0
Exp/Cntr=0.3,0.1

Type RM Length L Ch R = 1 ,234209.9,1132.1,1103.7,1074.7
XS GIS Cut Line= 4
     1573856.933      245316.628     1573183.322      245708.989
     1572950.683      245806.211     1572485.405      246115.239
#Sta/Elev= 30
       0  942.69      39  941.97      78  937.14   136.4  924.16   204.6  905.49
   263.1  894.22   292.3  895.93   311.8  894.74   438.5  876.75   487.2  865.97
   545.7  856.94   652.9  835.79   682.1  825.78   730.8  813.11   779.6  795.42
   808.6  787.74   876.5  775.95   952.7768.5589   983.2  763.94  1012.3  767.48
  1031.7  772.29  1061.1  784.72  1090.5  790.18  1119.9  798.79  1168.9  805.39
  1237.5  810.27  1286.5   824.3  1335.5  833.39  1404.1  842.63  1590.2  859.39
#Mann= 3 , 0 , 0
       0     .05       0   952.7    .045       0  1012.3     .08       0
Bank Sta=952.7,1012.3
XS Rating Curve= 0 ,0
Exp/Cntr=0.3,0.1

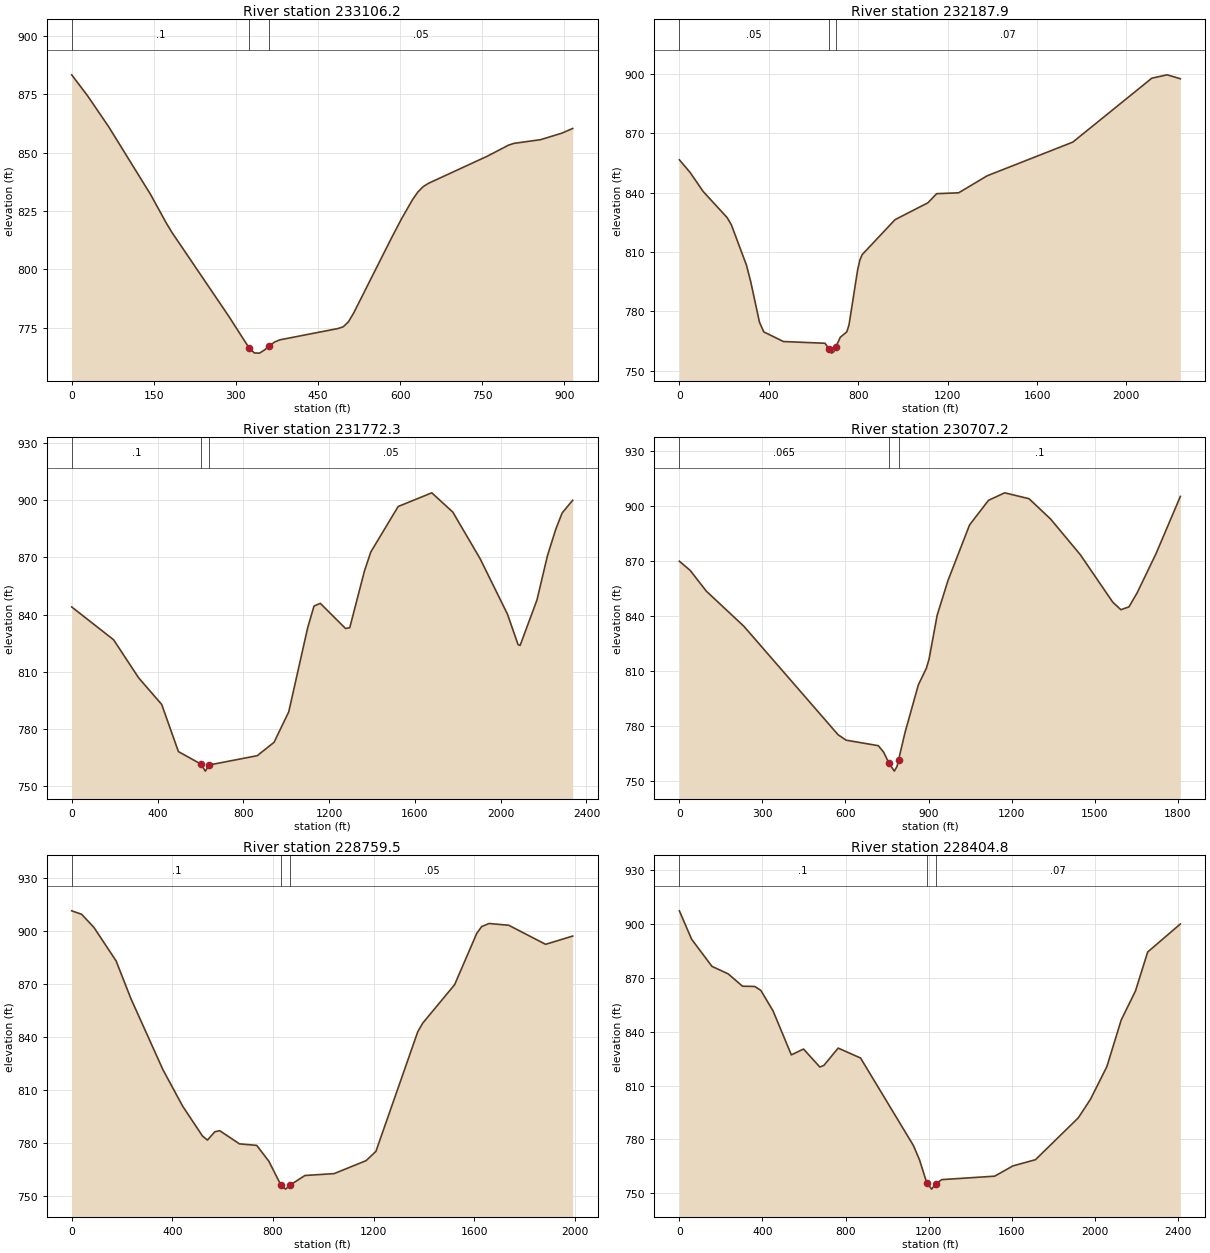
Type RM Length L Ch R = 1 ,233106.2,917.2,918.3,918.8
XS GIS Cut Line= 4
     1572035.401      245406.936     1572040.093      245647.096
     1572055.718       245824.18     1572206.759      246298.138
#Sta/Elev= 30
       0  883.36    28.8  874.44    67.3  861.19   144.1  832.06     173  819.73
   182.6  815.99     287  779.82   324.4  766.16   333.8  764.09   343.1  764.02
   352.5  765.41   361.3767.1982   371.2  768.84   380.6  769.73   486.2  774.55
     496  775.29   505.8  777.49   515.5  781.35   583.8  813.16   603.3  821.89
   622.8  829.85   632.6  833.14   642.3  835.43   652.1  836.86   759.4  848.47
   798.4  853.23   808.1  853.97   856.9  855.56   895.9  858.37   915.4  860.36
#Mann= 3 , 0 , 0
       0      .1       0   324.4    .045       0   361.3     .05       0
Bank Sta=324.4,361.3
XS Rating Curve= 0 ,0
Exp/Cntr=0.3,0.1

Type RM Length L Ch R = 1 ,232187.9,397.4,415.6,432.6
XS GIS Cut Line= 4
     1571644.259      245282.513     1571331.759       245542.93
     1571342.176      246022.096     1571472.384      247371.055
#Sta/Elev= 30
       0  856.67    48.4  850.22   106.5  840.63   213.1  827.49   232.4  823.82
   300.2  803.34   319.6  794.75   358.4  774.45   377.7  769.56   465.5  764.69
   651.3  763.82   669.4 761.032   680.7  758.82   690.4  759.45   700.2  762.04
   719.8  766.84   749.1   769.6   758.9  773.15     798  801.33   807.8  806.02
   817.6  808.65   964.6  826.36  1111.9  834.92  1151.2  839.54  1249.4  839.97
  1377.1  848.59  1760.1  865.63  2113.6  897.99  2182.4  899.69  2241.3   897.7
#Mann= 3 , 0 , 0
       0     .05       0   669.4    .045       0   700.2     .07       0
Bank Sta=669.4,700.2
XS Rating Curve= 0 ,0
Exp/Cntr=0.3,0.1

Type RM Length L Ch R = 1 ,231772.3,1036.5,1065.1,1092.7
XS GIS Cut Line= 4
     1571456.759      245282.513     1571024.468      245662.721
      1570933.31      245758.674     1569597.384      246688.763
#Sta/Elev= 30
       0     844   195.2  826.77   312.2  806.73   419.6  792.76   497.6  767.98
   602.4761.4207     623  757.72   641.9  760.97     865  765.84   943.4  772.85
    1012  788.89  1100.3  833.11  1129.7  844.47  1159.1   845.9  1276.8  832.69
  1296.4  833.09  1365.1  862.96  1394.5  872.87    1522  896.78  1678.9  903.98
  1776.9  893.86  1904.4  869.34  2031.9  840.19  2080.9  824.31  2090.7  823.76
  2169.2  847.62  2218.2  870.94  2257.4  884.98  2286.8  893.42  2335.9  900.09
#Mann= 3 , 0 , 0
       0      .1       0   602.4    .045       0   641.9     .05       0
Bank Sta=602.4,641.9
XS Rating Curve= 0 ,0
Exp/Cntr=0.3,0.1

Type RM Length L Ch R = 1 ,230707.2,1957.6,1947.7,1937
XS GIS Cut Line= 4
     1571800.509      245115.846     1571128.634      244959.596
     1570935.926      244871.055     1570066.134      244610.638
#Sta/Elev= 30
       0     870    38.9  865.02    97.2  853.69   233.2  834.46   573.2  775.29
   602.4  772.31   718.7   769.3     738  765.74   757.3  759.68   776.6  755.41
   786.2  757.98   791.9761.5998   815.1  776.48   863.3  802.54   892.2  811.56
   901.9  816.54   931.2   840.5   970.2  859.43  1048.3  889.84  1116.7  903.26
  1175.2  907.35  1263.1  904.14  1341.2  893.02  1448.6  873.52  1565.8   847.6
    1595  843.54  1624.3  845.11  1653.6  852.73    1722  874.18  1809.8  905.39
#Mann= 3 , 0 , 0
       0    .065       0   757.3    .045       0   791.9      .1       0
Bank Sta=757.3,791.9
XS Rating Curve= 0 ,0
Exp/Cntr=0.3,0.1

Type RM Length L Ch R = 1 ,228759.5,367.7,354.7,341.6
XS GIS Cut Line= 4
     1572456.759       244136.68     1572034.884      243522.096
     1571805.718      243532.513     1570821.343      243787.721
#Sta/Elev= 30
       0  911.58    39.2  909.65    88.3  902.22   176.6  883.21   235.4  861.89
   362.9  821.62   441.4  800.98   519.8  784.19   539.5  781.85   568.9  786.56
   588.5  787.17     667  779.72   735.6  778.86   783.7  769.92   831.5  756.49
   850.6  754.11   869.7  756.54   927.1  761.81  1043.3  762.89  1170.4  770.22
  1209.5  775.48  1375.8  843.14  1395.3  847.99  1522.4   869.8  1610.4  898.84
    1630  902.68  1659.3  904.41  1737.5  903.42  1884.2  892.63  1991.8   897.3
#Mann= 3 , 0 , 0
       0      .1       0   831.5    .045       0   869.7     .05       0
Bank Sta=831.5,869.7
XS Rating Curve= 0 ,0
Exp/Cntr=0.3,0.1

Type RM Length L Ch R = 1 ,228404.8,1915.3,1926.3,1937.4
XS GIS Cut Line= 4
     1572873.426       242574.18     1571988.009      243079.388
     1571701.551      243282.513     1570738.009      243678.346
#Sta/Elev= 30
       0  907.28    58.8  891.48   156.8  876.37   235.2  872.18   303.9  865.31
   362.7  865.19   392.1     863   450.9  851.61   539.1  827.09   597.9  830.34
   676.3  820.32   695.9  821.24   764.6  830.86   872.4  825.34  1126.7  776.66
    1156  768.74 1190.93755.9135  1214.5  752.35    1234   755.2  1263.3  757.64
    1518  759.56  1606.4   765.3  1714.5  768.72  1920.9  792.05  1979.9  802.45
  2058.5  820.59  2127.3  846.46  2196.1  862.66    2255  884.37  2412.3  899.96
#Mann= 3 , 0 , 0
       0      .1       0 1190.93    .045       0    1234     .07       0
Bank Sta=1190.93,1234
XS Rating Curve= 0 ,0
Exp/Cntr=0.3,0.1

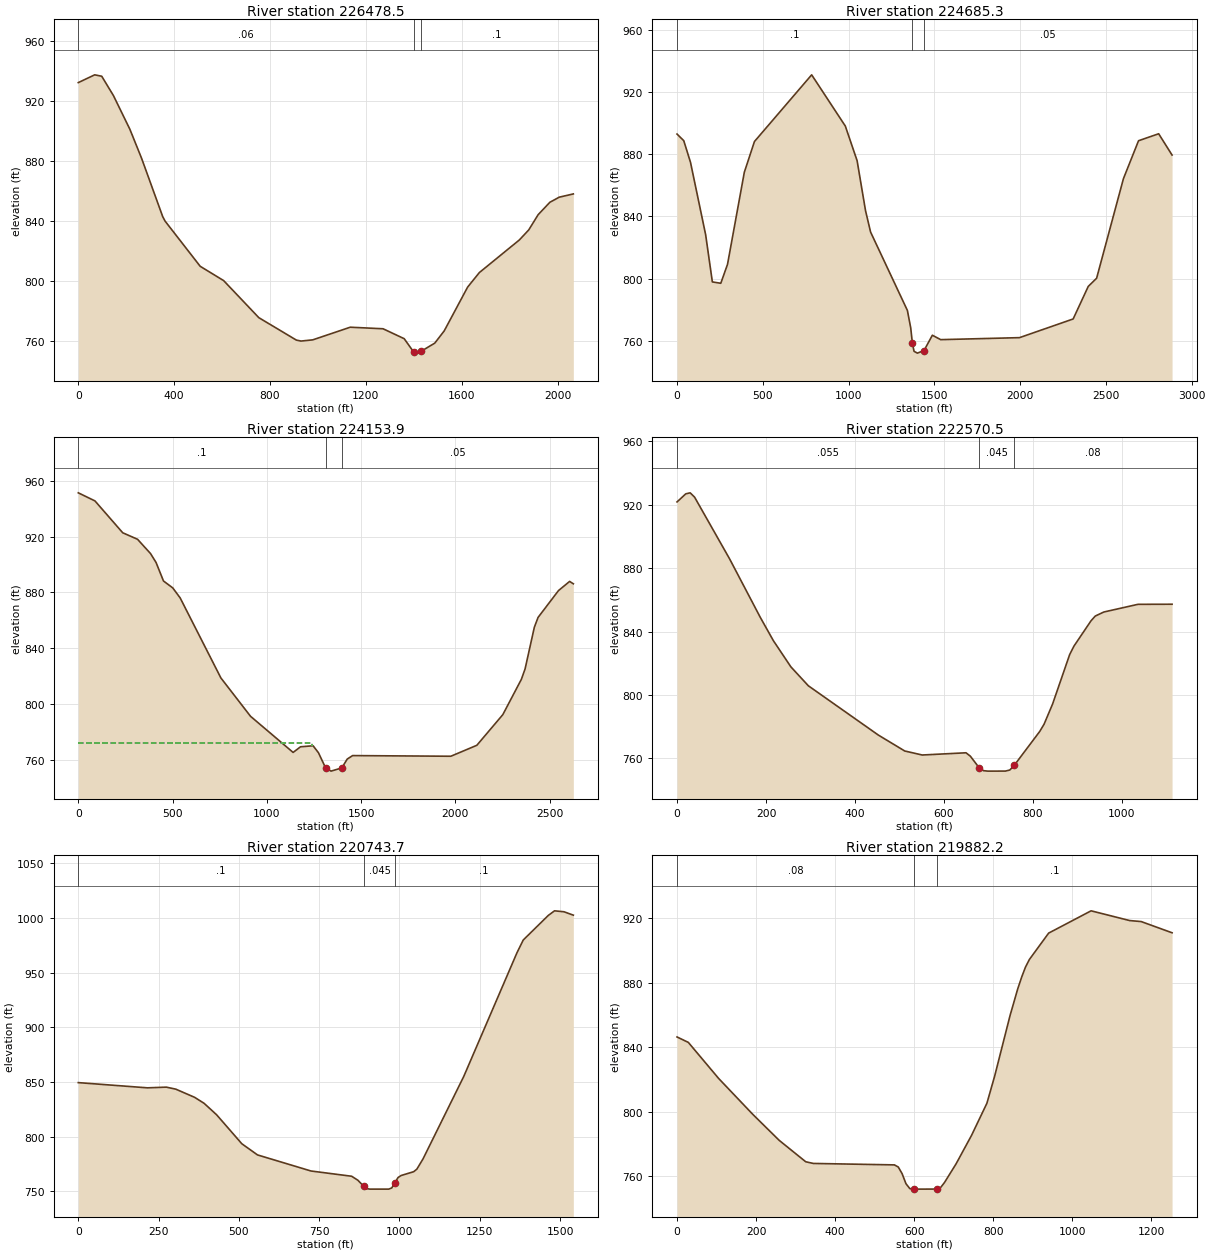
Type RM Length L Ch R = 1 ,226478.5,1801.7,1793.3,1782.2
XS GIS Cut Line= 4
     1571753.634      242147.096     1570447.883      242343.497
     1570243.218      242365.846     1569738.009      242553.346
#Sta/Elev= 30
       0  932.02    68.5  937.19    97.8  936.25   146.7  923.36   215.2  900.99
   264.1  881.66   352.1  842.92   361.9  839.94   508.6  809.84   606.4  800.33
   753.1  775.69   909.6  760.78   929.2  760.12   978.1  760.92  1134.6  769.34
  1271.5   768.3  1359.6   761.7  1398.9  752.89  1408.7   752.1    1429 753.205
  1487.1  758.75  1526.3  766.82  1624.3  796.03  1673.3   805.7  1839.8  827.34
    1879     834  1918.2  844.13  1967.2  852.41  2006.4  855.82  2065.2  857.98
#Mann= 3 , 0 , 0
       0     .06       0  1398.9    .045       0    1429      .1       0
Bank Sta=1398.9,1429
XS Rating Curve= 0 ,0
Exp/Cntr=0.3,0.1

Type RM Length L Ch R = 1 ,224685.3,553.2,531.3,507.6
XS GIS Cut Line= 4
     1572357.801      240298.138     1571211.968      240787.721
     1570988.009      240923.138     1570045.301      241928.346
#Sta/Elev= 30
       0  892.88    39.2  888.63    78.5  874.75   166.8  828.22     206  797.87
   255.1  796.98   294.3  809.13   392.4  868.36   451.3  888.07   784.9  930.94
   981.1  898.01  1049.8  875.76  1098.9  843.64  1128.3  829.92    1343  779.51
  1362.4  768.25  1372.1  758.31  1381.8  753.26  1401.1   752.1  1439.9  753.76
  1488.4   763.6  1537.1  760.76  1996.4  762.05  2309.2  774.05  2397.2  794.97
    2446  800.23  2602.4  864.25  2690.4  888.59  2807.7  893.07  2885.8  879.38
#Mann= 3 , 0 , 0
       0      .1       0  1372.1    .045       0  1439.9     .05       0
Bank Sta=1372.1,1439.9
XS Rating Curve= 0 ,0
Exp/Cntr=0.3,0.1

Type RM Length L Ch R = 1 ,224153.9,1585.4,1583.4,1581.6
XS GIS Cut Line= 4
     1570571.343      239412.721     1570628.634      240589.805
     1570581.759      240881.471     1569993.218      241871.055
#Sta/Elev= 30
       0  951.29    88.4   945.5   235.7  922.69   314.3  918.04     383  907.83
   412.5  901.42   451.8  888.19   500.8  883.26   540.1  876.11   756.2   818.8
   913.3  791.36  1139.2  765.48  1178.5  769.52  1245.2  770.25  1273.8  765.23
  1311.9  754.28  1340.5   752.1  1397.6  754.41  1426.2  760.73  1454.8  763.22
  1975.8  762.75  2113.5  770.59  2251.3  792.52  2349.7  817.79  2369.4  825.25
  2418.6  855.12  2438.3  862.11  2546.5  881.31  2605.6  887.88  2625.3  886.18
#Mann= 3 , 0 , 0
       0      .1       0  1311.9    .045       0  1397.6     .05       0
#XS Ineff= 2 , 0
         1239.37  772.04
Permanent Ineff=
       F       F
Bank Sta=1311.9,1397.6
XS Rating Curve= 0 ,0
Exp/Cntr=0.3,0.1

Type RM Length L Ch R = 1 ,222570.5,1831.3,1826.8,1822
XS GIS Cut Line= 3
     1569508.843      240865.846     1569446.343      241621.055
     1569425.509      241975.221
#Sta/Elev= 30
       0   921.7    19.7  926.81    29.5  927.44    39.4  924.75   118.1  885.84
     187  849.01   216.5  834.26   255.9  817.73   295.2  805.79   452.7  774.69
   511.8  764.69   551.1  762.16   649.5  763.56   659.4  761.38   679.1  754.08
   688.9  752.28   698.7     752   738.1  752.03     748  752.71   757.8  755.61
   815.3  777.06   824.9  781.56   844.1  794.32   882.4  825.44     892  830.77
   930.4  846.75     940  849.76   959.2   852.3  1035.9  857.15  1112.6  857.21
#Mann= 3 , 0 , 0
       0    .055       0   679.1    .045       0   757.8     .08       0
Bank Sta=679.1,757.8
XS Rating Curve= 0 ,0
Exp/Cntr=0.3,0.1

Type RM Length L Ch R = 1 ,220743.7,836.9,861.5,886
XS GIS Cut Line= 4
     1568180.718      241740.846     1568310.926       242542.93
     1568331.759      242714.805     1568394.259      243266.888
#Sta/Elev= 30
       0  849.46   215.4  844.69   274.1  845.32   303.5  843.49   362.2     836
   391.6  830.54   430.8     820   509.1  793.54     558   783.3   724.5  768.59
   851.1  763.78   870.3  760.17   889.5  754.41   899.2  752.35   908.8     752
   966.5     752   976.1  753.14   985.7   757.8   995.5  762.59  1005.2  764.47
  1044.2  767.94    1054  770.24  1073.4   779.7  1200.2  855.15  1365.9  968.35
  1385.4  979.98  1463.4 1002.46  1482.8 1006.66  1512.1  1005.8  1541.3  1002.7
#Mann= 3 , 0 , 0
       0      .1       0   889.5    .045       0   985.7      .1       0
Bank Sta=889.5,985.7
XS Rating Curve= 0 ,0
Exp/Cntr=0.3,0.1

Type RM Length L Ch R = 1 ,219882.2,567.5,573.6,579.8
XS GIS Cut Line= 3
     1568147.974      241784.633     1567898.842      242009.025
     1567144.502       242531.16
#Sta/Elev= 30
       0  846.31    28.7  842.92   105.4  820.57   191.6  798.38   258.6  782.22
   325.7  768.96     345  767.92     550  767.02   559.8  765.73   569.5  761.64
   579.3  755.38     589  752.34   598.8     752   657.4  752.03   667.1  753.02
   676.9  756.13   706.2  767.69   745.2  785.28   784.2  805.26   803.8  822.07
   842.8  859.66   862.3  876.22   872.1   883.4   881.8  889.62   891.6  894.31
   940.4  910.67  1047.8  924.48  1145.4  918.45  1174.6  917.82  1252.7  910.88
#Mann= 3 , 0 , 0
       0     .08       0   598.8    .045       0   657.4      .1       0
Bank Sta=598.8,657.4
XS Rating Curve= 0 ,0
Exp/Cntr=0.3,0.1