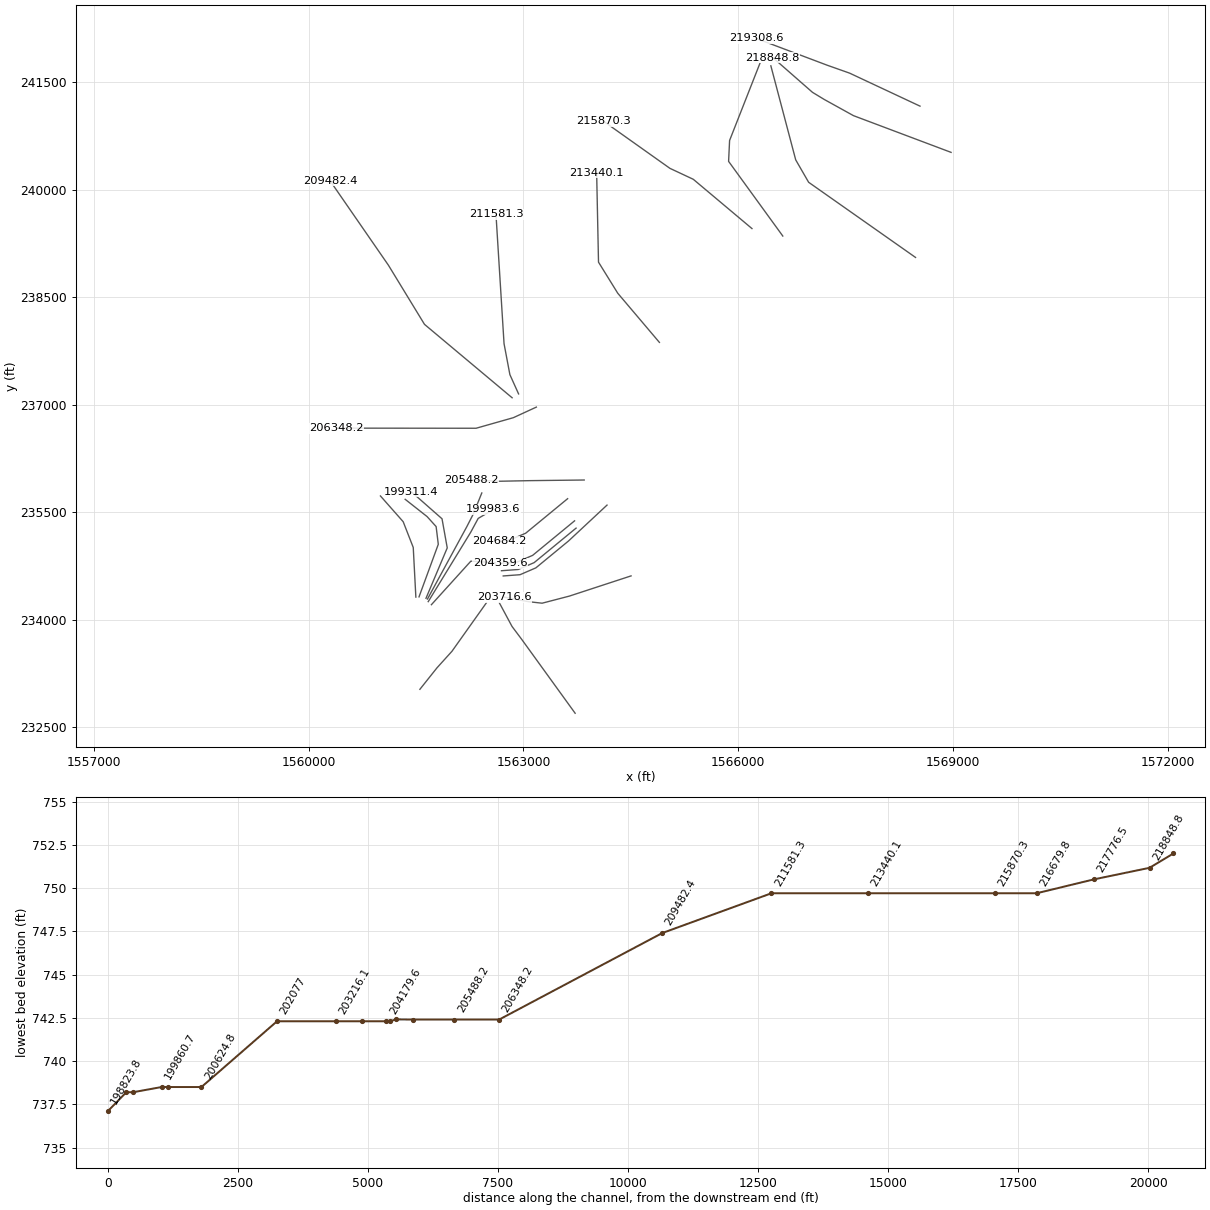
HEC-RAS study SFHGHSRV.prj: SFHGHSRV

--- SFHGHSRV.g01 (geometry) --- (continued)

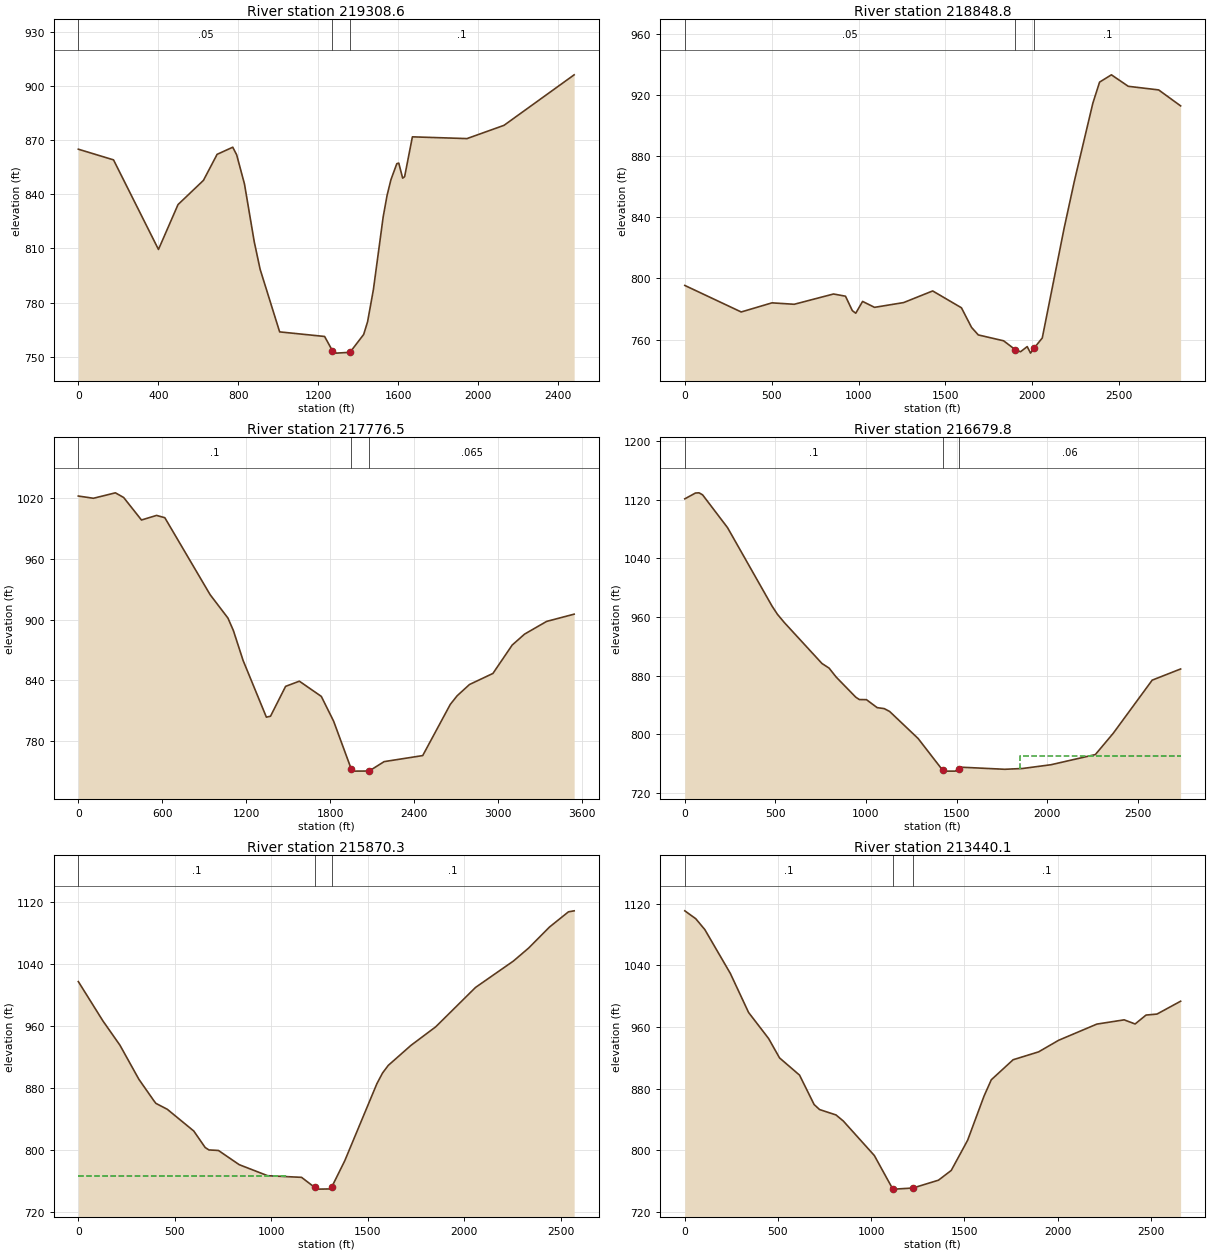
Type RM Length L Ch R = 1 ,219308.6,464.8,459.8,454.8
XS GIS Cut Line= 4
     1568540.093      241164.458     1567556.791      241624.965
     1567243.218      241735.638     1566248.426      242110.638
#Sta/Elev= 30
       0  864.99   176.1  859.08   401.1  809.44   498.9   834.3     626   847.7
   694.5  862.14   772.8  866.09   792.3  861.91   831.5   845.7   880.4   813.7
   909.7   798.5  1007.5  763.77  1232.5  761.23  1271.6  753.34  1291.2     752
  1359.6  752.45  1428.1  762.36  1447.6  769.39  1476.8  787.29  1525.6  827.46
  1545.1  839.41  1564.6  848.15  1593.9  856.96  1603.6   857.3  1623.2  848.94
  1632.9  849.76  1671.9  871.84    1945  870.87  2130.3  878.21  2481.4   906.2
#Mann= 3 , 0 , 0
       0     .05       0  1271.6    .045       0  1359.6      .1       0
Bank Sta=1271.6,1359.6
XS Rating Curve= 0 ,0
Exp/Cntr=0.3,0.1

Type RM Length L Ch R = 1 ,218848.8,1083.7,1072.3,1060.9
XS GIS Cut Line= 5
     1568974.095      240519.324     1567611.248      241031.477
     1567203.261      241257.171     1567038.331      241356.998
     1566482.775      241843.109
#Sta/Elev= 30
       0  795.43   324.6  778.08   501.7  784.04   629.6  783.11   855.8  789.83
   924.7  788.39     964  778.98   983.7  777.26  1023.1  784.98  1091.9   781.1
  1259.2  784.22  1426.4  791.83  1591.9  780.82  1650.2  767.97    1689  763.07
  1834.7  759.23  1902.7  753.32  1931.8  752.06  1970.4  755.44  1989.6  751.17
  2008.9  754.29  2057.1  761.08  2182.9  832.89  2241.2  863.36  2348.1  914.59
  2386.9  928.37  2454.9  933.13    2552  925.63  2726.9  923.26  2853.2  912.83
#Mann= 3 , 0 , 0
       0     .05       0  1902.7    .045       0  2008.9      .1       0
Bank Sta=1902.7,2008.9
XS Rating Curve= 0 ,0
Exp/Cntr=0.3,0.1

Type RM Length L Ch R = 1 ,217776.5,1109.5,1096.6,1083.7
XS GIS Cut Line= 4
     1568477.593      239053.346     1566984.537      240101.958
     1566803.981      240414.458     1566456.759      241726.958
#Sta/Elev= 30
       0 1021.83   107.9 1019.63   264.8    1025   323.7 1020.42   451.2   998.2
   559.1 1002.72     618 1000.47   941.7  924.56  1069.2  901.45  1108.4  889.03
  1177.1  859.77  1343.8  803.72  1373.3  804.66  1481.2  834.12  1579.3  839.22
  1736.2  824.22  1824.5  799.71  1951.3  752.16  1970.8   750.5  2078.1   750.6
  2185.4  759.88  2460.9  765.83  2657.6  816.24  2706.8  824.81  2795.4  835.96
  2962.6  846.85  3100.4  874.87  3188.9  885.65  3346.3  898.17  3543.1  905.33
#Mann= 3 , 0 , 0
       0      .1       0  1951.3    .045       0  2078.1    .065       0
Bank Sta=1951.3,2078.1
XS Rating Curve= 0 ,0
Exp/Cntr=0.3,0.1

Type RM Length L Ch R = 1 ,216679.8,783,809.5,836.1
XS GIS Cut Line= 4
     1566623.426      239351.958     1565866.481      240393.624
      1565880.37      240685.291     1566303.981       241761.68
#Sta/Elev= 30
       0 1121.37      59 1129.31    78.6 1129.57    98.3  1126.8   235.9 1082.05
   481.6  974.93   511.1  963.82   550.4  952.22   756.9  896.66   796.2  890.34
   835.5  878.08   943.6  850.63   963.3  847.41  1002.6  847.23  1061.6  836.37
  1100.9     835  1130.4  831.15  1287.6  794.27  1423.9  750.71  1443.4   749.7
    1492   749.7  1511.5  752.62    1531     755  1765.9  752.21  1863.9  753.29
  2020.8  758.42  2265.8   772.3  2363.9  801.16  2579.5  873.89  2736.4  889.15
#Mann= 3 , 0 , 0
       0      .1       0  1423.9    .045       0  1511.5     .06       0
#XS Ineff= 2 , 0
                         1852.33          769.77
Permanent Ineff=
       F       F
Bank Sta=1423.9,1511.5
XS Rating Curve= 0 ,0
Exp/Cntr=0.3,0.1

Type RM Length L Ch R = 1 ,215870.3,2443.2,2430.2,2417.2
XS GIS Cut Line= 4
      1566192.87      239456.124     1565373.426      240143.624
     1565047.037      240296.402     1564116.481      240956.124
#Sta/Elev= 30
       0 1017.22   127.6  966.48   215.9  935.16     314  891.26   392.5  863.36
   402.3  860.22   461.2  852.63   598.6  824.59   657.5  803.39   677.1   800.2
   726.2  799.56   834.1  781.23   981.3  767.01  1157.3  764.88  1225.5  751.94
    1245   749.7  1303.4  749.94  1313.1  752.02  1381.3  786.22    1548  885.65
  1577.5  899.47    1607   909.2    1725  935.09  1852.9   958.9  2059.4 1009.68
    2256 1043.73  2334.7 1060.43  2442.9 1087.53  2541.2 1107.14  2570.7 1108.42
#Mann= 3 , 0 , 0
       0      .1       0  1225.5    .045       0  1313.1      .1       0
#XS Ineff= 2 , 0
         1088.84  766.05
Permanent Ineff=
       F       F
Bank Sta=1225.5,1313.1
XS Rating Curve= 0 ,0
Exp/Cntr=0.3,0.1

Type RM Length L Ch R = 1 ,213440.1,1867.7,1858.8,1850.4
XS GIS Cut Line= 4
     1564900.075      237867.756     1564318.478       238553.52
     1564049.381      238987.548     1564023.339      240237.548
#Sta/Elev= 30
       0 1110.97    58.6 1100.78   107.5 1086.61   244.3 1029.72   342.1  979.06
   449.6  945.23   508.2  920.07   615.7  897.66   693.9  859.49   723.2  852.99
   811.2     846   850.3  838.14    1017   793.3  1115.2  750.09  1125.1   749.7
  1223.3  751.11  1360.8  761.29  1429.4  773.94  1517.3   813.1  1605.2  870.36
  1644.3  891.64  1761.5  917.67  1898.2  927.89  2005.7  942.93  2210.8  963.94
  2357.3  969.45  2415.9  964.09  2474.6  975.66  2533.2  976.94  2660.1  993.62
#Mann= 3 , 0 , 0
       0      .1       0  1115.2    .045       0  1223.3      .1       0
Bank Sta=1115.2,1223.3
XS Rating Curve= 0 ,0
Exp/Cntr=0.3,0.1

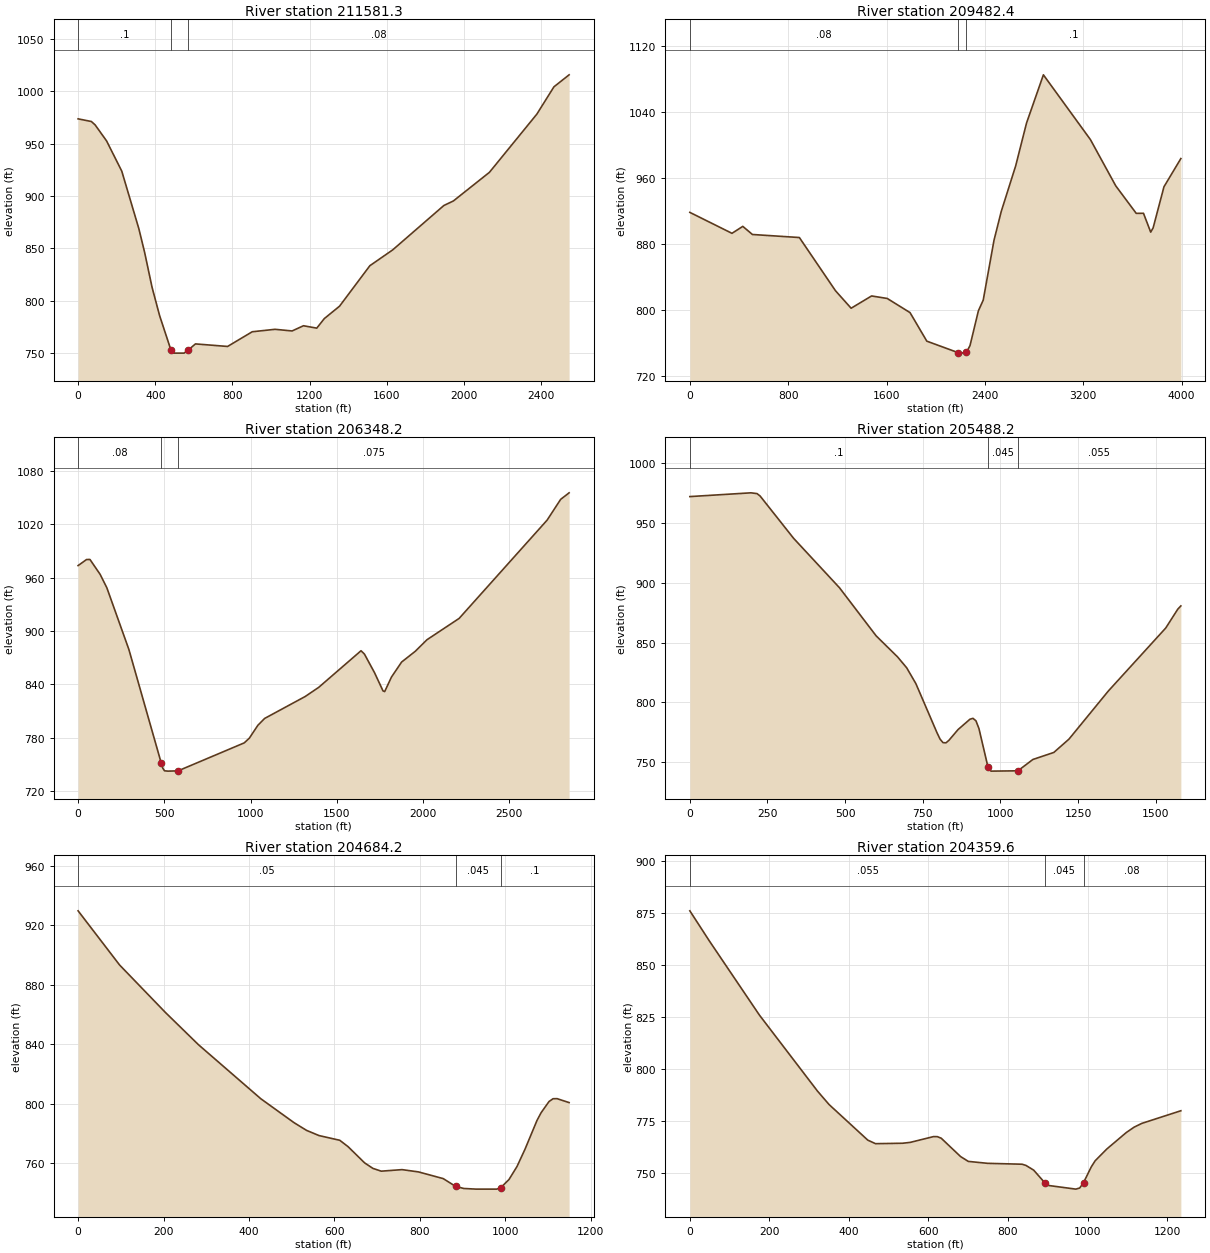
Type RM Length L Ch R = 1 ,211581.3,2090.2,2098.8,2106.7
XS GIS Cut Line= 4
     1562933.061      237148.934     1562811.534      237418.031
     1562729.936      237850.395     1562617.089      239655.951
#Sta/Elev= 30
       0   973.8    68.9  971.25    88.6  967.94   147.6   952.7   226.4  923.75
   314.8  868.74   344.2  846.53   383.3  812.66   422.4  785.57     481  752.72
   490.8   749.7   549.5  749.72     569   752.4   608.2  758.52   774.6  756.08
   902.4  770.14  1020.4  772.48  1108.9  770.91  1167.9  775.89  1236.7   773.6
    1276  782.76  1354.7  794.58    1512  833.34    1630  848.43  1895.4  890.92
  1944.6  895.25  2131.4  922.63  2377.2  978.32  2465.7 1004.43  2544.3  1015.9
#Mann= 3 , 0 , 0
       0      .1       0     481    .045       0     569     .08       0
Bank Sta=481,569
XS Rating Curve= 0 ,0
Exp/Cntr=0.3,0.1

Type RM Length L Ch R = 1 ,209482.4,3105.1,3134.2,3163.4
XS GIS Cut Line= 4
     1562842.784      237095.187     1561618.825      238119.492
     1561115.353      238944.145     1560300.683      240122.024
#Sta/Elev= 30
       0   918.2   342.7  892.79   430.8  901.22   509.2  891.37     891  887.68
  1184.8  823.11  1312.1  801.88  1478.5  816.78  1605.8  813.73  1791.2  796.58
  1927.8  761.92  2181.6  748.04  2201.1   747.4  2249.9  748.32  2279.2  756.59
  2347.5  798.86  2386.5  811.64  2474.4   884.4  2532.9  919.14  2650.5  974.59
  2738.8 1026.54  2876.1 1085.12  3258.7 1006.51  3464.7  950.41  3631.4     917
  3690.3   917.1  3749.1  894.23  3768.8  899.38    3857  949.28  3994.4  983.52
#Mann= 3 , 0 , 0
       0     .08       0  2181.6    .045       0  2249.9      .1       0
Bank Sta=2181.6,2249.9
XS Rating Curve= 0 ,0
Exp/Cntr=0.3,0.1

Type RM Length L Ch R = 1 ,206348.2,865.5,860,854.4
XS GIS Cut Line= 4
     1563181.325      236964.978     1562860.145      236817.409
     1562339.311      236669.839     1560387.488      236671.503
#Sta/Elev= 30
       0  973.52    49.1  980.34    68.7  980.41   127.6  963.72   166.9  948.48
   294.6  879.12   481.4  751.94   491.2  745.64   501.1  742.75   520.8   742.4
   579.8  742.72   963.4  774.18   992.9  779.49  1041.9  793.85  1081.2   801.6
  1316.6  826.31    1395   836.6  1640.2  877.76  1659.8  874.08  1718.7  853.04
  1767.7  832.61  1777.5  831.87  1816.8  848.19  1875.6  865.06  1954.1  877.04
  2022.7  890.16  2209.1  914.13  2719.1 1024.63  2797.6 1047.98  2846.6 1055.33
#Mann= 3 , 0 , 0
       0     .08       0   481.4    .045       0   579.8    .075       0
Bank Sta=481.4,579.8
XS Rating Curve= 0 ,0
Exp/Cntr=0.3,0.1

Type RM Length L Ch R = 1 ,205488.2,795.3,804,812.8
XS GIS Cut Line= 4
     1563849.728      235947.545      1563092.35      235938.864
     1562658.322      235930.184     1562268.999      235948.304
#Sta/Elev= 30
       0  972.28   196.7  975.43   216.4  974.78   226.2  972.79   334.4  937.27
     482  895.92     600  855.67   668.9  838.06   698.4  828.89   727.9  815.68
     796  774.53   805.7  769.25   815.3  766.25     825  766.11   834.6  768.26
   863.6  777.16   902.1  785.86   911.8  786.61   921.4  784.54   931.1  778.01
     960  745.96   969.7   742.4  1056.5  742.66  1104.7  752.15  1172.2  758.05
  1220.8  769.15  1347.4  809.38  1532.6  862.24  1571.5  878.06  1581.3  880.74
#Mann= 3 , 0 , 0
       0      .1       0     960    .045       0  1056.5    .055       0
Bank Sta=960,1056.5
XS Rating Curve= 0 ,0
Exp/Cntr=0.3,0.1

Type RM Length L Ch R = 1 ,204684.2,324.7,324.6,324.5
XS GIS Cut Line= 4
     1563617.957       235687.02      1563032.02      235205.249
     1562810.666      235109.763      1562661.36      235094.138
#Sta/Elev= 30
       0  929.63    97.2  893.19   204.2  861.34     282  839.53   427.9   803.2
   505.7  787.11   534.9  781.94   564.1  778.44   612.7  775.27   632.1     771
     671  760.05   690.5  756.34   709.9  754.48   758.6  755.52   797.1  753.98
     855  749.48   883.9  744.27   903.2  742.84   932.1   742.4   980.4   742.4
     990  743.46    1009  748.86  1027.8  757.63  1046.6   769.3  1074.7  788.67
  1084.1  793.76  1102.8  801.35  1112.2  803.21  1121.6  803.27  1149.8  800.62
#Mann= 3 , 0 , 0
       0     .05       0   883.9    .045       0     990      .1       0
Bank Sta=883.9,990
XS Rating Curve= 0 ,0
Exp/Cntr=0.3,0.1

Type RM Length L Ch R = 1 ,204359.6,101.6,101.6,101.5
XS GIS Cut Line= 4
     1563715.179      235377.992     1563129.242      234896.221
     1562907.888      234800.735     1562673.513      234783.374
#Sta/Elev= 30
       0  876.17    48.6  861.83     175  826.05   320.9  789.55   350.1  783.07
   447.4  765.97   466.8  764.26   534.9  764.46   554.3  764.88   612.7  767.66
   622.4  767.63   632.1  766.88   680.8  758.06   700.2  755.74   748.8  754.81
   835.7  754.38   845.4  753.78   864.6  751.54   893.6  745.23   903.2  744.13
   970.7  742.41   980.4  742.97     990  745.55  1009.4  753.09  1019.2  756.04
  1048.6  761.71  1097.6  769.63  1117.2   772.2  1136.7  774.02  1234.7  780.08
#Mann= 3 , 0 , 0
       0    .055       0   893.6    .045       0     990     .08       0
Bank Sta=893.6,990
XS Rating Curve= 0 ,0
Exp/Cntr=0.3,0.1

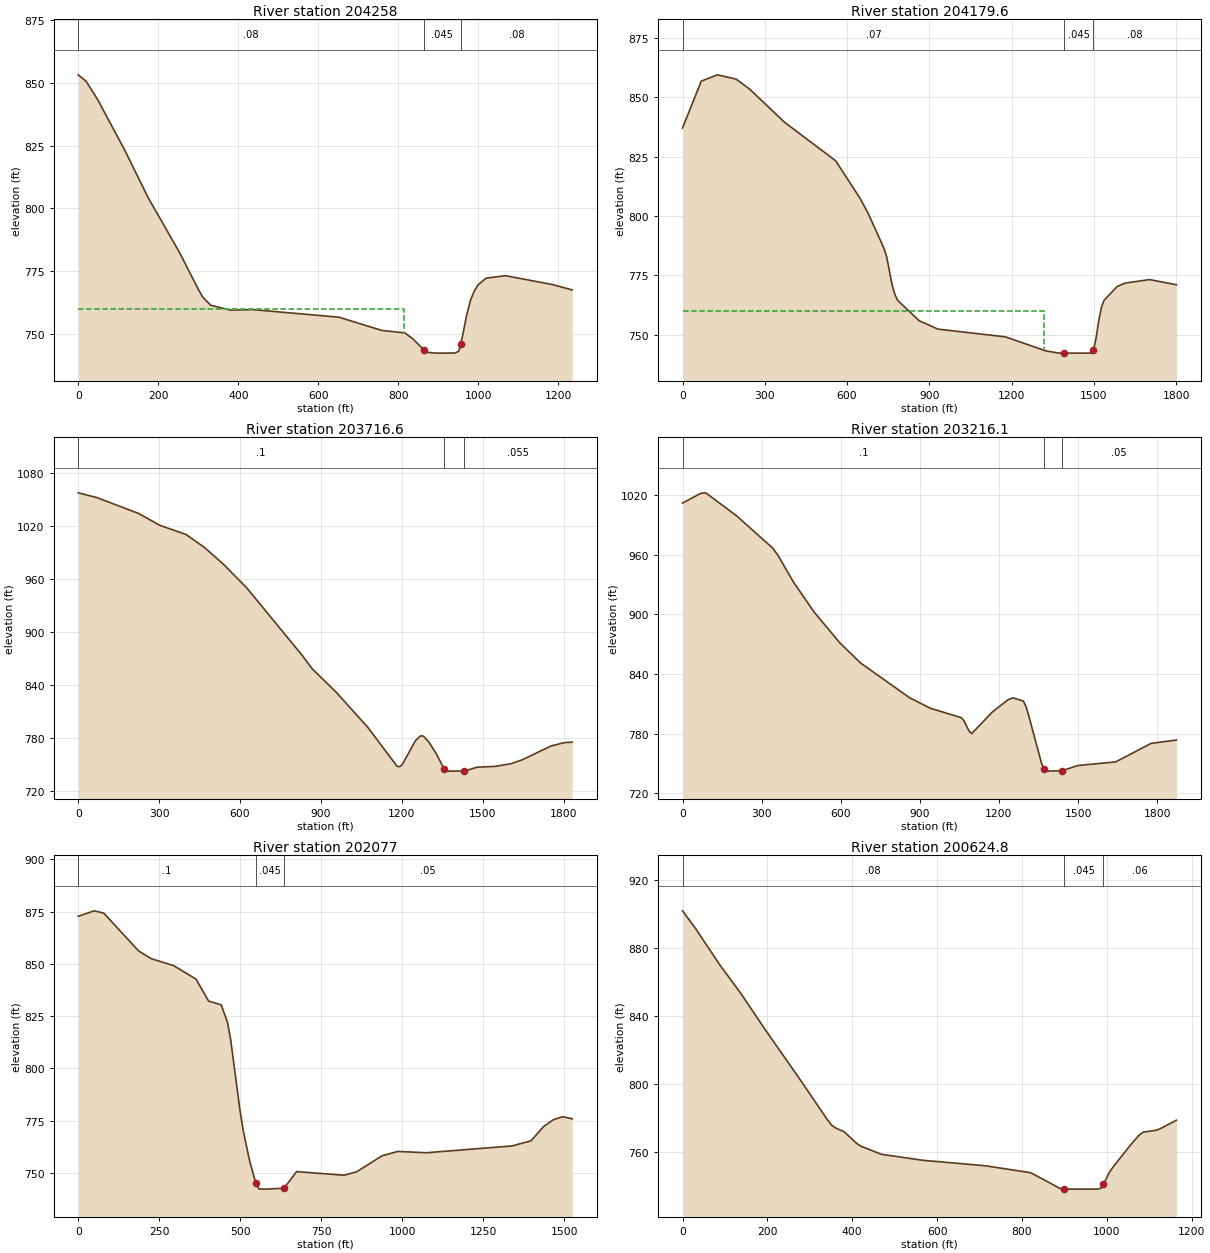
Type RM Length L Ch R = 1 ,204258  ,78.2,78.4,78.2
XS GIS Cut Line= 4
     1563736.013      235276.429     1563150.075      234794.659
     1562928.721      234699.172     1562694.346      234681.811
#Sta/Elev= 30
       0  853.28    19.4  850.78    48.6  843.41   116.7  823.11     175  804.22
   252.9  782.52   301.5  767.35   311.2  764.66   330.7  761.42   379.3  759.46
   437.6  759.64   651.6  756.63   758.6  751.36   816.4  750.36   835.7  748.12
   864.6  743.49   874.3   742.6   893.6   742.3   941.8  742.34   951.4   743.1
  955.73745.9167   961.1  749.41   970.7  757.32   980.4  763.31     990  767.07
   999.6  769.54  1019.2  772.17  1068.2  773.18  1185.7  769.63  1234.7  767.51
#Mann= 3 , 0 , 0
       0     .08       0   864.6    .045       0  955.73     .08       0
#XS Ineff= 2 , 0
          814.72  759.71
Permanent Ineff=
       F       F
Bank Sta=864.6,955.73
XS Rating Curve= 0 ,0
Exp/Cntr=0.3,0.1

Type RM Length L Ch R = 1 ,204179.6,475,463,451.4
XS GIS Cut Line= 5
     1564168.304       235597.61     1563630.309      235096.617
     1563174.381      234721.742     1562953.027      234626.256
     1562718.652      234608.895
#Sta/Elev= 30
       0  837.12    68.6  856.88   127.4  859.52     196  857.69     245   853.5
   372.5  839.51   558.7  823.32   646.9  807.63   676.3  801.41   735.1  786.37
     745  782.73   764.6  770.97   774.5  767.06   784.3  764.58     863  755.96
   931.9   752.4  1177.8  749.15  1325.4  743.23  1373.6   742.3  1392.9  742.31
  1489.3   742.3    1499  743.47  1508.6   748.7  1518.2  755.97  1527.9  761.55
  1537.5  764.54    1586  770.42  1615.4  771.81  1703.6  773.28  1801.5  771.08
#Mann= 3 , 0 , 0
       0     .07       0  1392.9    .045       0    1499     .08       0
#XS Ineff= 2 , 0
         1317.73     760
Permanent Ineff=
       F       F
Bank Sta=1392.9,1499
XS Rating Curve= 0 ,0
Exp/Cntr=0.3,0.1

Type RM Length L Ch R = 1 ,203716.6,519,500.5,482
XS GIS Cut Line= 5
     1564504.242      234609.763      1563642.03      234327.746
     1563261.821      234228.788     1563074.321      234249.621
     1562736.881      234312.888
#Sta/Elev= 30
       0 1057.93    68.3 1052.64   224.4 1034.48   302.4 1021.12   399.9 1010.64
   468.2  995.95   536.5  977.53   624.3  950.42   829.1  874.16   868.1  858.23
   956.3  831.96  1074.1  791.94  1182.2  747.95    1192  747.31  1201.8  749.65
  1250.9  776.98  1270.6  782.48  1280.4  781.92    1300  775.48  1328.3  761.85
  1356.6  745.06  1366.1   742.3  1432.1  742.38  1479.3   746.7  1547.6  747.73
  1606.4   750.8  1645.6  754.98  1753.5  770.79  1802.6  774.62    1832  775.12
#Mann= 3 , 0 , 0
       0      .1       0  1356.6    .045       0  1432.1    .055       0
#XS Ineff= 2 , 0
         1314.38  767.65
Permanent Ineff=
       F       F
Bank Sta=1356.6,1432.1
XS Rating Curve= 0 ,0
Exp/Cntr=0.3,0.1

Type RM Length L Ch R = 1 ,203216.1,1167.5,1139.1,1110
XS GIS Cut Line= 4
     1563722.992      232693.096     1562976.464      233724.346
     1562841.047      233904.902     1562663.964      234234.763
#Sta/Elev= 30
       0 1011.75    68.6 1021.42    88.1 1022.04   205.6  998.86   342.8  966.28
   362.3  959.11   421.1  932.24   499.4  902.14   597.4  871.02   675.7  850.94
   861.8  815.95   940.1   805.5  1057.6  795.98  1067.4  792.99    1087   782.4
  1096.8  779.99  1175.2  801.78  1233.9  813.95  1253.5  815.93  1292.7  812.74
  1302.5  807.38  1312.4   798.8  1361.4   750.4  1371.2  744.21    1381   742.3
  1439.9  742.67  1498.8  747.92  1642.8  751.55  1777.2   770.2  1873.2  773.57
#Mann= 3 , 0 , 0
       0      .1       0  1371.2    .045       0  1439.9     .05       0
Bank Sta=1371.2,1439.9
XS Rating Curve= 0 ,0
Exp/Cntr=0.3,0.1

Type RM Length L Ch R = 1 ,202077  ,1475.6,1452.2,1429
XS GIS Cut Line= 4
     1561554.589      233027.297     1561793.304      233326.777
     1562001.638      233556.811     1562483.409      234233.895
#Sta/Elev= 30
       0  872.78    49.1  875.39    78.6  874.32   186.6  856.17   225.9  852.48
   294.6  849.18   363.3  842.76   402.4  832.23   441.2  830.43   460.6  822.06
   470.3  813.91   499.4  779.67   509.1  770.36   528.5  756.06   547.8  745.18
   557.6  742.38     577   742.3   635.1  742.74   673.9  750.68   820.4  748.94
   859.5  750.61   937.7  758.25   986.6  760.33  1074.6   759.7  1338.6  762.95
  1397.2  765.39  1436.3  772.23  1465.7  775.45    1495  776.93  1524.3  775.92
#Mann= 3 , 0 , 0
       0      .1       0   547.8    .045       0   635.1     .05       0
Bank Sta=547.8,635.1
XS Rating Curve= 0 ,0
Exp/Cntr=0.3,0.1

Type RM Length L Ch R = 1 ,200624.8,627.8,641.2,654.4
XS GIS Cut Line= 3
     1561715.179      234207.853     1562266.395      234815.492
     1562609.277      234793.791
#Sta/Elev= 30
       0  901.78    29.3  891.94    87.9  870.06   136.7  853.59   195.3  831.95
   273.5  804.09   341.8  779.12   351.6     776   361.4   774.3   380.9  772.17
   410.2  765.38     420  763.75   468.8  758.93   566.5  755.41     713  752.22
   820.4  748.15   889.1  739.01   898.9  738.55   908.8   738.5   977.5   738.5
   987.3  739.15  991.98741.3372  1006.9  748.76  1016.7  752.14    1056  764.46
  1075.6  770.02  1085.4  771.95  1114.9  772.97  1124.7  773.82    1164  778.94
#Mann= 3 , 0 , 0
       0     .08       0   898.9    .045       0  991.98     .06       0
Bank Sta=898.9,991.98
XS Rating Curve= 0 ,0
Exp/Cntr=0.3,0.1

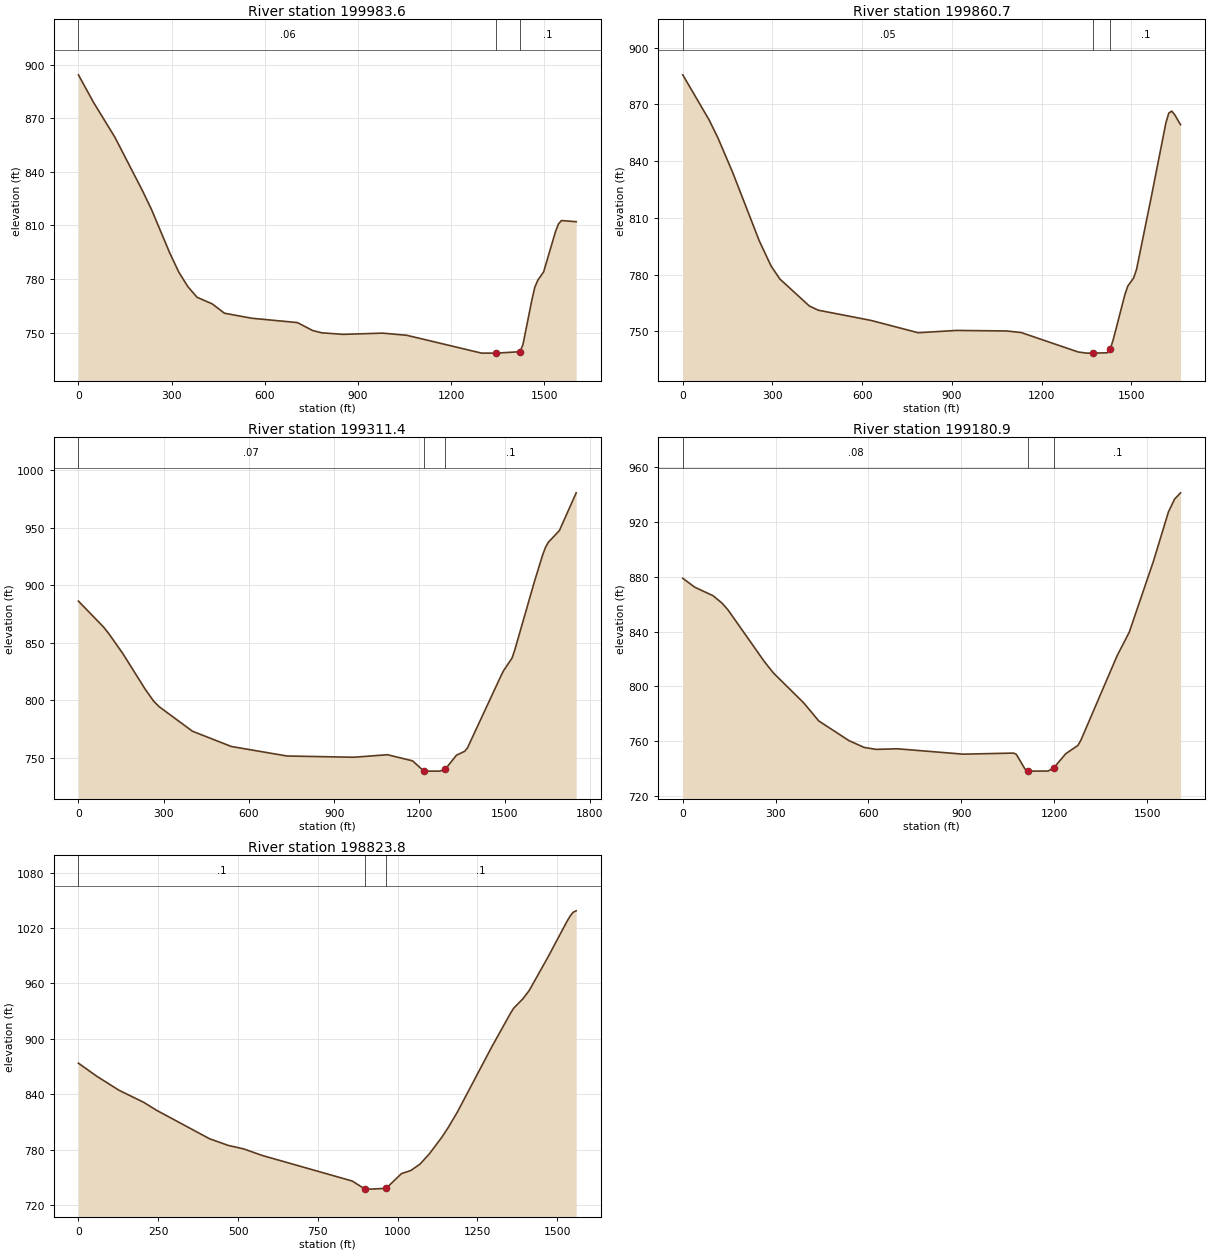
Type RM Length L Ch R = 1 ,199983.6,107.8,122.9,138
XS GIS Cut Line= 4
     1561670.909      234250.388     1562264.659      235219.138
     1562368.825      235411.846     1562582.367      235536.846
#Sta/Elev= 30
       0  894.25      49  878.72   117.5   859.3   205.7  829.58   235.1  818.96
   293.8  794.67   323.2  783.84   352.6  775.66     382  769.75     431  766.04
   470.2  760.83   558.3  758.02   705.2  755.59   754.2  751.14   783.6  749.87
   852.2     749   979.5  749.69  1057.9  748.46  1298.1   738.5  1345.8   738.5
  1421.9  739.29  1431.4  743.36    1460  768.21  1469.5  775.37    1479  779.28
    1498  784.02  1536.1  806.53  1545.6  810.76  1555.1   812.7  1602.7  812.05
#Mann= 3 , 0 , 0
       0     .06       0  1345.8    .045       0  1421.9      .1       0
Bank Sta=1345.8,1421.9
XS Rating Curve= 0 ,0
Exp/Cntr=0.3,0.1

Type RM Length L Ch R = 1 ,199860.7,521.5,549.3,577.1
XS GIS Cut Line= 4
     1561660.492      234286.846     1562210.839      235298.131
     1562301.985      235476.082     1562419.172      235766.881
#Sta/Elev= 30
       0  885.64    88.6  861.68   118.1  852.14   167.3  833.88   255.8  797.91
   295.2  784.62   324.7   777.7   423.1  763.46   452.7  761.22   629.8  755.79
   787.2  749.28   915.2   750.5  1082.4  750.22  1131.7  749.39  1322.7   739.1
  1351.3   738.5  1370.9   738.5  1419.9  738.67  1429.6  740.61  1439.4  745.42
  1478.6  769.36  1488.4  773.94    1508  778.26  1517.8  782.83  1566.8   820.9
  1615.8  860.21  1625.6  865.42  1635.4  866.45  1645.2  864.58  1664.8  859.27
#Mann= 3 , 0 , 0
       0     .05       0  1370.9    .045       0  1429.6      .1       0
Bank Sta=1370.9,1429.6
XS Rating Curve= 0 ,0
Exp/Cntr=0.3,0.1

Type RM Length L Ch R = 1 ,199311.4,132.9,130.5,128.1
XS GIS Cut Line= 5
     1561639.659      234297.263     1561936.534      235000.388
     1561863.617      235406.638     1561733.409      235521.221
     1561431.325      235786.846
#Sta/Elev= 30
       0  886.22    88.1  863.75   107.6  857.68   156.6  840.43   234.8  809.61
   264.2  799.28   283.8  794.36   401.2  772.94   538.2  759.65   733.9  751.37
   969.6  750.29  1087.5  752.48    1176  747.15  1214.5  738.43  1224.2   738.2
  1272.3   738.2  1291.6  740.01  1330.2  752.06  1359.2  755.43    1369  758.38
  1486.8  821.03  1496.6  825.86    1526  836.64  1535.8  843.84  1604.5  903.04
  1633.9  926.59  1643.8   933.1  1653.6   937.4  1692.8  947.73  1751.7   980.5
#Mann= 3 , 0 , 0
       0     .07       0  1214.5    .045       0  1291.6      .1       0
Bank Sta=1214.5,1291.6
XS Rating Curve= 0 ,0
Exp/Cntr=0.3,0.1

Type RM Length L Ch R = 1 ,199180.9,365.6,357.2,348.8
XS GIS Cut Line= 5
     1561542.436      234317.228     1561811.534      235050.735
     1561781.152      235298.131     1561655.284       235437.02
      1561348.86      235678.339
#Sta/Elev= 30
       0  878.89    39.1  872.34    97.7   866.2     127  860.76   146.5  855.72
   263.7  818.08     293  809.78   390.7     788   439.5   774.8   537.2  760.42
     586  755.49     625  754.07   693.4   754.5   905.9  750.58    1068  751.36
  1077.4  750.53  1105.5  739.72  1114.9  738.57  1133.7   738.2  1180.5  738.27
  1199.3  740.79  1237.5  750.96  1276.5  756.97  1286.3  760.85  1403.3  822.45
  1442.3  839.53  1520.3  891.22    1569  927.33  1588.5  936.55    1608  941.24
#Mann= 3 , 0 , 0
       0     .08       0  1114.9    .045       0  1199.3      .1       0
Bank Sta=1114.9,1199.3
XS Rating Curve= 0 ,0
Exp/Cntr=0.3,0.1

Type RM Length L Ch R = 1 ,198823.8,1303.7,1318.8,1333.8
XS GIS Cut Line= 4
     1561498.166      234313.756     1561461.707      235006.464
     1561321.082      235365.839     1561003.374      235725.214
#Sta/Elev= 30
       0  873.58    58.6  859.16     127  844.28   205.2  831.03   244.2  822.66
   410.3  791.76     469   784.5   517.8  780.66   576.4  773.52   857.7  745.87
   896.3  737.39   915.6   737.1   963.8  737.94    1012  753.95    1041  757.25
  1069.9   764.2  1099.2   775.3  1138.3   793.3  1157.9   803.6  1187.3  820.82
  1294.9  891.36  1353.7  927.84  1363.5  933.22  1392.8  943.55  1412.4  952.56
  1471.2  988.82  1529.9 1026.99  1539.7 1032.72  1549.5 1037.14  1559.2  1038.7
#Mann= 3 , 0 , 0
       0      .1       0   896.3    .045       0   963.8      .1       0
Bank Sta=896.3,963.8
XS Rating Curve= 0 ,0
Exp/Cntr=0.3,0.1