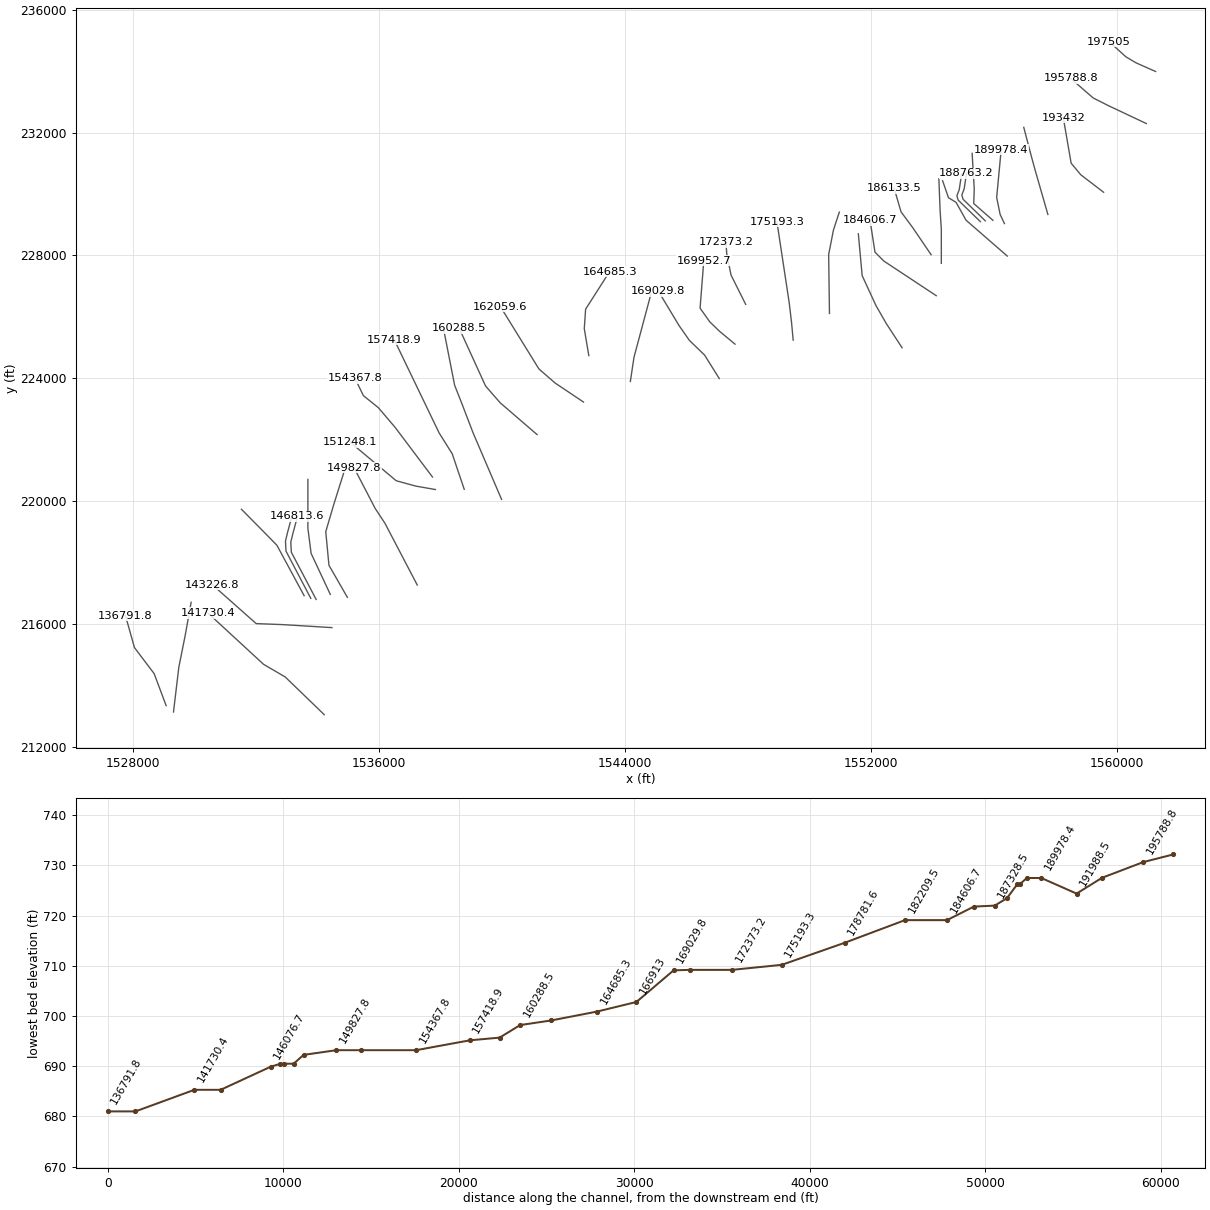
HEC-RAS study SFHGHSRV.prj: SFHGHSRV

--- SFHGHSRV.g01 (geometry) --- (continued)

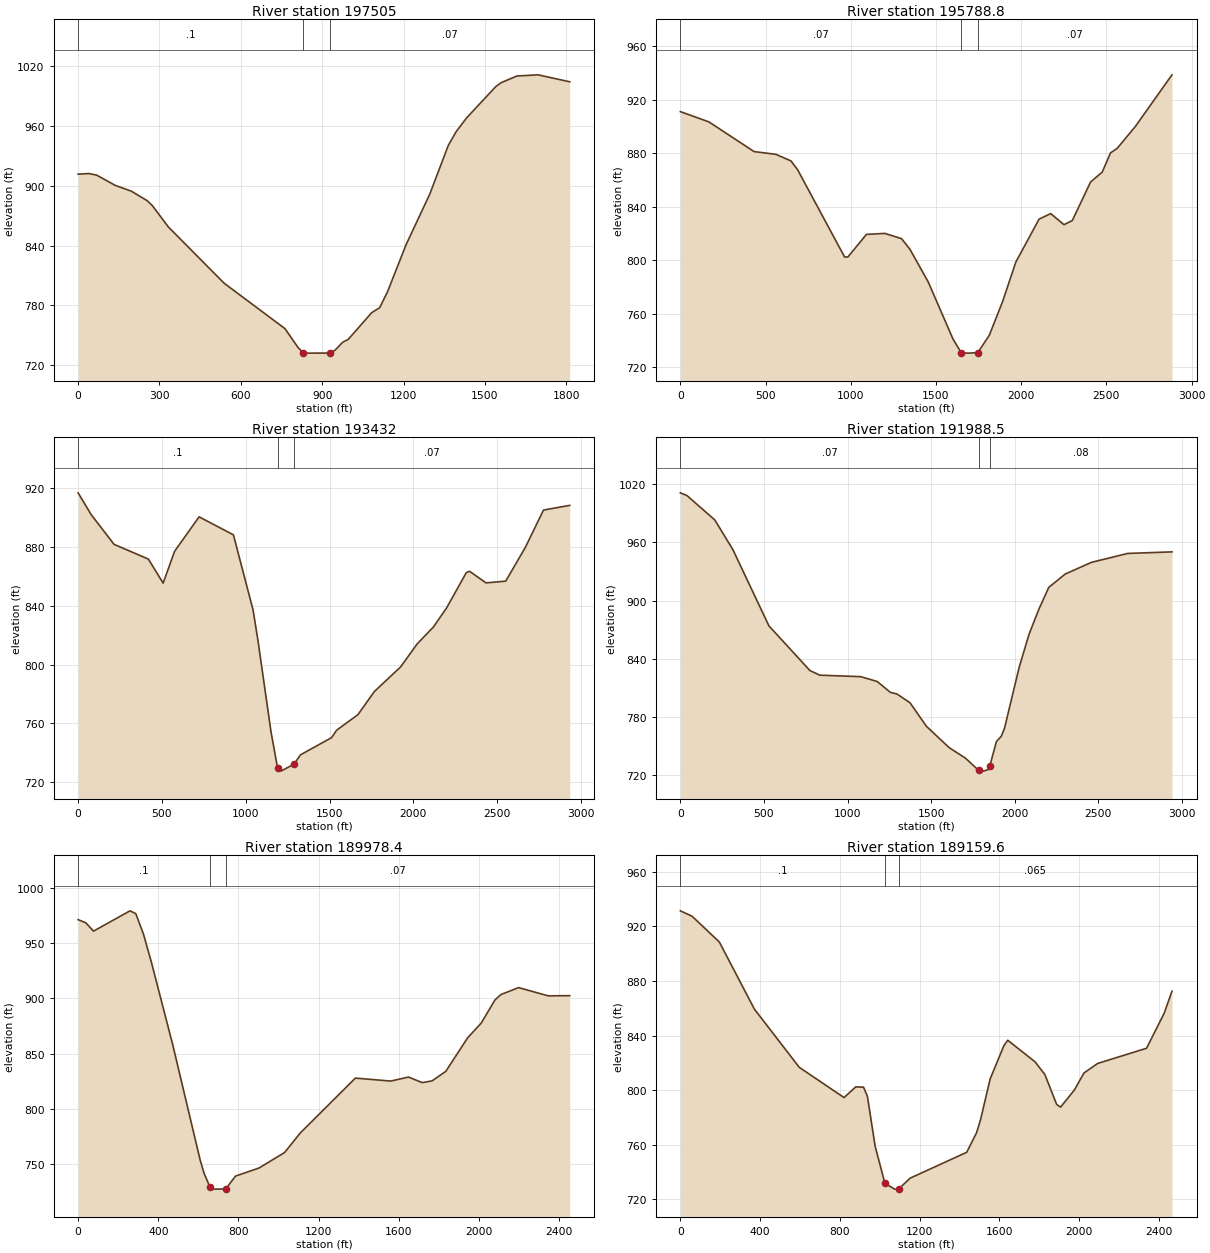
Type RM Length L Ch R = 1 ,197505  ,1714.1,1716.2,1718.3
XS GIS Cut Line= 4
     1561263.791      233985.631     1560628.374      234266.881
     1560295.041      234464.797     1559753.374      234954.381
#Sta/Elev= 30
       0  911.65    39.2  912.26    68.5  910.67     137  900.38   195.7  894.66
   254.5  885.09     274  880.01   332.8  858.68   538.3  802.32   762.7  756.77
   811.2  737.74   830.6  732.39   840.2   732.2   927.5  732.26   946.9  735.05
   975.9  743.19   995.3  745.79  1082.5  772.75  1111.8  777.75    1141  793.82
  1209.1  840.84  1296.7  891.68  1364.9  940.43  1394.1  954.35    1433  968.24
  1540.1  999.47  1559.6 1003.34    1618 1010.07  1695.8 1011.24  1812.7 1004.25
#Mann= 3 , 0 , 0
       0      .1       0   830.6    .045       0   927.5     .07       0
Bank Sta=830.6,927.5
XS Rating Curve= 0 ,0
Exp/Cntr=0.3,0.1

Type RM Length L Ch R = 1 ,195788.8,2367.2,2356.8,2346.3
XS GIS Cut Line= 4
     1560959.971      232292.922      1559723.86      232876.256
     1559230.804      233126.256     1558501.638        233758.2
#Sta/Elev= 30
       0  911.18   167.2  903.53   432.7   881.3   560.5  879.26     649  874.33
   688.3  867.69   963.7  802.52   983.3  802.56  1091.5  819.39  1199.7  820.17
    1298  816.22  1347.2  808.26  1454.1  783.95  1599.6  741.24  1648.1  730.99
  1686.9  730.67  1745.1  730.96    1813   744.1  1890.6  769.17  1968.4  798.73
  2104.8  830.82  2173.1  834.96    2251  826.67  2299.8  829.78    2407  858.58
  2475.2  865.97  2523.9  880.31  2562.9  883.69  2670.1  900.16  2884.6  938.68
#Mann= 3 , 0 , 0
       0     .07       0  1648.1    .045       0  1745.1     .07       0
Bank Sta=1648.1,1745.1
XS Rating Curve= 0 ,0
Exp/Cntr=0.3,0.1

Type RM Length L Ch R = 1 ,193432  ,1453,1443.6,1434.1
XS GIS Cut Line= 4
     1559571.082      230056.811     1558828.027      230626.256
     1558515.527      231001.256     1558258.582      232487.367
#Sta/Elev= 30
       0  916.83      78  901.99   214.5  881.77   419.3  871.75   507.1   855.4
   575.4  877.05   721.6  900.49   926.4  888.25  1043.6  837.12  1072.8  816.38
  1150.9  754.06    1190  729.57  1209.5  727.53  1287.6  732.23  1326.7  738.62
  1512.4  750.36  1541.8  755.34  1669.1  765.94  1767.1  781.68  1923.8  798.43
  2021.7  813.97  2119.6  825.61    2198  838.54  2315.5  862.57  2335.1  863.46
    2433  855.58  2550.5  856.75    2668  879.76  2775.8   905.1  2932.5  908.31
#Mann= 3 , 0 , 0
       0      .1       0    1190    .045       0  1287.6     .07       0
Bank Sta=1190,1287.6
XS Rating Curve= 0 ,0
Exp/Cntr=0.3,0.1

Type RM Length L Ch R = 1 ,191988.5,2011.3,2010,2008.5
XS GIS Cut Line= 4
     1557758.582      229334.589      1557348.86        230758.2
     1557209.971      231265.145      1556973.86      232167.922
#Sta/Elev= 30
       0 1011.17    39.2  1008.4     206  983.22   313.9  952.73   529.8  874.03
     775  828.02   833.9  823.27  1079.2  821.73  1177.3  816.74  1255.8   805.6
    1295  803.91  1373.5  794.87  1471.6  770.59  1607.9  748.56  1705.3  737.74
  1783.2  725.28  1812.4  724.39  1841.6  726.01  1851.3  730.07  1890.2  754.86
  1919.4  760.28  1938.9  768.74  2026.7  831.68  2085.6  865.54  2144.5  891.36
  2203.5  913.74  2301.7  927.47  2458.9  939.55    2675   948.7  2940.2  950.33
#Mann= 3 , 0 , 0
       0     .07       0  1783.2    .045       0  1851.3     .08       0
Bank Sta=1783.2,1851.3
XS Rating Curve= 0 ,0
Exp/Cntr=0.3,0.1

Type RM Length L Ch R = 1 ,189978.4,823.5,818.9,813.7
XS GIS Cut Line= 4
     1556343.652       229039.45     1556204.763      229334.589
     1556091.916      229890.145     1556239.485      231443.964
#Sta/Elev= 30
       0  971.18    38.4  968.33    76.8  960.79     259  979.16   287.8  976.63
   326.2  958.11   365.3  933.02   472.8  857.68   609.6  753.49   629.2  741.59
   658.5  729.25   678.1   727.5   736.7  727.63   785.6  739.28   902.9  746.59
  1030.5  760.58    1109  778.29  1383.9  827.89  1560.6  825.21    1649  828.84
  1717.7  823.81  1766.8  825.39  1835.5  834.03  1943.4  864.13  2012.2  877.67
  2080.9  898.59  2110.3  903.44  2198.7  909.74  2345.9   902.3  2453.9  902.43
#Mann= 3 , 0 , 0
       0      .1       0   658.5    .045       0   736.7     .07       0
Bank Sta=658.5,736.7
XS Rating Curve= 0 ,0
Exp/Cntr=0.3,0.1

Type RM Length L Ch R = 1 ,189159.6,404.4,396.3,388.9
XS GIS Cut Line= 4
     1555970.388      229143.617     1555345.388      229690.492
     1555362.749      230167.922     1555293.304      231322.436
#Sta/Elev= 30
       0  931.46    58.6  927.51   195.4  908.62   371.3  859.42     596  816.78
   820.7   794.6   879.2  802.43   918.2  802.22   937.7  795.61   976.7  758.84
  1025.5  731.76  1074.2   727.5  1093.7  727.52  1152.2  735.55  1435.6   754.5
  1484.7  768.71  1504.3  777.97  1553.3  808.32  1621.9  832.57  1641.5  836.61
  1778.7  820.74  1827.7  811.43  1886.5  789.62  1906.1  787.59  1974.7     800
  2023.8  812.65  2092.4  819.62  2337.4  830.74  2425.6  856.39  2464.8  872.55
#Mann= 3 , 0 , 0
       0      .1       0  1025.5    .045       0  1093.7    .065       0
Bank Sta=1025.5,1093.7
XS Rating Curve= 0 ,0
Exp/Cntr=0.3,0.1

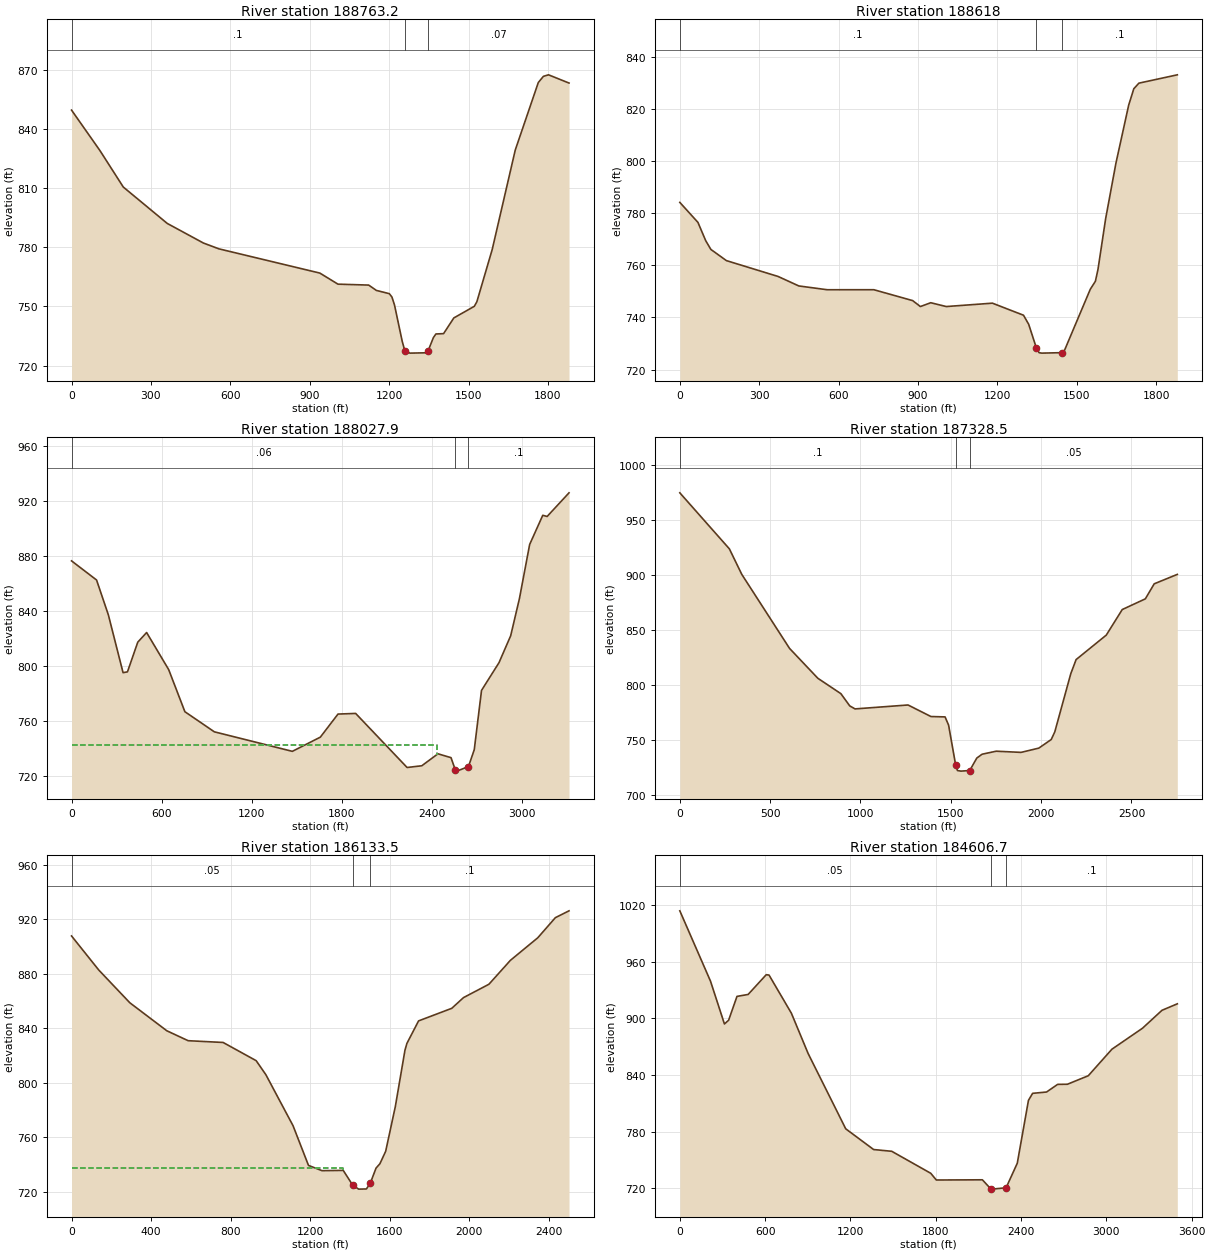
Type RM Length L Ch R = 1 ,188763.2,141.2,145.2,150.1
XS GIS Cut Line= 5
     1555722.124      229126.256     1554999.902      229827.645
     1554958.235      229966.534     1555034.624      230167.922
     1555111.013      230674.867
#Sta/Elev= 30
       0  849.81   107.5  829.21   195.5  810.72   361.6  792.22   498.5  782.24
   557.1  779.29   938.3  766.98  1006.8  761.35  1122.8  760.88  1151.8  758.17
  1200.7  756.52  1210.5  754.86  1220.3   750.8  1249.7  732.19  1259.4  727.47
    1279   726.3  1337.8  726.46  1347.6  727.58  1367.2  734.16  1376.8  736.03
  1405.8  736.21  1444.5  744.18  1521.9  750.09  1531.6  752.42  1589.6  778.99
  1676.7  829.54  1763.7  863.82  1783.1  866.98  1802.4  867.74  1879.8  863.56
#Mann= 3 , 0 , 0
       0      .1       0  1259.4    .045       0  1347.6     .07       0
Bank Sta=1259.4,1347.6
XS Rating Curve= 0 ,0
Exp/Cntr=0.3,0.1

Type RM Length L Ch R = 1 ,188618  ,565,590.2,611.8
XS GIS Cut Line= 5
     1555561.534      229100.214     1554839.311      229801.603
     1554797.645      229940.492     1554874.034      230141.881
     1554950.422      230648.825
#Sta/Elev= 30
       0  784.23    68.4  776.56    97.7  769.54   117.3  766.16   175.9  761.86
   371.4  755.76   449.6  752.12   557.1  750.66   733.1  750.67   879.7  746.49
     909   744.2   948.1  745.67  1006.8   744.2  1181.1   745.5  1298.6  740.87
  1318.2  737.38  1347.6   728.2  1357.4  726.47  1367.2   726.3  1444.5  726.48
  1454.2  727.52  1550.9  750.83  1570.3  753.92    1580  758.44    1609  777.97
  1647.7  799.22    1696  821.59  1715.4  827.91  1734.7  830.06  1879.8  833.26
#Mann= 3 , 0 , 0
       0      .1       0  1347.6    .045       0  1444.5      .1       0
Bank Sta=1347.6,1444.5
XS Rating Curve= 0 ,0
Exp/Cntr=0.3,0.1

Type RM Length L Ch R = 1 ,188027.9,719,699.4,682.2
XS GIS Cut Line= 5
     1556437.402      227980.422     1555097.124      229146.221
     1554771.603      229727.818     1554524.207      229879.728
     1554333.235      230430.943
#Sta/Elev= 30
       0  876.23   166.8  862.34   245.4  837.04   343.5  795.02   372.9  795.63
   441.6  817.19   500.5  824.18   647.7  797.24   755.7  766.66     952  752.05
  1472.1  737.87  1658.6  748.18  1776.4  764.95    1894  765.41    2237  726.14
    2335  727.39  2442.8  736.09  2529.9  733.28    2559   724.2  2568.6   723.5
  2646.1  726.82  2684.8  739.08  2733.2  782.15  2849.8   802.3  2927.6  821.86
    2986  848.88    3054  888.12  3141.5  909.34  3170.7   908.5  3316.5  925.66
#Mann= 3 , 0 , 0
       0     .06       0    2559    .045       0  2646.1      .1       0
#XS Ineff= 2 , 0
         2434.27   742.7
Permanent Ineff=
       F       F
Bank Sta=2559,2646.1
XS Rating Curve= 0 ,0
Exp/Cntr=0.3,0.1

Type RM Length L Ch R = 1 ,187328.5,1182.1,1194.9,1207.6
XS GIS Cut Line= 4
     1554291.568      227744.311     1554291.568      228841.534
     1554249.902      229494.311     1554211.707      230496.047
#Sta/Elev= 30
       0  974.46   274.3  923.63   342.9   900.5   607.4  833.32   764.1  806.21
   891.5  792.28   940.5  781.18   969.9  778.44  1263.2     782  1390.1  771.52
  1468.2  771.19  1487.7  763.79  1526.8  727.63  1536.6  722.56  1556.1     722
  1604.9  722.56  1643.9  733.86  1673.2  737.34  1751.3  740.08  1888.9     739
  1987.2  742.88    2056  750.69  2075.7  757.67  2164.1  810.39  2193.6  823.19
  2360.7  845.41  2449.1  868.59  2576.9  878.28    2626  891.93  2753.8  900.47
#Mann= 3 , 0 , 0
       0      .1       0  1526.8    .045       0  1604.9     .05       0
Bank Sta=1526.8,1604.9
XS Rating Curve= 0 ,0
Exp/Cntr=0.3,0.1

Type RM Length L Ch R = 1 ,186133.5,1524,1526.9,1529.8
XS GIS Cut Line= 4
     1553959.103      228024.693     1553354.936      228913.582
     1552979.936      229420.527     1552757.714      230184.416
#Sta/Elev= 30
       0  907.66   136.8  882.66   293.1   858.6   478.8  838.07   586.2  830.76
   762.1  829.46   928.2  816.09   977.1  805.77  1113.6  768.33  1191.2  739.21
  1259.1  735.34  1365.8  735.56  1414.3  724.53  1443.4   721.8  1482.2  721.92
  1501.6  726.02  1530.7  737.22  1550.1  740.42  1579.2  749.57  1627.7  782.38
  1676.2  823.81  1685.9  828.76  1744.6   845.3  1911.6  854.54  1970.5   862.4
  2098.2  872.19  2206.2  889.75  2343.8  906.31  2432.2  921.07  2500.9   926.1
#Mann= 3 , 0 , 0
       0     .05       0  1414.3    .045       0  1501.6      .1       0
#XS Ineff= 2 , 0
         1366.88  737.16
Permanent Ineff=
       F       F
Bank Sta=1414.3,1501.6
XS Rating Curve= 0 ,0
Exp/Cntr=0.3,0.1

Type RM Length L Ch R = 1 ,184606.7,2402.7,2397.1,2391.5
XS GIS Cut Line= 4
      1554125.77       226691.36     1552424.381       227816.36
     1552132.714      228108.027     1551972.992      229142.749
#Sta/Elev= 30
       0 1013.92   215.7  939.44   313.8  894.06   343.2  898.02     402  923.27
   480.5  925.33     608  946.29   627.6  945.84   784.5  905.51   902.2  862.86
  1166.9  783.01  1363.1  761.04  1490.6  759.18  1765.1  735.87  1804.3  728.76
  2128.1  728.98    2187  719.42  2196.8   719.1    2295  720.56  2373.6  746.54
  2452.2  813.14  2481.5  820.59  2579.4  821.97  2657.6  830.08  2726.2   830.2
  2872.9   839.2  3039.3  867.33  3254.5  889.57  3391.5  908.55  3499.2   915.4
#Mann= 3 , 0 , 0
       0     .05       0    2187    .045       0    2295      .1       0
Bank Sta=2187,2295
XS Rating Curve= 0 ,0
Exp/Cntr=0.3,0.1

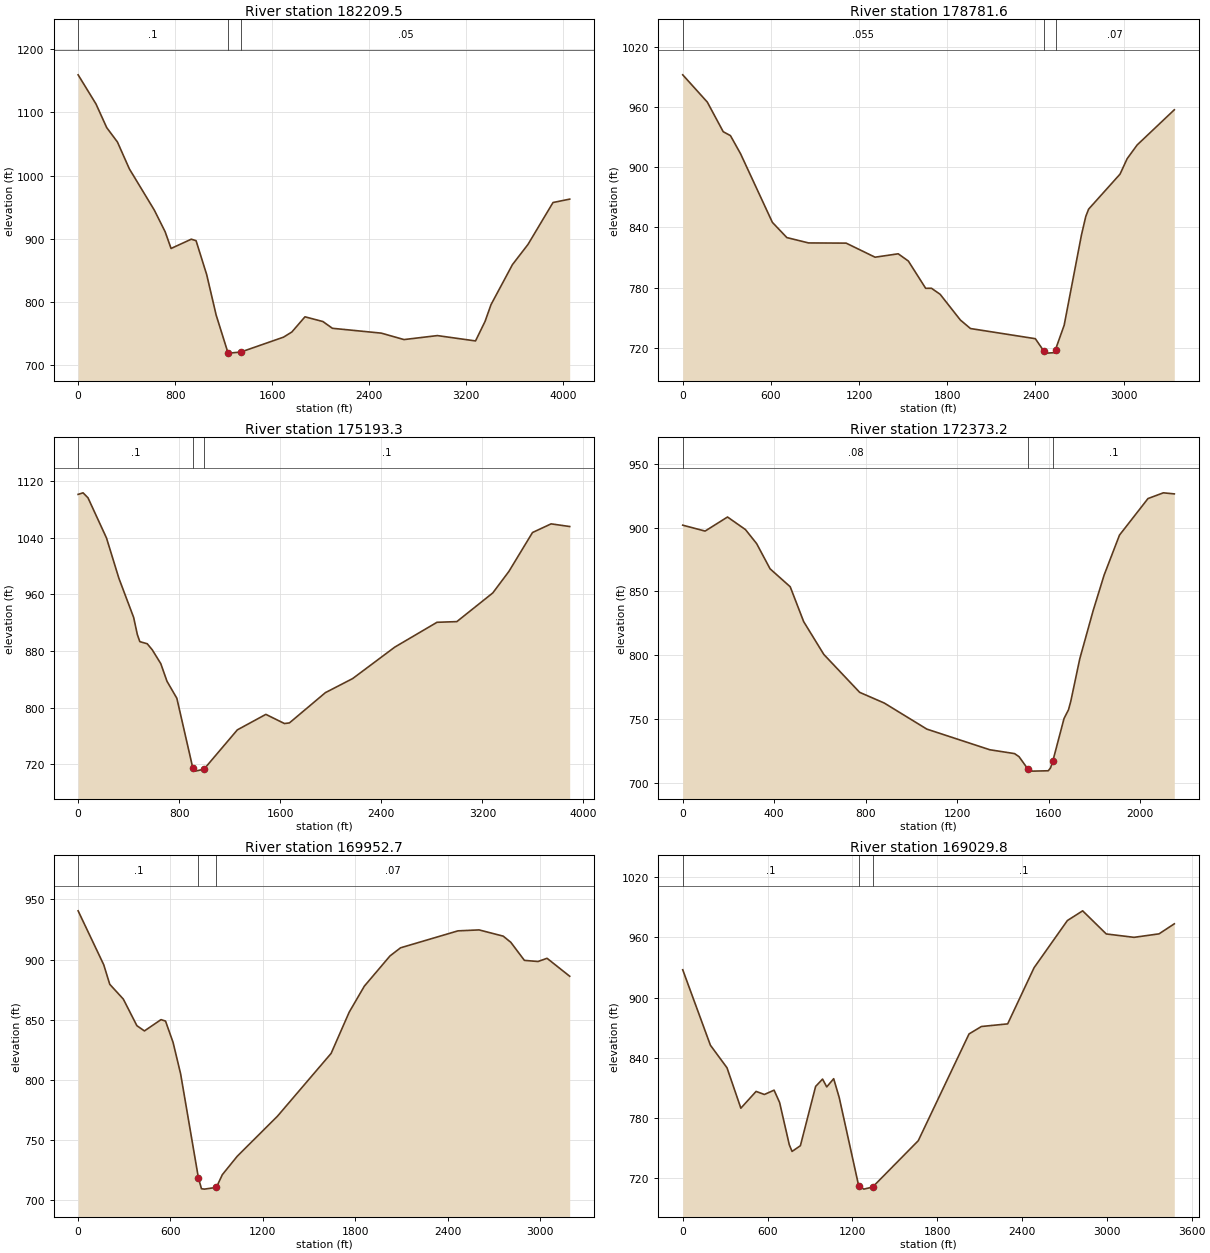
Type RM Length L Ch R = 1 ,182209.5,3443.2,3427.9,3412.4
XS GIS Cut Line= 5
     1553014.659      224996.916     1552493.825      225795.527
     1552160.492       226378.86     1551716.047      227344.138
     1551591.047      228705.249
#Sta/Elev= 30
       0 1159.27   147.4 1113.18   235.9 1075.76   324.4 1052.98   422.7 1010.53
   629.1  945.13   717.5  911.21   766.7  884.63   933.8  899.33   972.9  896.92
  1060.6   843.2  1138.4  779.46  1235.8  719.79  1245.6   719.1  1342.9  720.87
  1694.2  744.36    1763  752.52  1871.3  776.54  2018.9  769.07  2097.6  758.37
    2501  750.72    2688  740.53  2963.3  746.84    3278  738.39  3356.6  769.27
  3405.8  795.79  3582.8  859.16  3710.6  890.96  3917.2  957.31  4054.8  962.68
#Mann= 3 , 0 , 0
       0      .1       0  1235.8    .045       0  1342.9     .05       0
Bank Sta=1235.8,1342.9
XS Rating Curve= 0 ,0
Exp/Cntr=0.3,0.1

Type RM Length L Ch R = 1 ,178781.6,3581.4,3588.3,3595
XS GIS Cut Line= 4
     1550651.811      226113.235      1550625.77      228031.638
      1550782.02      228830.249     1550972.992      229411.846
#Sta/Elev= 30
       0  992.24   167.3  965.03   275.5  935.49   324.7   931.6   393.6  913.47
     610  845.05   708.4  829.87     856  824.53  1111.8  824.34  1308.6   810.3
    1466  813.69  1534.9   806.5  1652.9  779.26  1692.3  779.31  1751.3   773.3
  1889.1  747.61  1957.8  739.13    2399     729  2457.8  716.46  2477.4   714.6
  2526.4  715.04  2536.2  718.19  2595.1  742.39  2712.7  832.42    2742  850.85
  2761.5  858.24  2975.2  893.18  3023.8   908.6  3091.8  922.29  3344.5  957.36
#Mann= 3 , 0 , 0
       0    .055       0  2457.8    .045       0  2536.2     .07       0
Bank Sta=2457.8,2536.2
XS Rating Curve= 0 ,0
Exp/Cntr=0.3,0.1

Type RM Length L Ch R = 1 ,175193.3,2819.3,2820.2,2820.9
XS GIS Cut Line= 4
     1549471.256      225245.179     1549419.172      225809.416
     1549341.047      226469.138     1548941.742      229099.346
#Sta/Elev= 30
       0 1101.53    39.1 1103.73    78.2 1096.68   224.7 1039.83   322.4  983.07
   439.6  927.49   468.9  903.32   488.5   893.3   547.1  890.31   586.2  881.92
   654.6  862.12   703.4  837.31   781.6   813.2   908.6  714.08   928.1   710.2
   996.5  713.01  1260.4  768.54  1486.2  790.45  1633.4   777.5  1672.7  778.38
  1957.4  821.17  2173.4  841.09  2507.2  885.62  2840.9  920.66    2998  921.61
  3282.7  962.21  3410.3  992.66  3596.8 1047.59  3744.1 1059.83  3891.3 1056.08
#Mann= 3 , 0 , 0
       0      .1       0   908.6    .045       0   996.5      .1       0
Bank Sta=908.6,996.5
XS Rating Curve= 0 ,0
Exp/Cntr=0.3,0.1

Type RM Length L Ch R = 1 ,172373.2,2405.7,2420.5,2435.4
XS GIS Cut Line= 4
     1547926.117      226408.374     1547448.686      227363.235
     1547309.797      228057.679     1547283.756      228430.943
#Sta/Elev= 30
       0  901.84    97.9  897.22   195.9  908.24   274.2  898.41   323.2  887.42
     382  867.67   470.1   853.6   528.9  826.31     617  800.62   773.7  770.92
   881.5  762.52  1067.6  742.11    1343  725.94  1451.2  722.93  1470.8  720.52
  1510.2  710.67  1529.9   709.2  1598.7  709.48  1608.6  711.72  1618.4  716.96
  1667.6   750.4  1687.2  757.29  1697.1  763.85  1736.4  797.14    1795  834.93
  1842.9  862.74  1910.1  894.06  2034.8  922.69    2102  927.18  2149.9  926.35
#Mann= 3 , 0 , 0
       0     .08       0  1510.2    .045       0  1618.4      .1       0
Bank Sta=1510.2,1618.4
XS Rating Curve= 0 ,0
Exp/Cntr=0.3,0.1

Type RM Length L Ch R = 1 ,169952.7,922.1,922.8,923.5
XS GIS Cut Line= 5
     1547578.895      225114.971     1547066.742      225540.318
     1546754.242      225844.138     1546441.742      226286.846
      1546563.27      227831.985
#Sta/Elev= 30
       0  940.55   166.4  895.72   205.6  879.47   293.7  867.16   381.8  845.06
   430.8  840.72   538.5   850.1   567.8  848.91   616.8   831.2   665.8  805.09
     782  718.14   801.4  709.53   820.7   709.2   898.2  710.68   936.9  721.23
  1033.8  736.55  1295.1  769.84  1643.5  822.03  1761.2  856.37  1859.3  877.91
  2026.1  903.07  2094.7  909.81  2467.5   923.9  2604.8  924.69  2761.8  919.49
  2810.8  914.39  2899.1  899.37  2987.4  898.41  3046.2   901.1  3193.4  886.17
#Mann= 3 , 0 , 0
       0      .1       0     782    .045       0   898.2     .07       0
Bank Sta=782,898.2
XS Rating Curve= 0 ,0
Exp/Cntr=0.3,0.1

Type RM Length L Ch R = 1 ,169029.8,2138.8,2116.8,2094.6
XS GIS Cut Line= 5
     1547066.742      223995.179     1546589.311      224759.068
      1546094.52      225236.499     1545755.978       225722.61
     1545087.575      226833.721
#Sta/Elev= 30
       0  927.72   195.8  852.52   313.3  830.01   411.2  789.77     519  806.48
   577.7  803.42   646.2  807.73   685.4  795.42   753.9  753.28   773.5  746.67
   832.3  752.37   940.1  811.46   989.2  818.77  1018.7  810.99  1067.8  819.15
  1107.1  800.34  1244.6  712.51    1281   709.1  1342.8  711.11  1666.1  757.34
  2025.4  863.77  2112.8  871.17  2298.6  873.79  2485.3  929.74    2721  976.78
  2829.1  986.46  2996.1  963.41  3192.6  960.04  3369.4  963.51  3477.4  973.51
#Mann= 3 , 0 , 0
       0      .1       0  1244.6    .045       0  1342.8      .1       0
Bank Sta=1244.6,1342.8
XS Rating Curve= 0 ,0
Exp/Cntr=0.3,0.1

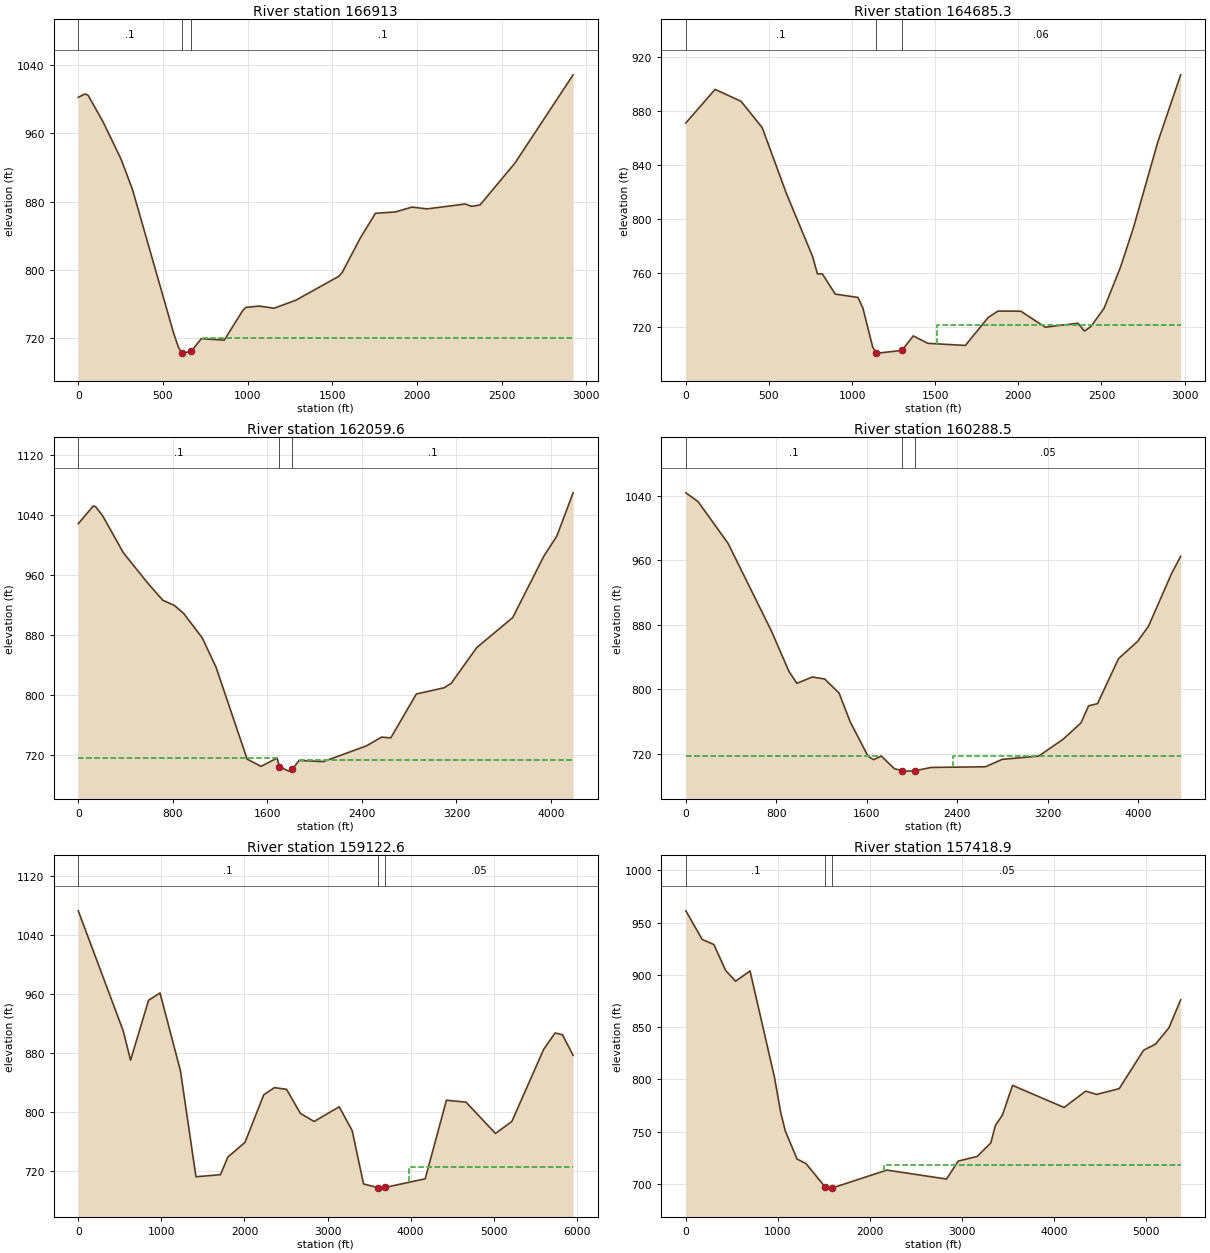
Type RM Length L Ch R = 1 ,166913  ,2233.7,2227.8,2255.6
XS GIS Cut Line= 4
     1544173.147      223901.386     1544253.009      224429.164
     1544291.203      224686.108     1544842.129      226742.243
#Sta/Elev= 30
       0 1001.85    38.8 1005.81    58.2 1004.24   145.6  973.46   252.3  929.83
   320.3     894   562.6  726.48   591.5  709.56   610.8  703.14   620.4   702.8
   668.5  705.14   726.2  719.67   862.2  718.04   970.1  752.29   989.7  756.28
  1068.2  757.82  1156.5  755.32    1284  764.57  1539.1  792.71  1558.7  797.14
  1666.6  837.75  1754.9  866.26  1872.6  867.85  1970.7  873.56    2059  871.44
  2284.6  877.14  2323.8  874.41  2372.9  876.12  2578.9  925.03  2922.2 1028.18
#Mann= 3 , 0 , 0
       0      .1       0   610.8    .045       0   668.5      .1       0
#XS Ineff= 2 , 0
                          736.07          720.28
Permanent Ineff=
       F       F
Bank Sta=610.8,668.5
XS Rating Curve= 0 ,0
Exp/Cntr=0.3,0.1

Type RM Length L Ch R = 1 ,164685.3,2613.8,2625.6,2638.5
XS GIS Cut Line= 4
      1542821.95      224741.707     1542674.381      225618.443
     1542717.784      226252.124     1543499.034      227476.082
#Sta/Elev= 30
       0  871.06   175.9  895.86   332.2  887.03   459.2  867.61   605.7  818.63
   762.1  772.44   791.4  759.52   820.7  759.55   898.8  744.53  1035.6  742.05
    1065  734.15  1123.6  705.55  1143.1   701.1  1152.9   700.9  1299.5  702.87
  1367.9  713.64  1455.8  708.14  1681.2  706.59  1818.6  727.28  1877.4  731.98
  2014.8  731.89    2162  720.06  2358.2  722.99  2397.4  717.22  2436.7  720.61
  2515.2     734  2613.3  764.04  2691.8  793.45  2838.9  857.04  2976.3  906.61
#Mann= 3 , 0 , 0
       0      .1       0  1143.1    .045       0  1299.5     .06       0
#XS Ineff= 2 , 0
                         1510.03          721.45
Permanent Ineff=
       F       F
Bank Sta=1143.1,1299.5
XS Rating Curve= 0 ,0
Exp/Cntr=0.3,0.1

Type RM Length L Ch R = 1 ,162059.6,1773.1,1771.1,1768.5
XS GIS Cut Line= 4
     1542648.339      223231.291       1541728.2       223847.61
     1541198.686      224307.679     1539948.686      226330.249
#Sta/Elev= 30
       0  1028.7   127.4 1052.25     147  1051.3   205.8 1039.29   382.2  989.82
     588  949.49   715.4   926.7   813.5  919.75   891.9  909.11  1048.7  876.64
  1165.9  837.43    1429  715.04  1545.9  705.51  1682.3  716.43  1701.8  705.25
  1779.7  699.12  1808.9  701.36  1867.9  713.29  2074.2  711.83  2437.7  732.73
  2565.5  744.42  2644.1  743.41  2860.2  801.82    3096   810.2    3155  816.06
  3371.1  863.64  3675.7  903.66    3941  985.95    4049 1012.13  4186.6 1069.76
#Mann= 3 , 0 , 0
       0      .1       0  1701.8    .045       0  1808.9      .1       0
#XS Ineff= 2 , 0
         1681.77  717.12 1877.68          713.62
Permanent Ineff=
       F       F
Bank Sta=1701.8,1808.9
XS Rating Curve= 0 ,0
Exp/Cntr=0.3,0.1

Type RM Length L Ch R = 1 ,160288.5,1174.8,1166,1157.5
XS GIS Cut Line= 4
     1541137.922      222172.263     1539940.006      223205.249
     1539462.575      223752.124       1538603.2      225635.804
#Sta/Elev= 30
       0 1043.64   108.1 1032.77   373.3  980.96   756.5   872.3   913.7  821.59
   982.5   807.2    1120  815.06  1228.1  812.55  1355.8   795.1  1454.1  759.45
  1611.2  716.93  1660.3  712.39  1728.9  716.95  1846.7  701.05  1915.3  698.92
  1944.8   698.2  2023.2  698.53  2170.4  702.79  2651.2  703.61  2798.4   712.8
  3122.2  716.86  3338.1  737.79  3495.1   757.9  3563.8  779.28  3642.3  781.93
  3828.7  837.94  3995.5  858.97  4093.6  878.12  4299.7  944.06  4378.2  964.74
#Mann= 3 , 0 , 0
       0      .1       0  1915.3    .045       0  2023.2     .05       0
#XS Ineff= 2 , 0
          1725.2  716.89 2367.12           717.4
Permanent Ineff=
       F       F
Bank Sta=1915.3,2023.2
XS Rating Curve= 0 ,0
Exp/Cntr=0.3,0.1

Type RM Length L Ch R = 1 ,159122.6,1699.7,1703.7,1707.5
XS GIS Cut Line= 5
     1539983.409      220062.888     1539054.589      222233.027
     1538698.686      223161.846     1538455.631      223778.166
     1538082.367      225679.207
#Sta/Elev= 30
       0  1072.5     541  909.92   629.5  870.35   845.9  951.38   983.6  961.29
  1229.4  856.05  1416.3  712.43  1711.4  715.25  1799.9   739.1  2006.5  759.03
  2232.7  823.54  2360.6   833.1  2506.8  830.84  2672.6  798.26  2838.4  787.32
  3140.7  807.17  3296.7  774.81  3433.2  702.73  3608.5  697.72    3628   695.7
  3696.2  698.13  4175.1  709.68  4430.8  816.06  4666.8  813.44  5020.8  771.13
  5217.5  787.23    5601     885  5738.7  907.14  5827.2   904.7  5955.1  876.85
#Mann= 3 , 0 , 0
       0      .1       0  3608.5    .045       0  3696.2     .05       0
#XS Ineff= 2 , 0
            3301  761.76 3983.28             725
Permanent Ineff=
       F       F
Bank Sta=3608.5,3696.2
XS Rating Curve= 0 ,0
Exp/Cntr=0.3,0.1

Type RM Length L Ch R = 1 ,157418.9,3042.1,3051.1,3059.4
XS GIS Cut Line= 4
     1538768.131      220392.749     1538377.506      221547.263
     1537952.159      222224.346     1536493.825       225253.86
#Sta/Elev= 30
       0  961.21   176.9   933.9   304.7  928.99   432.5  904.23   540.6  893.91
   697.9  903.76   963.2  802.25    1032  768.14  1081.2  750.88    1209  723.96
  1306.6  719.59  1511.3697.5839  1540.6  695.16  1589.4  696.18  2185.5  713.38
  2834.4  704.81  2962.2  721.99  3168.6  726.43  3316.1  739.34  3365.3  755.85
  3443.9  766.25  3552.1  794.37  4112.4  773.23  4348.4  788.85  4466.4   785.7
  4712.1  791.22  4977.6     828  5105.4  833.67  5252.8  849.35  5380.6  876.17
#Mann= 3 , 0 , 0
       0      .1       0  1511.3    .045       0  1589.4     .05       0
#XS Ineff= 2 , 0
                         2157.19          718.63
Permanent Ineff=
       F       F
Bank Sta=1511.3,1589.4
XS Rating Curve= 0 ,0
Exp/Cntr=0.3,0.1

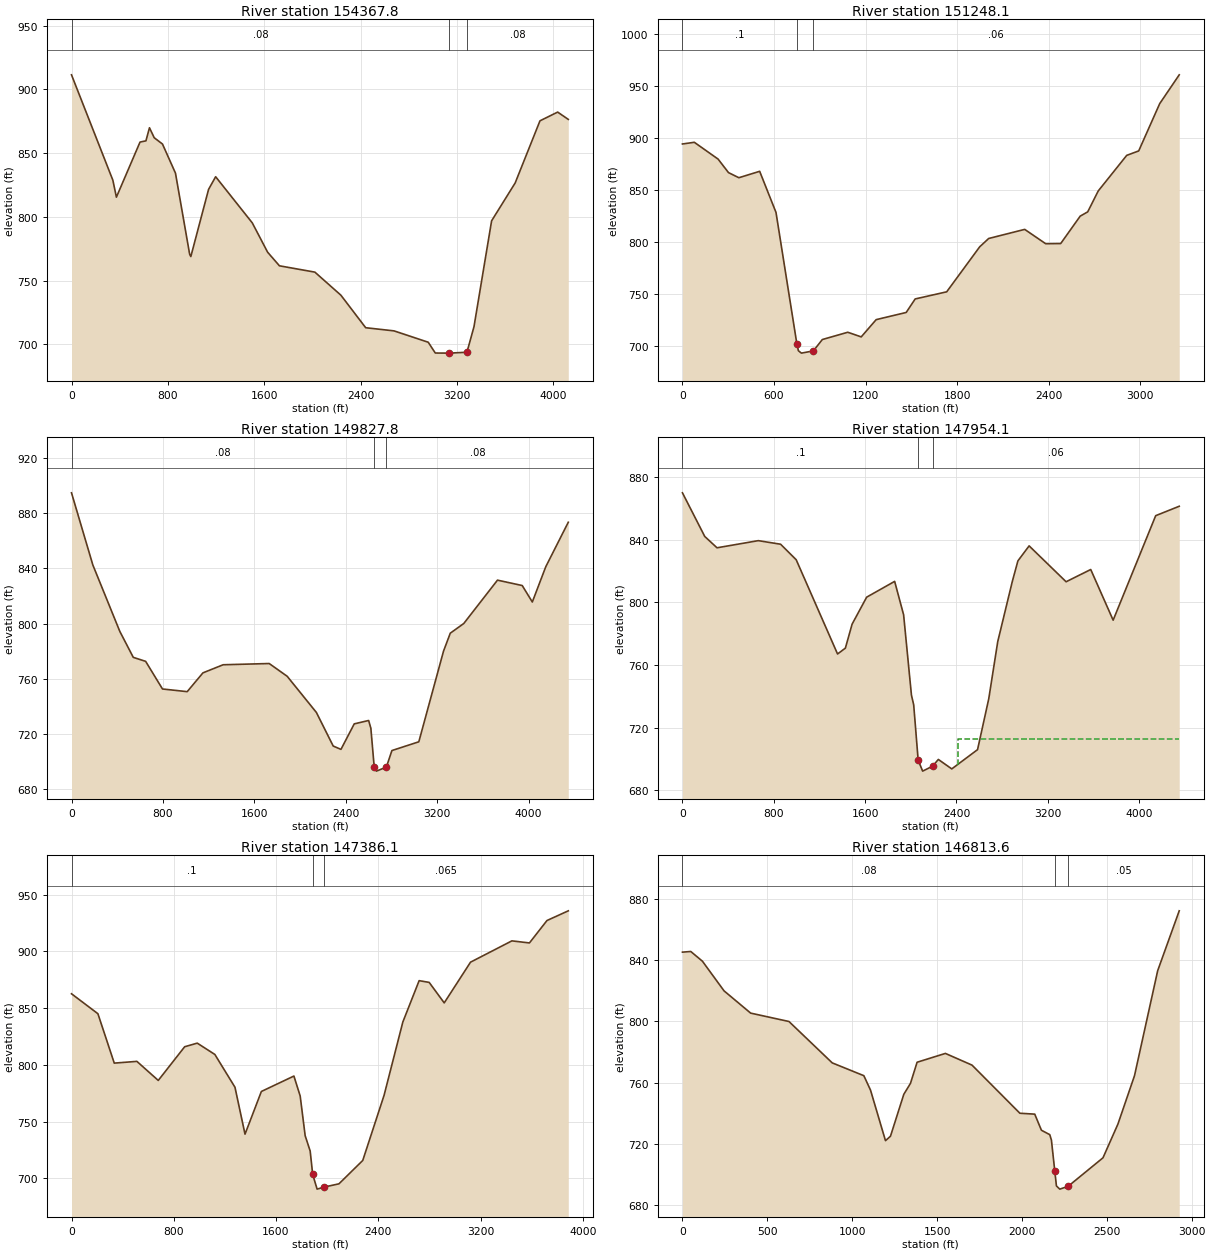
Type RM Length L Ch R = 1 ,154367.8,3109.9,3119.7,3129
XS GIS Cut Line= 5
     1537735.145      220792.054     1536519.867      222406.638
     1535972.992      223048.999     1535486.881      223439.624
     1535209.103      224012.541
#Sta/Elev= 30
       0   911.4   343.4  828.76   372.8  815.48     569  858.68     618  859.63
   647.4  869.89   686.7  862.09   755.4  857.13   863.3  834.31     981  770.72
   990.8  768.92    1138  821.56  1196.8   831.5  1500.9  795.34  1628.4  772.33
  1726.5  761.66  2020.8   756.7  2236.6  738.64  2442.6  713.12  2678.1  710.64
  2961.9  701.74  3020.4  693.28  3137.3   693.2  3283.4  693.89  3341.9  713.95
  3488.1  796.92    3684  826.66  3889.7  875.33  4036.6  882.18  4124.8  876.46
#Mann= 3 , 0 , 0
       0     .08       0  3137.3    .045       0  3283.4     .08       0
Bank Sta=3137.3,3283.4
XS Rating Curve= 0 ,0
Exp/Cntr=0.3,0.1

Type RM Length L Ch R = 1 ,151248.1,1436.8,1420.3,1403.9
XS GIS Cut Line= 4
     1537830.631      220384.068      1537188.27      220496.916
     1536554.589      220670.527     1535061.534      221920.527
#Sta/Elev= 30
       0  894.07    77.9  895.68   233.6  879.55   301.8  866.57   369.9  861.66
   506.2  867.81   613.3   828.3   750.3  701.82   760.1  695.49   779.7   693.2
   858.1  695.34     917  706.26  1083.7  713.24  1171.9   708.8    1270  725.37
  1466.6  732.25  1525.6  745.23  1732.1  752.08  1948.5   795.3  2007.5   803.3
  2243.5  812.04  2381.2  798.27  2479.5  798.44  2607.4  824.78  2656.6  828.87
  2725.4  848.93  2912.3  883.13  2990.9  887.41  3128.6  932.84  3256.5  960.48
#Mann= 3 , 0 , 0
       0      .1       0   750.3    .045       0   858.1     .06       0
#XS Ineff= 2 , 0
                         1083.58          713.23
Permanent Ineff=
       F       F
Bank Sta=750.3,858.1
XS Rating Curve= 0 ,0
Exp/Cntr=0.3,0.1

Type RM Length L Ch R = 1 ,149827.8,1885.4,1873.7,1861.6
XS GIS Cut Line= 4
     1537240.353      217276.429     1536187.836      219288.148
     1535873.166      219765.579     1535178.721      221100.214
#Sta/Elev= 30
       0  894.69   186.7  842.46   422.6  794.38   540.6  775.57   648.7  772.68
   796.1  752.67  1012.4  750.74    1150  764.35  1326.9  770.21  1729.8   771.1
  1887.1  761.87  2142.6  735.69  2289.8  711.37  2357.6  708.95  2473.9  727.42
  2599.9  729.86  2619.3  724.24  2648.4   696.4  2667.8   693.2    2755  696.12
  2803.5   708.1  3038.9  714.44  3255.2   780.1  3314.2  793.07  3432.2  800.08
  3727.2  831.47  3943.6  827.57    4032  815.65    4150  841.23  4346.7  873.39
#Mann= 3 , 0 , 0
       0     .08       0  2648.4    .045       0    2755     .08       0
#XS Ineff= 2 , 0
         2591.22  729.58
Permanent Ineff=
       F       F
Bank Sta=2648.4,2755
XS Rating Curve= 0 ,0
Exp/Cntr=0.3,0.1

Type RM Length L Ch R = 1 ,147954.1,566.3,567.9,570.1
XS GIS Cut Line= 5
     1534966.047      216877.124     1534367.089      217918.791
     1534262.922      219012.541     1534523.339      219897.957
     1534861.881      220974.346
#Sta/Elev= 30
       0  870.03   195.4  842.15   302.8  834.92   664.3  839.48   859.7   837.2
   996.4  827.28  1358.6  767.09  1427.2  770.83  1486.1  786.15  1613.6  803.38
  1858.8  813.46  1937.3  792.13    2006  740.76  2025.6   734.6  2064.8  699.24
  2104.1  692.26  2192.4  695.48  2241.4  699.73  2359.2  693.68    2585  705.99
  2683.2  738.51  2761.8  774.99  2889.4   813.4  2938.5  826.56  3036.7  836.14
  3360.6  813.22  3576.4  821.05  3772.7  788.69  4145.5  855.44  4351.6  861.45
#Mann= 3 , 0 , 0
       0      .1       0  2064.8    .045       0  2192.4     .06       0
#XS Ineff= 2 , 0
                         2410.64          712.84
Permanent Ineff=
       F       F
Bank Sta=2064.8,2192.4
XS Rating Curve= 0 ,0
Exp/Cntr=0.3,0.1

Type RM Length L Ch R = 1 ,147386.1,580.9,572.6,564.2
XS GIS Cut Line= 4
     1534410.492       216972.61     1533785.492      218309.416
     1533681.325      219125.388     1533681.325      220713.929
#Sta/Elev= 30
       0  862.58   206.6  845.01   334.5  801.49   511.6  803.03   678.8  786.25
   885.4  815.91   983.8   819.1  1121.5  809.13  1278.9  780.26  1357.6  738.91
  1485.5  776.52  1740.1   790.1  1789.1  772.57  1828.2  737.54  1867.4  724.02
    1887  703.46  1921.6   690.5  1975.1  692.27  2092.6  695.18  2278.7  715.75
  2445.4  773.09  2592.5  837.76  2719.9  874.12  2798.4   872.6  2916.1  854.55
    3122  890.42  3445.6  909.18  3582.8  907.34  3720.1   927.1  3886.8  935.64
#Mann= 3 , 0 , 0
       0      .1       0    1887    .045       0  1975.1    .065       0
Bank Sta=1887,1975.1
XS Rating Curve= 0 ,0
Exp/Cntr=0.3,0.1

Type RM Length L Ch R = 1 ,146813.6,177.2,177.3,177.2
XS GIS Cut Line= 5
     1533950.422      216807.679     1533143.131      218344.138
      1533125.77      218673.999     1533195.214      218960.457
     1533342.784      219507.332
#Sta/Elev= 30
       0  845.18      49  845.61   117.7  839.26   245.2   819.9     402  805.38
   627.6  799.91   882.5   772.9  1068.8  764.54  1108.1  755.14  1196.3  722.12
  1225.7  725.03  1304.2  752.37  1343.4   759.5  1382.6  773.32  1549.3  779.08
  1706.2  771.44  1988.2  740.03  2075.8  739.44  2115.1  728.94  2164.2  726.06
    2174  722.51  2193.7  702.47  2203.5  692.58  2223.2   690.5  2272.3  692.32
  2477.9  710.95  2565.8  732.94  2663.5  764.52  2800.2  833.11  2927.1  872.15
#Mann= 3 , 0 , 0
       0     .08       0  2193.7    .045       0  2272.3     .05       0
Bank Sta=2193.7,2272.3
XS Rating Curve= 0 ,0
Exp/Cntr=0.3,0.1

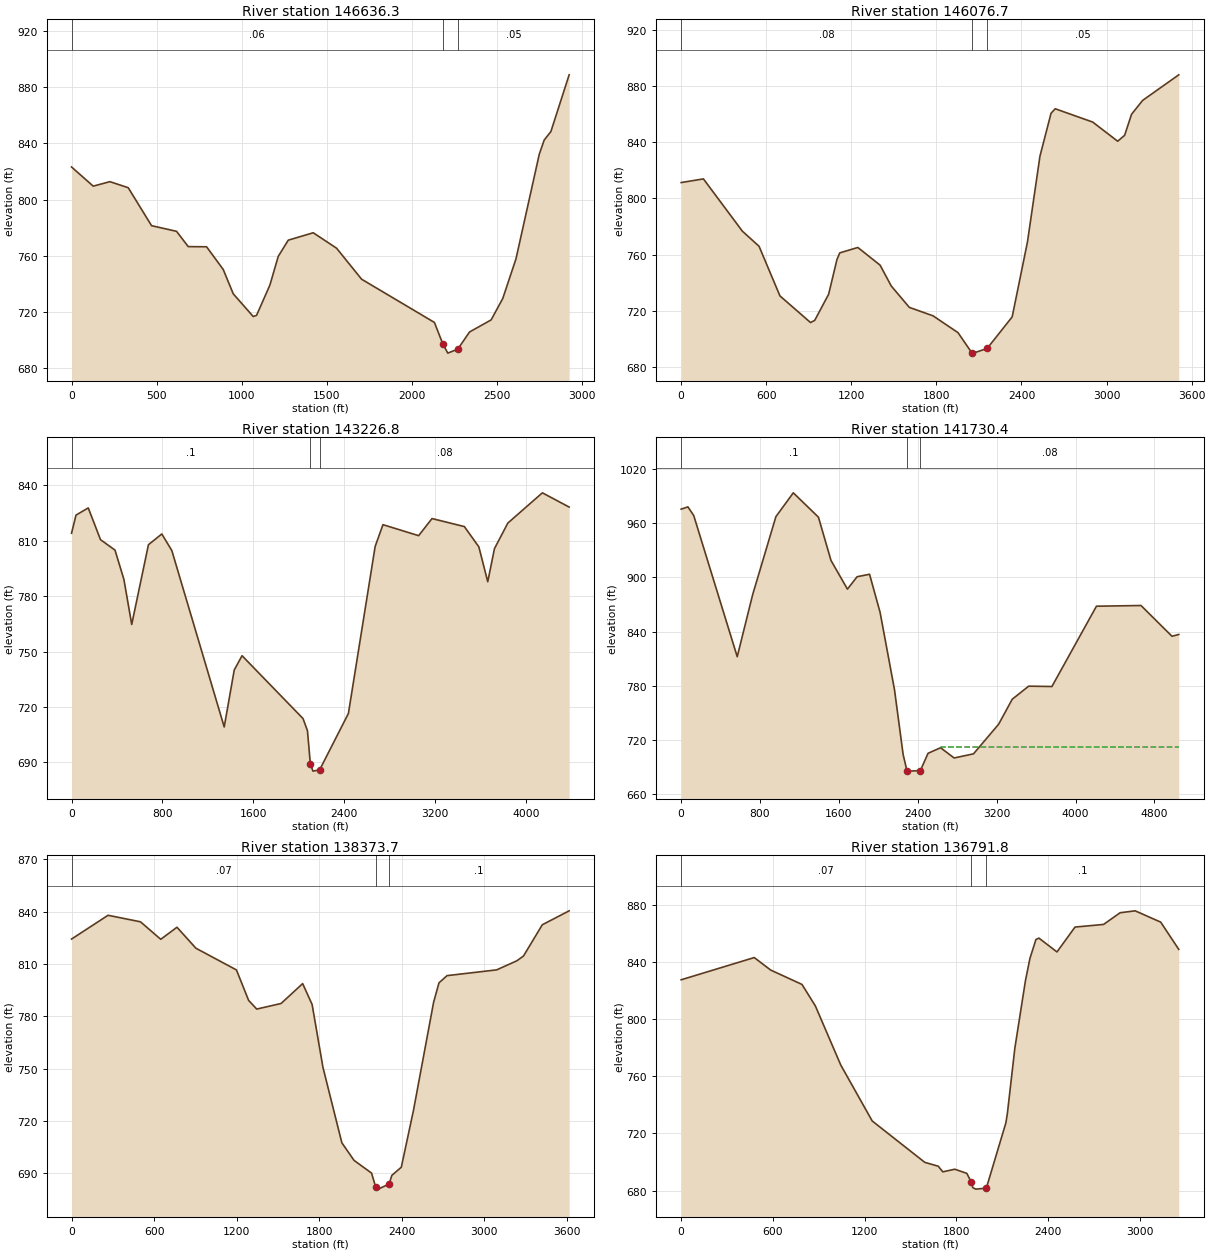
Type RM Length L Ch R = 1 ,146636.3,536.5,559.6,582.6
XS GIS Cut Line= 5
     1533776.811      216842.402      1532969.52       218378.86
     1532952.159      218708.721     1533021.603      218995.179
     1533169.172      219542.054
#Sta/Elev= 30
       0  823.22   127.5  809.55   225.5  812.76   333.4  808.45   470.7  781.38
   617.8  777.34   686.4  766.44   794.3  766.33   892.3  750.14   951.2   732.8
  1068.8   716.6  1088.4  717.44  1166.9  739.06  1215.9  759.48  1274.8  771.04
  1421.8  776.32  1559.1  765.31  1706.2  743.21  2134.7  712.37  2183.8  697.13
  2213.3   690.5  2272.3  693.38  2341.1  705.56  2468.1  714.18  2536.5  729.43
  2614.6   757.8  2751.4  832.32  2780.6  842.48  2819.7  848.47  2927.1  888.93
#Mann= 3 , 0 , 0
       0     .06       0  2183.8    .045       0  2272.3     .05       0
Bank Sta=2183.8,2272.3
XS Rating Curve= 0 ,0
Exp/Cntr=0.3,0.1

Type RM Length L Ch R = 1 ,146076.7,2876.8,2849.9,2890.7
XS GIS Cut Line= 4
     1533559.797      216929.207     1532674.381      218569.832
     1532318.478      218934.416     1531519.867      219741.707
#Sta/Elev= 30
       0  811.23     157  813.83   431.7  776.65   549.5  765.89   696.7  730.61
   912.5  711.65     942  713.21  1040.1  731.79    1099  756.56  1118.6   761.2
  1246.1  765.05  1403.1  752.48  1481.6  737.68  1609.2  722.44    1776  716.46
  1952.5  704.48  2050.5  690.06  2060.3   689.9  2158.2  693.24  2334.6  715.68
  2442.3  768.94  2530.4  829.97  2608.7  860.53  2638.1  863.72  2902.4  854.26
  3078.6  840.63  3127.6  844.83  3176.5  859.81  3254.8  869.68  3509.4  887.86
#Mann= 3 , 0 , 0
       0     .08       0  2050.5    .045       0  2158.2     .05       0
Bank Sta=2050.5,2158.2
XS Rating Curve= 0 ,0
Exp/Cntr=0.3,0.1

Type RM Length L Ch R = 1 ,143226.8,1508,1496.4,1484.7
XS GIS Cut Line= 4
     1534462.575      215891.881     1532856.672      215989.537
     1531999.468      216022.089     1530567.176       217291.62
#Sta/Elev= 30
       0  813.97    39.2  823.77   147.2  827.66   255.1  810.48   382.6  804.85
   461.1  788.96   529.8  764.63   676.9  807.75   794.6  813.57   882.9  804.59
    1344  709.19  1432.3  740.01    1501  747.73  2037.8  713.73  2076.8   707.2
 2102.52689.1238  2125.5   685.3    2184  685.98  2437.4  716.49  2672.8   806.8
  2741.5   818.6  3055.6  812.65  3173.4   821.9    3458  817.57  3585.6  806.61
  3664.1  787.73    3723  805.62  3840.8  819.46  4145.1  835.82  4380.6  828.12
#Mann= 3 , 0 , 0
       0      .1       0 2102.52    .045       0    2184     .08       0
Bank Sta=2102.52,2184
XS Rating Curve= 0 ,0
Exp/Cntr=0.3,0.1

Type RM Length L Ch R = 1 ,141730.4,3384.4,3356.7,3328.7
XS GIS Cut Line= 4
     1534213.009       213059.85     1532943.478      214285.978
     1532238.183      214698.304     1530426.117      216369.311
#Sta/Elev= 30
       0  975.77    68.6  978.28   127.5  968.67   568.7  812.18   725.6  881.15
   960.9  967.46  1137.4  993.87  1392.4  966.87  1519.8  918.88  1686.5   887.1
  1784.4  900.83  1910.8  903.59  2017.8  861.29  2163.7  775.61  2251.3  703.78
  2290.2  685.66  2309.6   685.3  2426.3  685.94  2504.1  705.05    2631  711.24
  2768.5  699.89  2964.9  704.46  3220.3  737.34  3357.8     765  3524.7   779.5
  3760.4  779.12  4212.1  868.15  4663.9  868.93  4978.1  834.85  5046.9  836.82
#Mann= 3 , 0 , 0
       0      .1       0  2290.2    .045       0  2426.3     .08       0
#XS Ineff= 2 , 0
                          2638.8          711.76
Permanent Ineff=
       F       F
Bank Sta=2290.2,2426.3
XS Rating Curve= 0 ,0
Exp/Cntr=0.3,0.1

Type RM Length L Ch R = 1 ,138373.7,1563.9,1581.9,1600.2
XS GIS Cut Line= 4
     1529308.495      213146.655     1529482.106      214600.648
      1529688.27      215631.464     1529883.582      216716.534
#Sta/Elev= 30
       0  824.29   265.4  837.92   501.2  834.18   648.6  824.16   766.6  831.06
   904.1  819.05    1199   806.6  1287.4  789.17  1346.4  784.18  1523.3  787.36
  1680.5  798.77  1749.2  786.81  1827.8  750.86  1965.4  707.56  2053.8   697.5
  2181.5  690.18    2211  682.31  2230.6     681  2309.2  683.99  2328.9  688.88
  2397.7  693.54  2486.1  726.07  2632.6  788.07  2671.7   799.2  2730.2  803.33
  3091.2  806.64  3237.6  811.83  3286.3  814.59  3422.9  832.48  3618.1  840.47
#Mann= 3 , 0 , 0
       0     .07       0    2211    .045       0  2309.2      .1       0
Bank Sta=2211,2309.2
XS Rating Curve= 0 ,0
Exp/Cntr=0.3,0.1

Type RM Length L Ch R = 1 ,136791.8,2355.3,2364.1,2372.8
XS GIS Cut Line= 4
      1529069.78      213352.818     1528679.155      214394.485
     1528038.964      215240.839     1527745.995      216282.506
#Sta/Elev= 30
       0  827.65   478.2  843.22   585.5  834.48   790.5   824.4   878.3   809.3
  1044.2  767.96  1250.1  728.74    1594  699.76  1682.4  697.04  1711.9  693.12
  1790.5  694.95  1869.1  692.04  1898.6  685.89  1908.4  682.02  1928.1     681
  1996.8  681.71  2124.6  727.41  2134.4  733.98  2183.5  779.87  2252.4  826.86
  2281.9  842.56  2321.3  855.87  2340.9  856.84    2459  847.16    2577  864.58
  2763.9  866.43  2872.1  874.62  2970.5  875.96  3137.7  868.04  3255.8  848.96
#Mann= 3 , 0 , 0
       0     .07       0  1898.6    .045       0  1996.8      .1       0
Bank Sta=1898.6,1996.8
XS Rating Curve= 0 ,0
Exp/Cntr=0.3,0.1