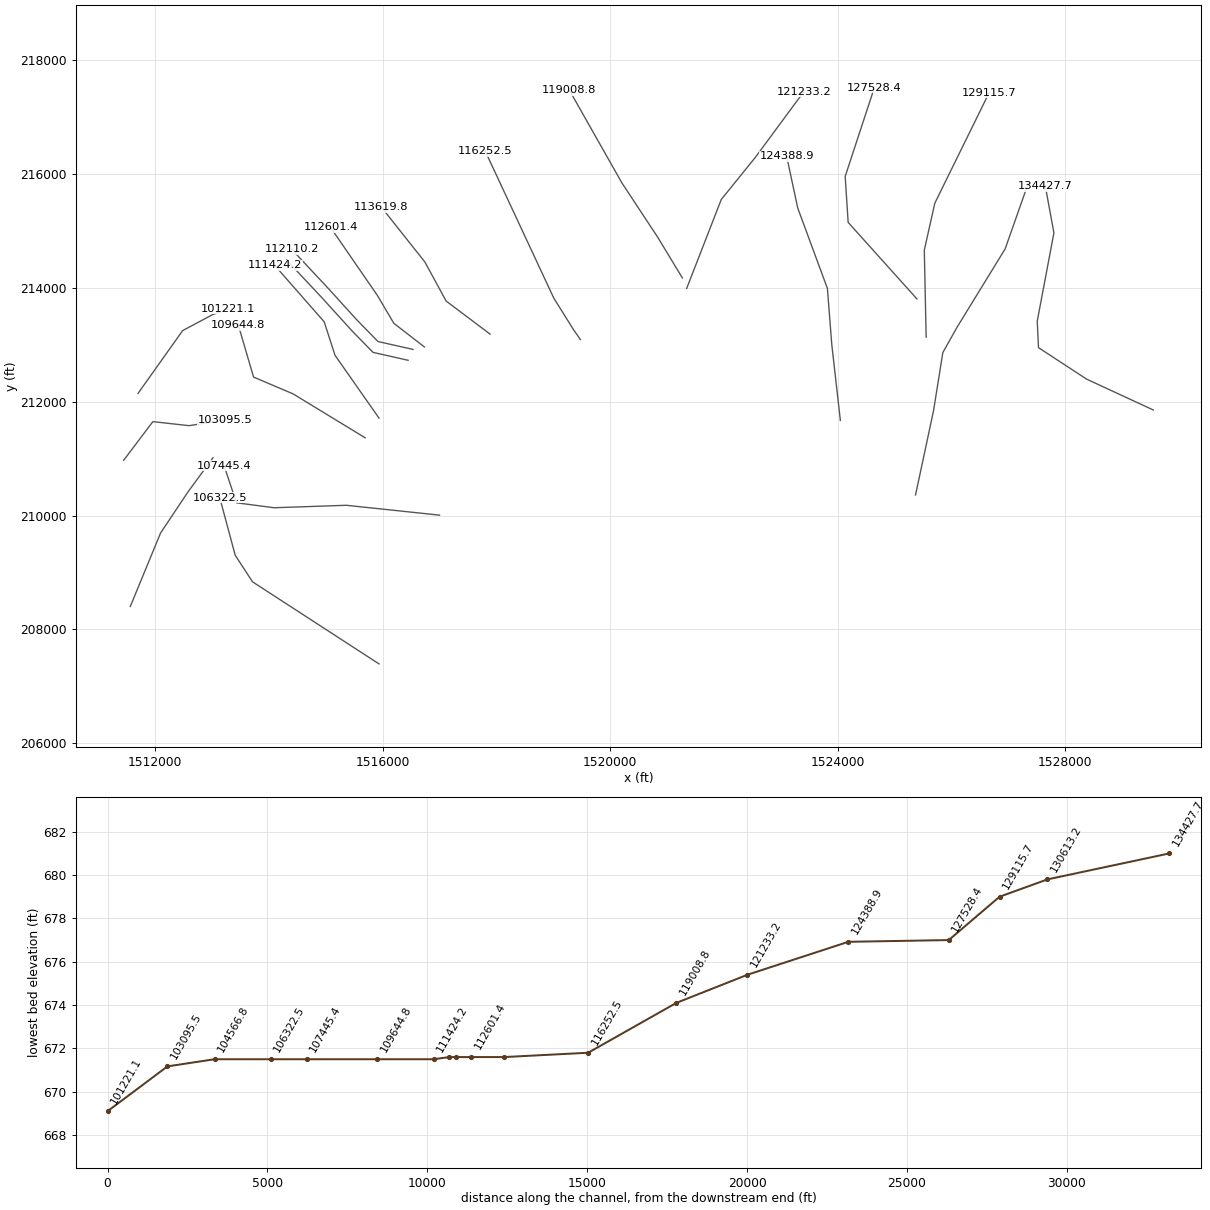
HEC-RAS study SFHGHSRV.prj: SFHGHSRV

--- SFHGHSRV.g01 (geometry) --- (continued)

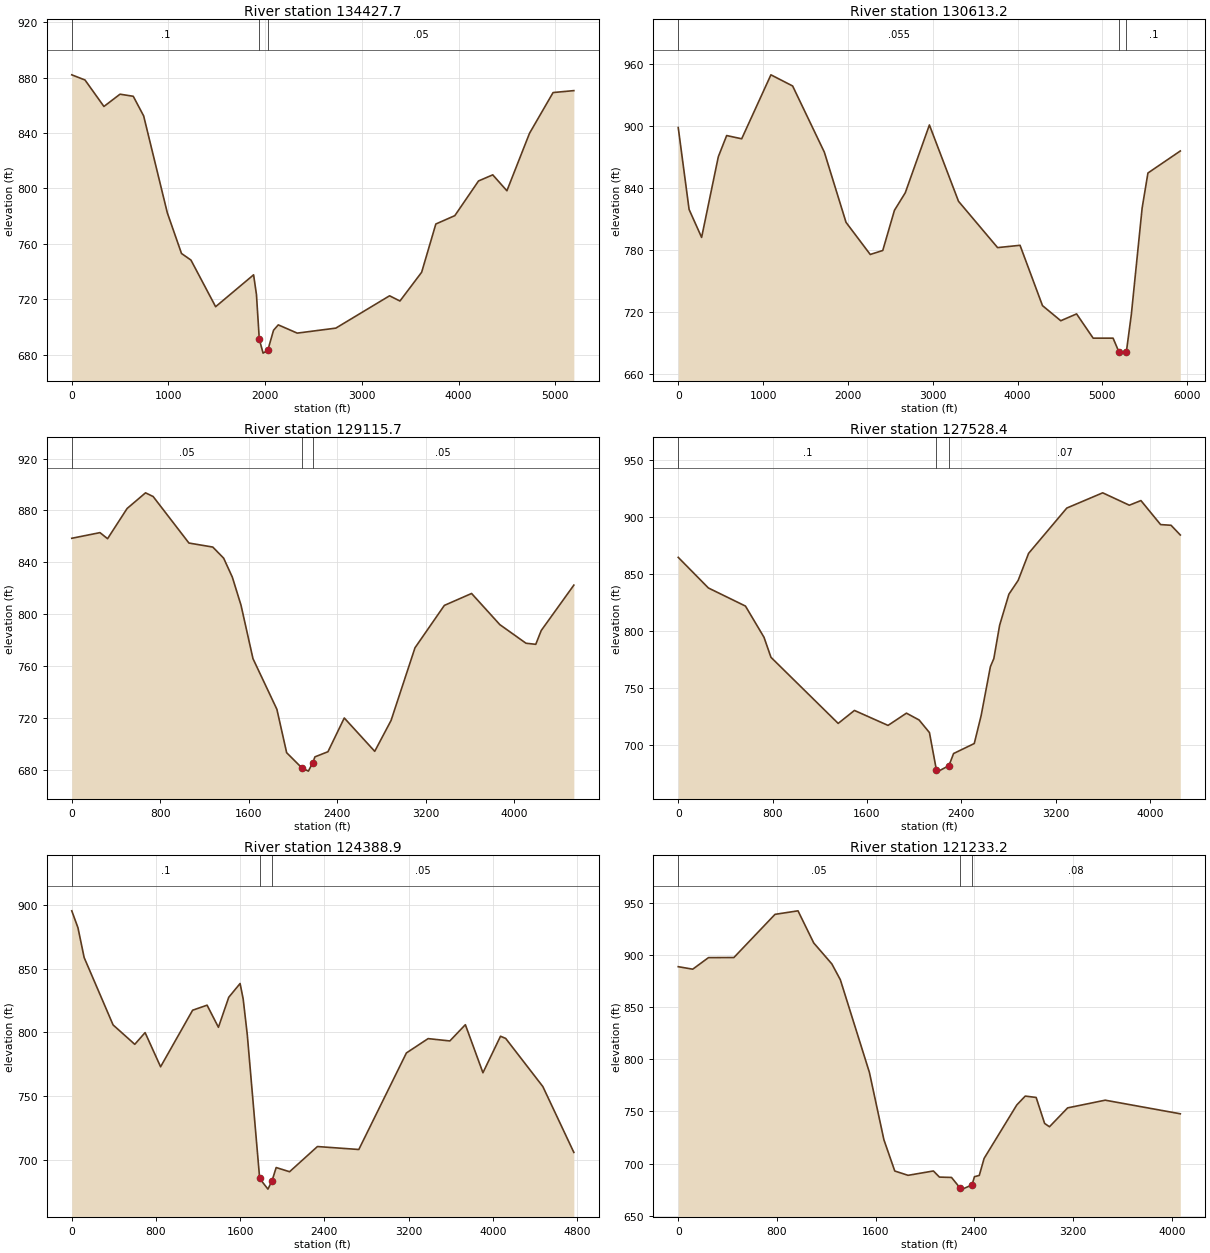
Type RM Length L Ch R = 1 ,134427.7,3845.1,3814.5,3783.7
XS GIS Cut Line= 6
     1529547.211      211855.422     1528375.336      212397.957
     1527528.981      212951.343      1527507.28      213417.922
     1527800.249      214969.572     1527648.339      215794.225
#Sta/Elev= 30
       0     882     137  878.26   332.6  859.14   498.9  868.01   635.9  866.51
   743.5  852.32   988.1  782.35  1134.8  752.97  1232.7   748.2  1487.7  714.53
  1880.4  737.55  1909.9  723.39  1939.3  691.06  1978.6     681  2027.7  683.13
  2086.6   697.5  2135.7  701.41  2331.8  695.45  2730.7  699.05  3286.7  722.41
    3394  718.63  3618.4   739.4  3765.2  774.26  3961.4  780.29  4206.7  805.35
  4353.8  809.76  4500.1  798.25  4734.1  839.79  4977.8   869.2  5192.4  870.59
#Mann= 3 , 0 , 0
       0      .1       0  1939.3    .045       0  2027.7     .05       0
Bank Sta=1939.3,2027.7
XS Rating Curve= 0 ,0
Exp/Cntr=0.3,0.1

Type RM Length L Ch R = 1 ,130613.2,1495.3,1497.5,1498.7
XS GIS Cut Line= 6
     1525367.523      210362.367     1525684.363      211844.572
     1525847.124      212864.537      1526096.69      213309.416
     1526943.044      214687.454      1527355.37      215859.329
#Sta/Elev= 30
       0  898.26     128  818.94   275.6  791.89   472.4  869.98   570.8  890.52
     748  887.38  1092.5  949.33  1348.4  938.54  1722.3  874.42    1978  806.44
  2263.3  775.34  2410.8  779.21  2548.6  818.11  2676.1  835.08  2960.6  900.77
  3303.7  826.86  3764.3  781.99    4029  784.22  4293.6  725.82  4509.2  711.16
  4695.4  717.78    4891  694.29  5125.8   694.3  5194.3  681.02  5272.5   679.8
  5282.3  680.98    5341  717.26  5468.2  820.32  5536.6  854.24  5918.2  875.58
#Mann= 3 , 0 , 0
       0    .055       0  5194.3    .045       0  5282.3      .1       0
Bank Sta=5194.3,5282.3
XS Rating Curve= 0 ,0
Exp/Cntr=0.3,0.1

Type RM Length L Ch R = 1 ,129115.7,1579.9,1587.3,1595.5
XS GIS Cut Line= 4
     1525554.155      213135.804     1525521.603      214665.752
     1525706.065      215490.405     1526660.926      217432.679
#Sta/Elev= 30
       0  858.54     255   862.9   323.7  858.22   500.3  881.51     667  893.59
   735.7  890.74  1059.4  854.87  1275.2  851.76  1373.3   843.2  1451.8  828.57
  1530.3  806.94  1638.4  765.74  1854.6  726.68    1943  693.19  2080.6  681.49
  2139.5     679  2178.8   685.4  2198.5     690  2316.4  693.96  2463.9  719.98
  2739.3  694.27  2886.9  718.06  3103.3   774.1  3368.9  806.79  3614.9  815.98
  3870.7  791.94  4106.8  777.62  4195.3  776.77  4244.5  787.39  4539.6  822.42
#Mann= 3 , 0 , 0
       0     .05       0  2080.6    .045       0  2178.8     .05       0
#XS Ineff= 2 , 0
                         2408.03          710.05
Permanent Ineff=
       F       F
Bank Sta=2080.6,2178.8
XS Rating Curve= 0 ,0
Exp/Cntr=0.3,0.1

Type RM Length L Ch R = 1 ,127528.4,3139.9,3139.5,3139.1
XS GIS Cut Line= 4
     1525391.395      213808.547     1524182.627      215154.034
     1524130.544      215961.325     1524642.697      217519.485
#Sta/Elev= 30
       0  864.65   255.6  837.79   570.1  821.89   727.4  794.49   786.4  776.92
  1356.5  718.89  1494.2  730.27  1779.2  717.13  1935.4  727.88  2042.6   721.9
  2130.4  710.84  2188.8  678.34  2208.3     677    2296  681.86    2335  692.44
  2510.5  701.23    2569  725.83  2647.2  768.64  2676.6  775.86  2725.7   805.1
  2804.3  832.32  2882.9  844.44  2971.3  868.16  3295.4  907.94  3599.8   921.3
  3825.7  910.43  3923.9   914.5  4090.9  893.41  4179.3  892.82  4257.9  884.29
#Mann= 3 , 0 , 0
       0      .1       0  2188.8    .045       0    2296     .07       0
Bank Sta=2188.8,2296
XS Rating Curve= 0 ,0
Exp/Cntr=0.3,0.1

Type RM Length L Ch R = 1 ,124388.9,3172.8,3155.8,3138.7
XS GIS Cut Line= 5
     1524045.909      211670.961     1523893.999      213016.447
     1523818.044      213993.009     1523297.211        215403.6
     1523101.898      216315.058
#Sta/Elev= 30
       0  895.25    58.9  881.97   117.7  858.58   392.5  805.75   598.5  790.52
   696.6  799.72   843.8   772.9    1148  817.28  1285.4  821.23  1393.2  803.88
  1491.2  827.42  1598.9  838.23  1628.3  826.08  1667.5  797.88    1785  685.27
  1863.4  676.92  1902.6  683.49  1941.7  693.85  2069.1  690.57  2333.6  710.33
  2726.7  708.01  3178.8  783.75  3385.1     795  3591.5  793.17  3738.9  805.92
  3905.9  768.22  4072.7  796.86  4121.8  795.16    4475  757.38  4769.4  705.73
#Mann= 3 , 0 , 0
       0      .1       0    1785    .045       0  1902.6     .05       0
Bank Sta=1785,1902.6
XS Rating Curve= 0 ,0
Exp/Cntr=0.3,0.1

Type RM Length L Ch R = 1 ,121233.2,2195.8,2224.4,2253
XS GIS Cut Line= 4
     1521344.086      213993.009     1521951.725      215555.509
     1522548.513      216293.357     1523405.718      217454.381
#Sta/Elev= 30
       0  889.06   117.6  886.67   245.1  897.77     451  897.86   784.3  939.33
   970.6  942.72    1098  911.87  1245.1  891.68  1313.7  876.53    1549  787.62
  1666.7  722.84  1754.8   692.8  1862.4  688.66  2067.8  692.84  2116.8  686.96
  2214.6  686.61  2283.1  676.63  2302.6   675.4  2380.9  679.46  2400.5  687.34
  2439.6  688.55  2478.7   704.9  2743.3  756.21    2812  764.77  2900.4  763.46
  2969.1   738.5  3008.4  735.31  3155.6  753.44    3460  760.83  4068.7  747.76
#Mann= 3 , 0 , 0
       0     .05       0  2283.1    .045       0  2380.9     .08       0
Bank Sta=2283.1,2380.9
XS Rating Curve= 0 ,0
Exp/Cntr=0.3,0.1

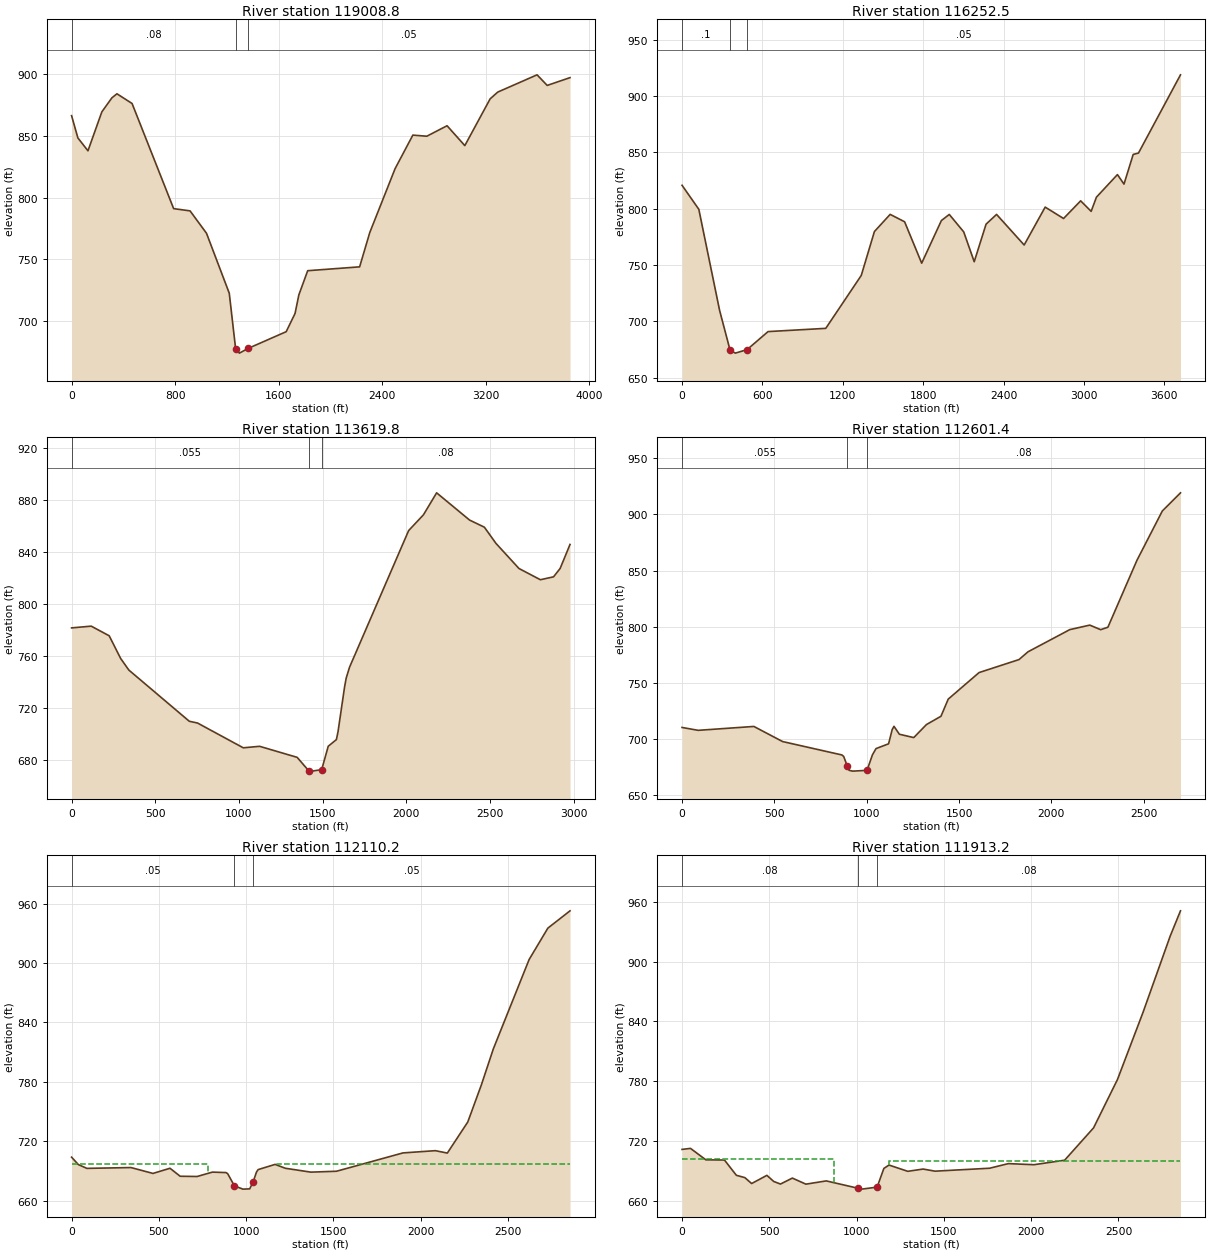
Type RM Length L Ch R = 1 ,119008.8,2757,2756.3,2755.5
XS GIS Cut Line= 4
     1521268.131      214177.471     1520834.103      214893.617
     1520204.763      215848.478     1519282.454      217476.082
#Sta/Elev= 30
       0  866.42    48.7   848.4   126.6  837.98   233.7  869.48   311.6  880.88
   350.5  884.15   467.4   876.3   788.7  791.13   915.6  789.32  1042.7  771.18
  1218.6  722.59  1267.5  677.78  1296.8   674.1  1365.2  677.97  1658.4  691.46
  1726.9  706.22  1756.2  721.24  1824.6  740.86  2225.9  743.98  2304.2  771.73
  2500.1  823.54  2637.2  850.68    2745  849.78  2901.7  858.27  3038.8  842.17
  3234.7  880.08  3293.5  885.54  3597.1  899.51  3675.5  890.93  3851.8  897.24
#Mann= 3 , 0 , 0
       0     .08       0  1267.5    .045       0  1365.2     .05       0
Bank Sta=1267.5,1365.2
XS Rating Curve= 0 ,0
Exp/Cntr=0.3,0.1

Type RM Length L Ch R = 1 ,116252.5,2634.9,2632.8,2630.3
XS GIS Cut Line= 4
      1519476.03      213093.791     1519354.502      213267.402
      1519007.28      213822.957     1517800.683      216409.763
#Sta/Elev= 30
       0  820.69   125.2   799.4   280.4  709.67   358.6  674.37   397.7   671.8
   485.7  674.92   642.2  690.91    1073  693.78  1337.9   740.7    1436  779.63
  1553.7   794.9  1661.6  788.33  1789.1   751.6  1936.2  789.42  1995.1  794.84
    2103  779.35  2181.4  752.89  2269.7   786.2  2348.2  794.86  2554.2  767.73
  2711.1  801.34  2848.4  791.24    2976  806.91  3054.4  797.54  3093.7  810.15
  3250.6  830.19  3299.6  821.76  3368.3  848.09  3407.6  849.28  3721.4   918.7
#Mann= 3 , 0 , 0
       0      .1       0   358.6    .045       0   485.7     .05       0
Bank Sta=358.6,485.7
XS Rating Curve= 0 ,0
Exp/Cntr=0.3,0.1

Type RM Length L Ch R = 1 ,113619.8,1017.6,1018.3,1019
XS GIS Cut Line= 4
     1517887.488      213189.277     1517114.919      213770.874
     1516741.655      214456.638     1515977.766      215420.179
#Sta/Elev= 30
       0  781.73   117.2  783.08   224.7  775.67     293  758.25   341.9  749.33
   703.3  709.92   752.1   708.6  1025.6  689.53  1123.2  690.68  1347.6  682.19
    1416  671.96  1435.5   671.6    1494  672.74  1533.1  690.72  1581.9  695.86
  1591.6  701.92  1630.7  736.32  1640.4  743.14    1660   751.4  2013.4  856.55
  2101.9  868.69  2180.6  885.59  2377.3  864.65  2465.9  859.16  2534.7  846.77
  2672.4  827.41  2800.3  818.77    2879     821  2918.4  827.45  2977.4  845.88
#Mann= 3 , 0 , 0
       0    .055       0    1416    .045       0    1494     .08       0
Bank Sta=1416,1494
XS Rating Curve= 0 ,0
Exp/Cntr=0.3,0.1

Type RM Length L Ch R = 1 ,112601.4,485.8,491.3,496.7
XS GIS Cut Line= 4
     1516732.975      212963.582      1516194.78      213380.249
     1515908.322       213866.36     1515083.669      215064.277
#Sta/Elev= 30
       0  710.46    87.5   707.9   388.9  711.36   544.5  697.91   865.5     686
   875.2  684.68   894.7  676.16   904.4  672.32   923.8   671.6  1001.7  672.29
  1030.8  686.02  1050.3  691.66  1118.4  695.91  1137.9  708.56  1147.6  711.49
  1176.8  704.42  1254.7  701.45  1323.5  713.04  1402.1  720.42  1441.4  735.68
  1608.4   759.3  1824.6  770.86  1873.8  777.82  2099.8  797.53  2207.9  801.53
  2266.8  797.48  2306.1  799.65  2463.4  859.21  2600.9  903.12  2699.2  919.25
#Mann= 3 , 0 , 0
       0    .055       0   894.7    .045       0  1001.7     .08       0
Bank Sta=894.7,1001.7
XS Rating Curve= 0 ,0
Exp/Cntr=0.3,0.1

Type RM Length L Ch R = 1 ,112110.2,197,197,197
XS GIS Cut Line= 5
     1516533.322      212920.179     1515917.002      213059.068
     1515543.738      213441.013     1515031.586      214005.249
     1514397.905      214682.332
#Sta/Elev= 30
       0  703.88    38.9  696.39    87.5  692.58   340.2   693.4   466.5  687.46
   563.7   692.7   622.1  684.61   719.2  684.38   806.6  688.79   884.2  688.34
   893.9  687.28   932.8  674.91   981.3   671.6  1020.2  671.86  1039.6   678.7
    1059  688.78  1068.7  691.34  1165.8  696.59  1224.4  692.68    1371  688.77
  1517.5  689.67  1898.5   708.2    2084  710.46  2152.4  708.03  2269.5  739.42
  2347.6  777.05  2415.9  813.31  2620.9   903.6  2728.3  935.33  2855.2  952.82
#Mann= 3 , 0 , 0
       0     .05       0   932.8    .045       0  1039.6     .05       0
#XS Ineff= 2 , 0
          781.14  697.31    1176           696.9
Permanent Ineff=
       F       F
Bank Sta=932.8,1039.6
XS Rating Curve= 0 ,0
Exp/Cntr=0.3,0.1

Type RM Length L Ch R = 1 ,111913.2,499.1,488.9,478.8
XS GIS Cut Line= 5
     1516446.516      212729.207     1515830.197      212868.096
     1515456.933      213250.041      1514944.78      213814.277
       1514311.1       214491.36
#Sta/Elev= 30
       0  711.49    48.6   712.5   136.1  701.03     243  700.81     311   685.5
   359.6  683.17   398.5  677.22     486  685.43   524.9  679.32   563.7  676.69
   631.8  682.68   709.4   676.6     826  679.86  1010.5  672.39  1029.9   671.6
  1117.3  673.62  1156.1  692.39  1185.4  695.78  1292.8  689.48  1380.8  691.76
  1449.1  689.63  1761.8  692.59  1869.2  697.22  2015.7  696.12  2191.4  700.62
  2357.4  733.15    2494   781.6  2640.4  849.02  2796.6  925.89  2855.2  951.06
#Mann= 3 , 0 , 0
       0     .08       0  1010.5    .045       0  1117.3     .08       0
#XS Ineff= 2 , 0
          872.91  701.47 1183.95          699.75
Permanent Ineff=
       F       F
Bank Sta=1010.5,1117.3
XS Rating Curve= 0 ,0
Exp/Cntr=0.3,0.1

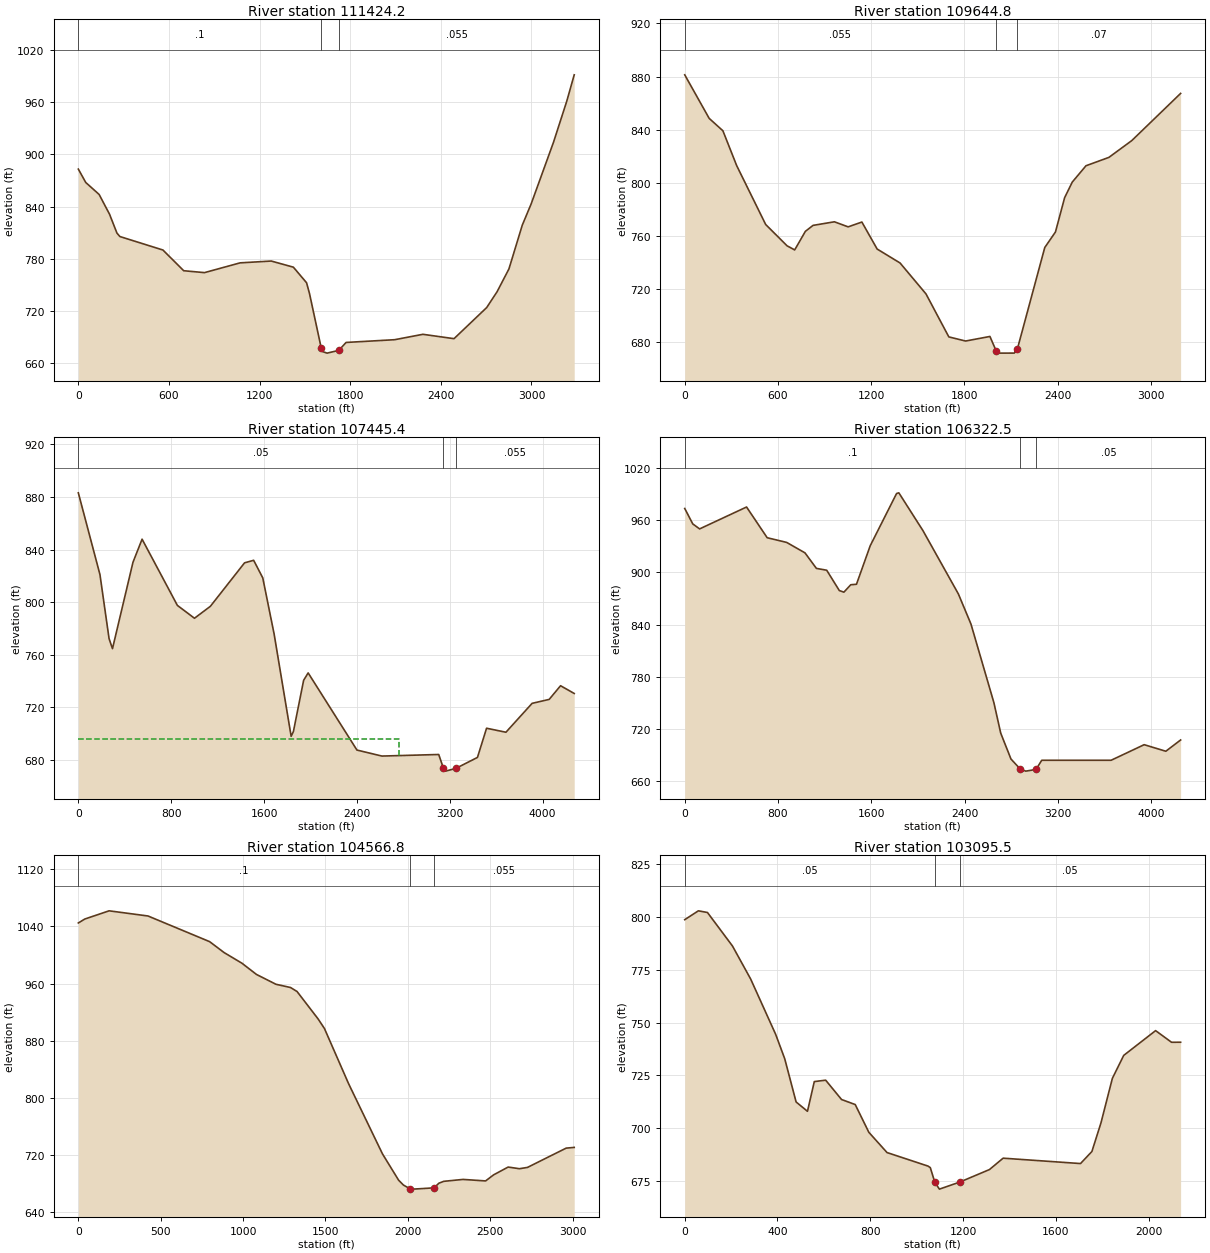
Type RM Length L Ch R = 1 ,111424.2,1760.2,1779.5,1798.6
XS GIS Cut Line= 4
     1515934.363      211713.582     1515161.794      212816.013
     1514970.822      213406.291     1514102.766      214395.874
#Sta/Elev= 30
       0  883.04    49.1  867.67   137.6  853.91   206.4  831.26   255.5  809.54
   275.1  805.53   560.1  790.02   697.7  766.22   835.2  764.04    1071  775.26
  1277.4  777.35  1423.7   770.3    1511   752.4  1530.4  740.01  1607.9  677.47
  1617.6  673.23  1646.7   671.5  1724.2  674.66  1772.7  683.77  2094.3  686.93
  2280.9  693.13  2487.2  688.12  2703.4  723.87  2772.1  742.03  2850.7  768.27
  2939.1  818.63  2998.1  843.17  3145.4  913.71  3233.8  961.23  3282.9  991.41
#Mann= 3 , 0 , 0
       0      .1       0  1607.9    .045       0  1724.2    .055       0
Bank Sta=1607.9,1724.2
XS Rating Curve= 0 ,0
Exp/Cntr=0.3,0.1

Type RM Length L Ch R = 1 ,109644.8,2193.2,2199.3,2205.7
XS GIS Cut Line= 4
     1515691.308       211366.36     1514423.947      212138.929
     1513729.502      212434.068     1513461.273      213348.565
#Sta/Elev= 30
       0  881.29   157.3  848.46   245.7  839.11   334.2  812.89     521  768.47
   658.6   752.4   707.7   749.3   776.5   763.3   825.7  767.79   963.3   770.5
  1051.8  766.68  1140.2  770.31  1238.5  749.96    1386  739.45  1552.9  716.13
  1699.9  683.73  1807.7  680.62  1964.4  684.06  2003.6  673.45  2023.2   671.5
  2121.2  671.53  2140.8   674.5  2317.4  751.11  2386.2  762.82  2445.2  788.68
  2494.3  800.41  2582.7  812.75  2730.1  819.05  2877.5  831.72  3191.8  867.28
#Mann= 3 , 0 , 0
       0    .055       0  2003.6    .045       0  2140.8     .07       0
Bank Sta=2003.6,2140.8
XS Rating Curve= 0 ,0
Exp/Cntr=0.3,0.1

Type RM Length L Ch R = 1 ,107445.4,1143.1,1123,1102.7
XS GIS Cut Line= 5
       1516998.6      210006.551     1515360.145      210180.162
     1514090.613      210136.759     1513428.721      210223.565
     1513211.707      210874.607
#Sta/Elev= 30
       0  883.18   186.3  820.99   264.8  772.26   294.2  764.65   470.8  830.38
   549.2  847.91   853.2  797.56  1000.4  787.78  1137.6  796.88  1431.9  829.93
  1510.3  831.85  1588.8  818.49  1686.7  775.74  1833.3  697.99  1852.8  701.62
  1940.8  740.58  1979.8  746.21    2400  687.53    2615  682.96  3104.4  684.15
  3143.7  674.09  3163.3   671.5  3251.7  673.56  3438.2  681.92  3516.7  704.13
  3683.5  701.08    3909  723.05    4056  726.06  4154.1  736.46  4271.7  730.57
#Mann= 3 , 0 , 0
       0     .05       0  3143.7    .045       0  3251.7    .055       0
#XS Ineff= 2 , 0
         2765.34  696.31
Permanent Ineff=
       F       F
Bank Sta=3143.7,3251.7
XS Rating Curve= 0 ,0
Exp/Cntr=0.3,0.1

Type RM Length L Ch R = 1 ,106322.5,1781.9,1755.7,1730.3
XS GIS Cut Line= 4
     1515935.231      207391.534     1513710.839      208834.676
      1513407.02      209301.256     1513135.752       210310.37
#Sta/Elev= 30
       0  973.49    68.7  955.76   127.7     950   530.3  975.17   707.1  939.86
     874  934.48  1031.2  922.47  1129.4  904.58  1217.7   902.5  1325.8  879.11
    1365  877.25    1424  885.78  1473.1  886.36  1590.9  930.64  1816.8  990.66
  1836.4  991.48  2042.7  948.13  2347.1  875.21  2455.1  840.56  2651.5   750.3
  2710.1  715.25    2798  685.44  2876.2  674.12    2925   671.5  3012.9   673.4
  3061.8  683.96  3657.5     684  3940.7   701.9  4126.3  694.36  4253.2   707.3
#Mann= 3 , 0 , 0
       0      .1       0  2876.2    .045       0  3012.9     .05       0
Bank Sta=2876.2,3012.9
XS Rating Curve= 0 ,0
Exp/Cntr=0.3,0.1

Type RM Length L Ch R = 1 ,104566.8,1496.2,1471.3,1445.5
XS GIS Cut Line= 4
     1511562.402      208400.648     1512094.086      209691.881
     1512571.516      210408.027     1513016.395      211015.666
#Sta/Elev= 30
       0 1044.95    39.3 1050.46   186.8 1061.97   422.9 1054.72   796.6 1018.77
     885 1003.39   993.2  988.44  1081.7  972.66  1199.7  958.92  1288.2  954.38
  1327.6  948.79  1455.1  910.44  1494.2  896.76  1640.9  819.28  1846.3  720.93
  1944.1   684.1  1973.5  677.19  2012.6   672.1  2032.2   671.5  2159.3  673.28
  2188.6  679.78    2218  682.43  2335.4  685.12  2472.3     683  2521.2  691.58
  2609.2  702.46  2677.7  700.13  2726.6  701.97  2961.3  729.03  3010.2  730.03
#Mann= 3 , 0 , 0
       0      .1       0  2012.6    .045       0  2159.3    .055       0
Bank Sta=2012.6,2159.3
XS Rating Curve= 0 ,0
Exp/Cntr=0.3,0.1

Type RM Length L Ch R = 1 ,103095.5,1860.6,1874.3,1887.9
XS GIS Cut Line= 4
     1511445.234      210970.285     1511959.123       211650.84
     1512593.218      211579.902     1513233.409      211677.558
#Sta/Elev= 30
       0   798.8    58.8  802.99      98   802.2   205.8  786.34   284.3  770.69
   392.1  744.49   431.3  732.89   480.3  712.45   529.3  708.03   558.7   722.1
   607.7  722.78   676.3  713.61   735.2  711.23     794  698.07   872.4  688.49
  1049.1  682.08  1058.9  681.37  1078.6  674.36  1098.2  671.17  1186.5  674.53
  1314.1  680.44    1373  685.83  1706.7  683.28  1755.8  688.99    1795  702.58
  1844.1  723.64  1893.1  734.52  2030.5  746.24  2099.2  740.73  2138.4  740.75
#Mann= 3 , 0 , 0
       0     .05       0  1078.6    .045       0  1186.5     .05       0
Bank Sta=1078.6,1186.5
XS Rating Curve= 0 ,0
Exp/Cntr=0.3,0.1

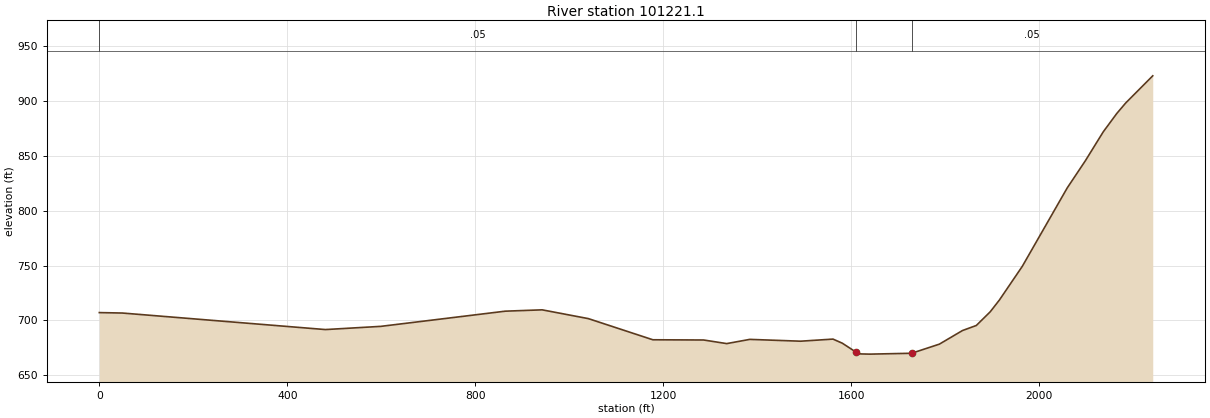
Type RM Length L Ch R = 1 ,101221.1,799.1,818,837
XS GIS Cut Line= 4
     1511698.345      212147.079     1512483.067      213251.245
     1513003.901      213529.023     1513281.678       213633.19
#Sta/Elev= 30
       0  707.01    49.1  706.61     481  691.52   598.8  694.44   863.8  708.31
   942.3  709.53  1040.5  701.53  1177.9   682.2  1285.9     682    1335  678.71
  1384.1  682.56  1492.3   680.9  1561.2  682.82  1580.9   679.1  1610.4  670.86
  1620.2  669.28  1639.9   669.1  1728.4  669.88  1787.5   678.2  1836.7  690.63
  1866.2  695.26  1895.7  707.71  1915.4  718.56    1964  749.23  2059.7  820.89
    2098  845.49  2136.3  872.04    2165  888.75  2184.1  898.39  2241.6  923.17
#Mann= 3 , 0 , 0
       0     .05       0  1610.4    .045       0  1728.4     .05       0
Bank Sta=1610.4,1728.4
XS Rating Curve= 0 ,0
Exp/Cntr=0.3,0.1