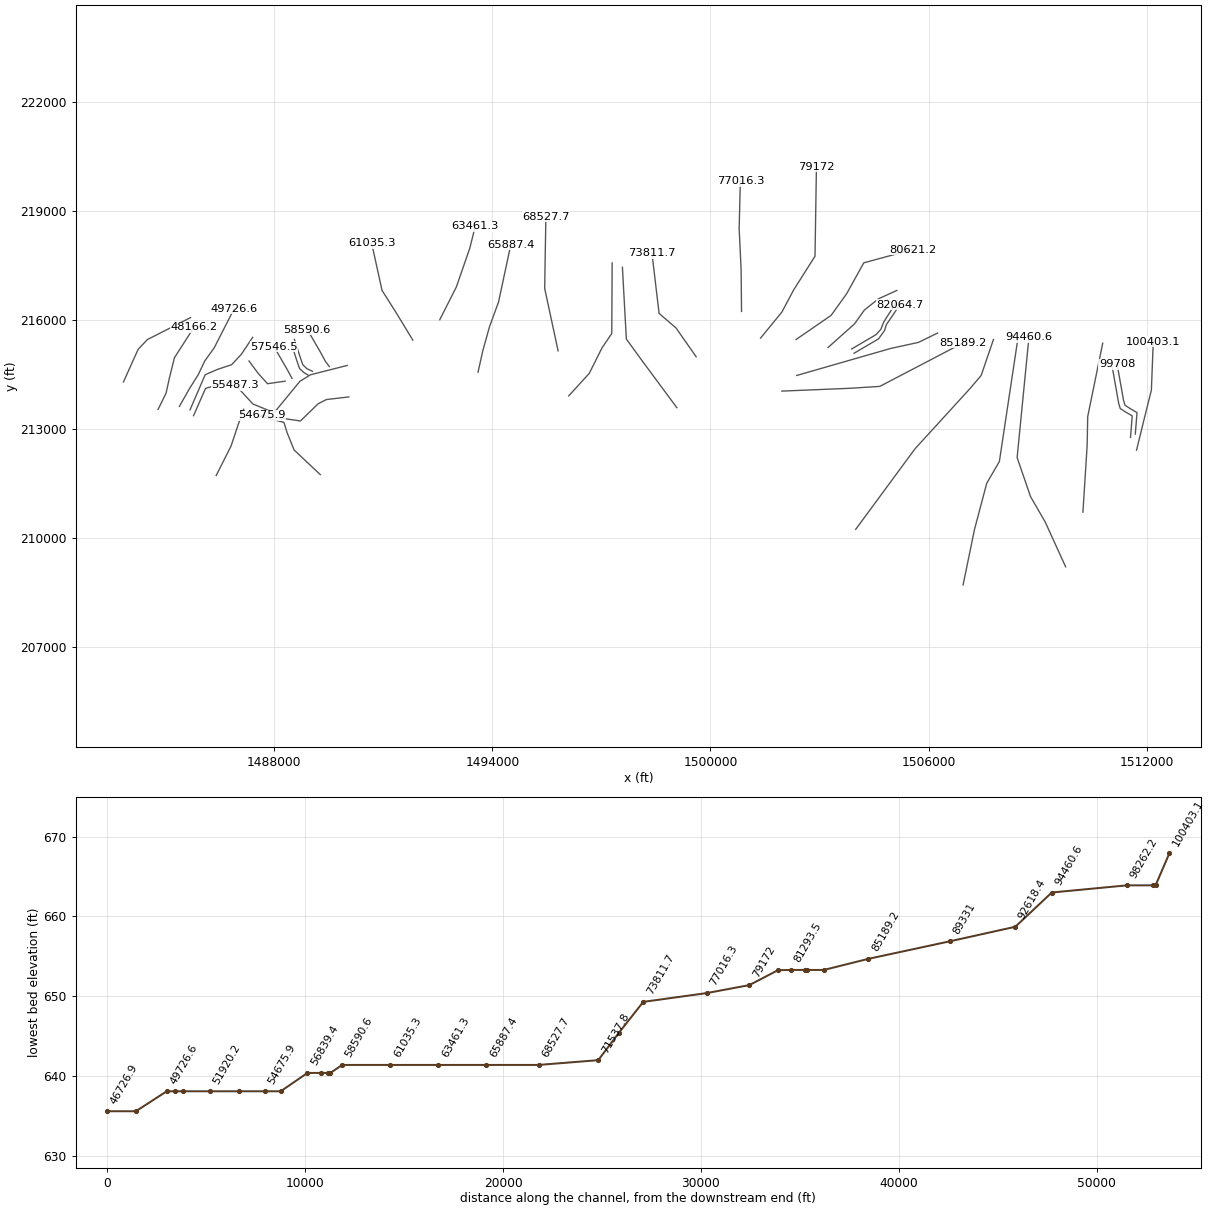
HEC-RAS study SFHGHSRV.prj: SFHGHSRV

--- SFHGHSRV.g01 (geometry) --- (continued)

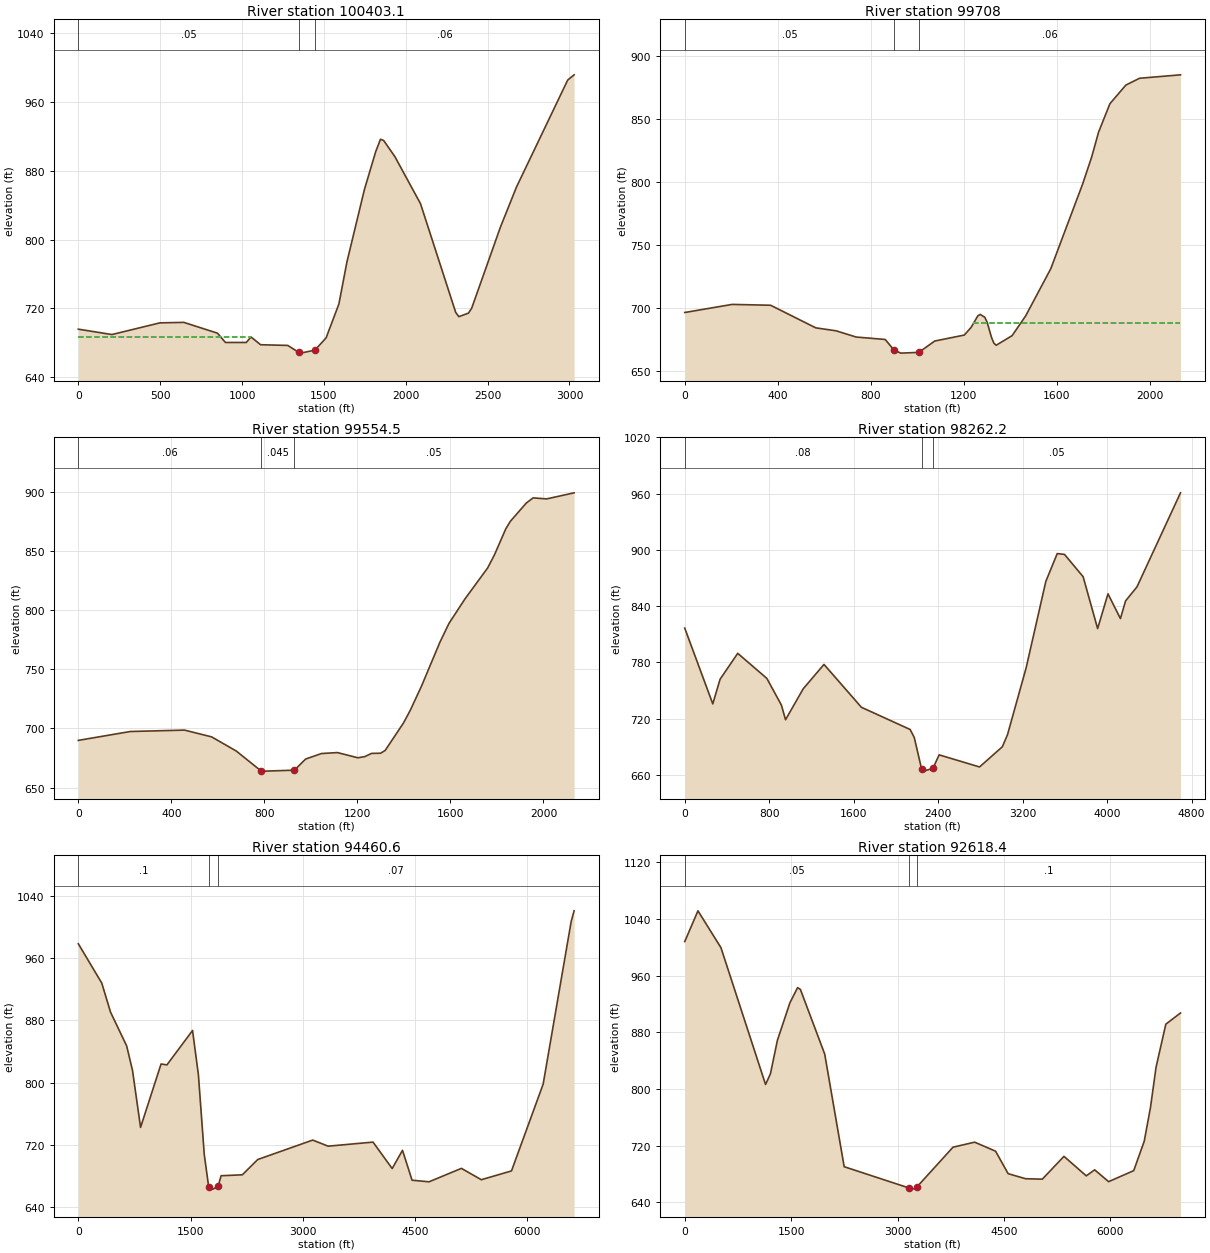
Type RM Length L Ch R = 1 ,100403.1,666.8,695.1,723.2
XS GIS Cut Line= 4
     1511722.651      212424.856     1511948.345      213344.995
     1512130.637      214074.162      1512182.72      215402.287
#Sta/Elev= 30
       0  695.78   205.1  689.51   498.1  703.11   644.6  703.68   849.7  691.13
   898.6  680.32  1025.5  680.28  1054.8  686.67  1113.4  677.67  1279.3  676.87
  1347.6  668.64  1357.4   667.9  1445.2  671.37  1513.6  685.72  1591.6  725.05
  1640.5  773.88  1747.9  858.56  1816.3  902.28  1845.6   916.8  1865.2   915.3
  1933.6  896.53    2090  841.85    2305  715.33  2324.5  710.33  2383.1  714.47
  2402.7  720.19  2578.6  814.74  2676.3  861.14  2989.1  985.63  3028.2  991.74
#Mann= 3 , 0 , 0
       0     .05       0  1347.6    .045       0  1445.2     .06       0
#XS Ineff= 2 , 0
         1054.74   686.9
Permanent Ineff=
       F       F
Bank Sta=1347.6,1445.2
XS Rating Curve= 0 ,0
Exp/Cntr=0.3,0.1

Type RM Length L Ch R = 1 ,99708   ,153.6,153.6,153.6
XS GIS Cut Line= 6
      1511688.29      212866.118     1511735.671      213456.974
     1511561.192      213558.537     1511407.546      213657.495
      1511365.88      213787.704      1511188.29      214789.729
#Sta/Elev= 30
       0  696.18   204.1  702.61   369.3  701.94   563.6  683.98   650.4  681.65
     737  676.69     862  674.75   900.4  666.22   929.3   663.9  1006.7  664.49
    1075   673.5  1202.2  678.26  1231.5  684.36  1260.9  693.67  1270.7  694.63
  1290.2  692.39    1300  688.66  1319.6  676.14  1329.4  671.82  1339.2  670.15
  1407.7  677.78  1466.4   693.6    1574  730.97    1711  798.26  1750.1  819.88
  1779.5  839.48  1828.4   862.1  1896.9  876.88  1955.6  882.29  2131.8  885.03
#Mann= 3 , 0 , 0
       0     .05       0   900.4    .045       0  1006.7     .06       0
#XS Ineff= 2 , 0
                         1241.64          687.99
Permanent Ineff=
       F       F
Bank Sta=900.4,1006.7
XS Rating Curve= 0 ,0
Exp/Cntr=0.3,0.1

Type RM Length L Ch R = 1 ,99554.5 ,1315.3,1292.3,1269.1
XS GIS Cut Line= 6
     1511556.346       212775.84     1511603.727      213366.697
     1511429.248      213468.259     1511275.602      213567.217
     1511233.935      213697.426     1511056.346      214699.451
#Sta/Elev= 30
       0  689.89   223.5  697.39   456.7  698.57   573.3  692.84   679.3  680.87
     785   664.2   804.3   663.9   929.3  664.72   977.4  674.11  1045.8  678.78
  1114.1  679.58  1202.2  675.18  1231.5  676.15  1260.9  678.88    1300  679.04
  1319.6  681.43  1397.9  704.53  1427.2  715.25  1476.2  735.99  1554.4  772.68
  1593.6   788.7  1662.1  809.33  1759.9   835.6  1789.3  846.68  1838.2  868.76
  1857.8  875.08  1926.3  890.52  1955.6  894.86  2014.3  894.02  2131.8  899.14
#Mann= 3 , 0 , 0
       0     .06       0     785    .045       0   929.3     .05       0
Bank Sta=785,929.3
XS Rating Curve= 0 ,0
Exp/Cntr=0.3,0.1

Type RM Length L Ch R = 1 ,98262.2 ,3788.9,3801.6,3813.9
XS GIS Cut Line= 4
     1510247.623      210717.684     1510363.942      212554.489
     1510379.676      213348.565     1510792.002      215366.794
#Sta/Elev= 30
       0  816.48   265.7  735.63   334.6  761.91     502  789.57   777.5  762.83
   915.3  734.39   954.7  718.74    1122  751.73  1318.8  777.74  1673.2  731.99
  2134.6  708.32  2173.9  699.66  2242.5  666.42  2262.1   663.9  2350.4  666.87
  2409.2  681.26  2791.7  668.34  3007.5  689.88  3056.5  702.76  3233.1  774.15
  3419.4  866.27  3527.4  895.97    3596   895.1  3772.6  871.31  3909.9  815.96
    4008  853.02  4125.7  826.63  4174.8  845.52  4282.6  860.48  4694.6  960.78
#Mann= 3 , 0 , 0
       0     .08       0  2242.5    .045       0  2350.4     .05       0
Bank Sta=2242.5,2350.4
XS Rating Curve= 0 ,0
Exp/Cntr=0.3,0.1

Type RM Length L Ch R = 1 ,94460.6 ,1865.6,1842.3,1818.9
XS GIS Cut Line= 5
     1509772.037       209214.45     1509207.801      210451.429
     1508806.325      211145.874     1508437.402      212220.093
     1508762.922      215529.554
#Sta/Elev= 30
       0   978.4     313   927.9   430.4  890.49   645.6  847.14   723.8  815.64
   831.4  742.36  1105.3  823.86  1183.5  822.69  1525.9  866.94  1604.1  810.08
  1682.4   707.5  1741.1  666.12  1799.8     663  1868.3  667.07  1907.4  680.23
  2191.1  681.41  2396.7  701.06  3131.1  726.05  3336.9  718.22    3937  723.44
  4192.8  689.45  4330.6  712.89  4458.5  674.46  4684.8  672.41  5117.7  689.69
  5383.3   675.1  5786.7  686.41  6209.8  798.03  6583.6 1006.77    6623 1020.75
#Mann= 3 , 0 , 0
       0      .1       0  1741.1    .045       0  1868.3     .07       0
#XS Ineff= 2 , 0
                         2785.95           709.8
Permanent Ineff=
       F       F
Bank Sta=1741.1,1868.3
XS Rating Curve= 0 ,0
Exp/Cntr=0.3,0.1

Type RM Length L Ch R = 1 ,92618.4 ,3291.9,3287.4,3282.3
XS GIS Cut Line= 5
     1506950.856      208715.318     1507265.527      210245.266
     1507601.898      211514.797      1507949.12      212111.586
     1508459.103      215497.002
#Sta/Elev= 30
       0 1007.95   186.6 1051.32   510.8  999.31  1139.6  806.31  1208.3  821.43
  1306.6  868.67  1483.4  921.73  1591.4  942.97  1630.6  940.46  1973.6   849.2
    2248  690.34  3157.3  660.48  3244.8  658.71    3274  661.84  3782.2  717.86
  4087.2  724.97  4382.3  712.23  4559.4  680.53  4805.3  673.39  5041.4  672.77
  5346.4  704.94  5661.2  677.43  5779.3  685.94  5976.1  669.23  6330.2  684.83
  6477.8  726.14  6566.3  773.94    6645  830.79  6782.8  891.46  6989.4  907.21
#Mann= 3 , 0 , 0
       0     .05       0  3157.3    .045       0    3274      .1       0
#XS Ineff= 2 , 0
                         3874.58          718.87
Permanent Ineff=
       F       F
Bank Sta=3157.3,3274
XS Rating Curve= 0 ,0
Exp/Cntr=0.3,0.1

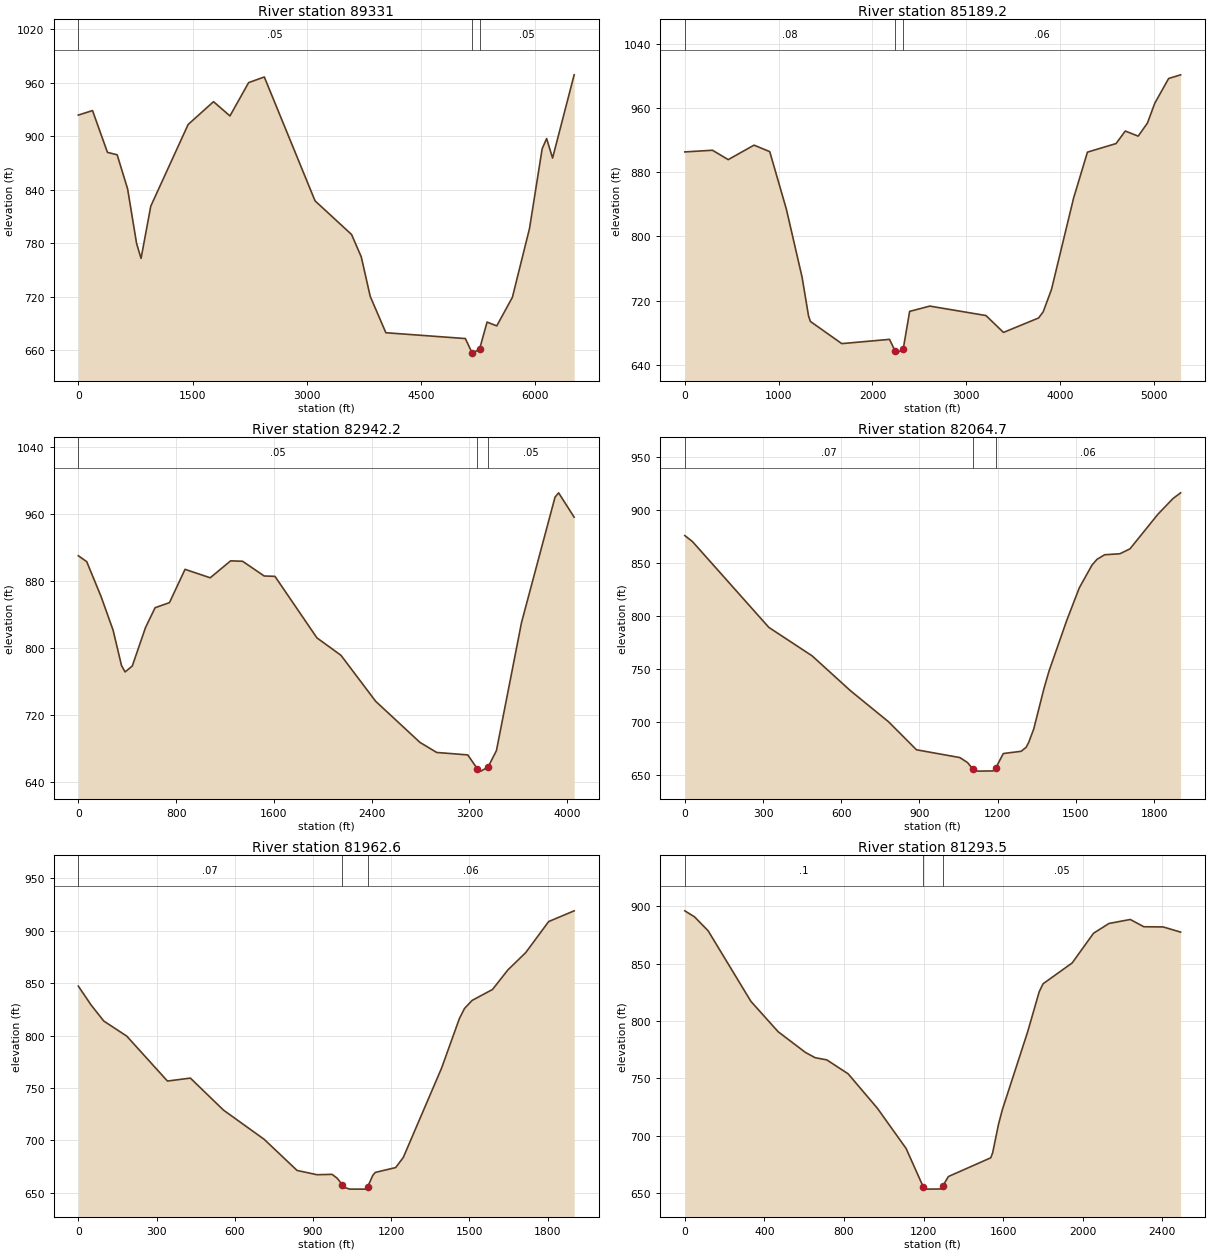
Type RM Length L Ch R = 1 ,89331   ,4159.8,4141.8,4121.7
XS GIS Cut Line= 6
      1503997.39      210246.037     1505632.335      212465.892
     1506471.348      213384.058     1507148.432      214126.245
     1507447.911      214477.808     1507786.453      215467.391
#Sta/Elev= 30
       0  923.58   186.4  928.61   382.6  881.81   510.2   879.1   647.5  840.83
   765.3  779.77   824.1  763.05   951.7  821.55  1442.2  913.02  1775.8   938.6
  1991.7  922.62    2237  959.95    2443  966.27  3109.5  827.51  3589.4  789.79
  3716.7  764.72  3834.2  720.51  4039.7  679.74    5084  673.22  5172.4   657.2
  5182.2   656.9  5270.7  661.41  5368.9  691.66  5496.5  687.43  5701.8  719.43
  5926.6   796.5  6092.8   885.8  6151.4   897.3  6229.6  875.42  6513.1  968.67
#Mann= 3 , 0 , 0
       0     .05       0  5172.4    .045       0  5270.7     .05       0
Bank Sta=5172.4,5270.7
XS Rating Curve= 0 ,0
Exp/Cntr=0.3,0.1

Type RM Length L Ch R = 1 ,85189.2 ,2243.5,2247,2251.8
XS GIS Cut Line= 4
      1501966.14       214048.12     1503854.161      214126.245
     1504661.453      214178.329     1506953.119      215376.245
#Sta/Elev= 30
       0  905.13   295.3   907.2   462.6  895.52   738.1  913.56   905.4  905.46
  1082.6  833.86  1249.9  749.28  1318.8  701.03  1338.5  694.14  1673.1  666.53
    2182  671.82  2240.5  657.62    2260  654.69  2328.2  659.94  2396.5  706.63
  2610.9  713.23  3209.9  701.47  3396.7  680.46  3770.3  698.42  3819.5  706.04
    3908  733.89  4143.9  847.72  4291.4  904.85  4596.2  915.52  4694.6  931.12
  4832.2  924.78  4930.5  940.97  5009.2  965.75  5156.7  996.51  5284.5 1001.08
#Mann= 3 , 0 , 0
       0     .08       0  2240.5    .045       0  2328.2     .06       0
Bank Sta=2240.5,2328.2
XS Rating Curve= 0 ,0
Exp/Cntr=0.3,0.1

Type RM Length L Ch R = 1 ,82942.2 ,853.1,877.5,901.8
XS GIS Cut Line= 4
     1502374.705      214478.242     1504958.038      215221.297
     1505721.927      215387.964     1506249.705      215644.908
#Sta/Elev= 30
       0   910.4    68.7  903.35   186.4  861.58   284.5  821.52   353.2  779.42
   382.6  771.69   441.5   778.8   549.4  824.59   627.9  848.35   745.6  854.43
   873.1  894.18  1079.2  884.08  1245.9   904.3    1344  903.81  1520.6  886.25
  1608.9  885.79  1952.3  812.35  2148.5  791.63    2433  736.64  2795.6  687.55
  2932.4  675.59  3186.5  672.65  3264.7  656.09    3294   653.3  3352.6  658.19
  3421.1  677.86  3626.5  830.86  3900.4  980.34  3929.8   985.5  4056.9  956.44
#Mann= 3 , 0 , 0
       0     .05       0  3264.7    .045       0  3352.6     .05       0
Bank Sta=3264.7,3352.6
XS Rating Curve= 0 ,0
Exp/Cntr=0.3,0.1

Type RM Length L Ch R = 1 ,82064.7 ,104.1,102.1,100.3
XS GIS Cut Line= 5
     1503951.094      215089.353     1504624.705      215485.186
     1504791.372      215714.353     1504839.983      215874.075
     1505214.983      216429.631
#Sta/Elev= 30
       0  875.68    29.3  870.05   322.3  789.01   488.3  762.14   634.8  729.36
   781.3  699.94   888.8  673.45  1054.9  666.11  1084.3  661.44    1104  655.46
  1123.6   653.3  1182.5   653.5  1192.3  656.04  1221.8  669.92  1289.9  672.01
  1309.3   675.8    1319  680.31  1338.5   693.1  1377.3  730.91  1396.8  747.51
  1464.8  795.42  1513.3  826.34  1561.9   847.8  1581.3  853.27  1610.5  857.58
  1668.8   858.5  1707.6  863.14  1814.5  895.73  1872.8  910.68  1901.9  916.03
#Mann= 3 , 0 , 0
       0     .07       0    1104    .045       0  1192.3     .06       0
Bank Sta=1104,1192.3
XS Rating Curve= 0 ,0
Exp/Cntr=0.3,0.1

Type RM Length L Ch R = 1 ,81962.6 ,674.2,669.1,663.6
XS GIS Cut Line= 5
     1503885.122      215207.408     1504558.733      215603.242
     1504687.205      215745.603     1504770.538      215953.936
     1505149.011      216547.686
#Sta/Elev= 30
       0  847.19    48.8  829.21    97.7  813.82   185.6  799.46   341.8  756.51
   429.7  759.35   556.7  728.77   712.9  700.85   838.8  671.16   915.5  667.06
   973.1  667.42   992.6  663.74  1012.1  657.66  1021.8   654.8  1041.4   653.3
  1099.9   653.3  1109.6  655.38  1129.2  666.42  1138.9  669.25    1217  673.89
  1246.3  683.55    1393   768.8  1461.5  816.22    1481  825.83  1510.4  833.55
  1588.6     844  1647.3  862.62  1715.8  879.18  1803.8  908.83  1901.6  919.09
#Mann= 3 , 0 , 0
       0     .07       0  1012.1    .045       0  1109.6     .06       0
Bank Sta=1012.1,1109.6
XS Rating Curve= 0 ,0
Exp/Cntr=0.3,0.1

Type RM Length L Ch R = 1 ,81293.5 ,672.2,672.3,672.3
XS GIS Cut Line= 5
     1503237.552      215248.728     1503966.719       215899.77
     1504234.369      216277.287     1504622.969       216587.27
     1505128.177      216816.436
#Sta/Elev= 30
       0  896.06    48.9  890.81   117.3  878.65   332.4  817.07   469.2  790.61
   606.1  772.58   654.9  767.96   713.6  766.05   821.1  753.87   967.7  723.92
  1112.5  688.72  1199.3  654.98  1218.5   653.3    1286  653.44  1295.7  655.73
  1324.6  664.26  1537.8  680.62  1547.5   685.1  1576.7  709.81  1596.2  722.66
    1723  790.36  1781.4  825.52  1800.9  832.44  1947.1  850.61  2054.2  876.47
    2132  885.04  2239.1  888.51  2307.2  882.18  2404.5     882  2492.1   877.5
#Mann= 3 , 0 , 0
       0      .1       0  1199.3    .045       0  1295.7     .05       0
Bank Sta=1199.3,1295.7
XS Rating Curve= 0 ,0
Exp/Cntr=0.3,0.1

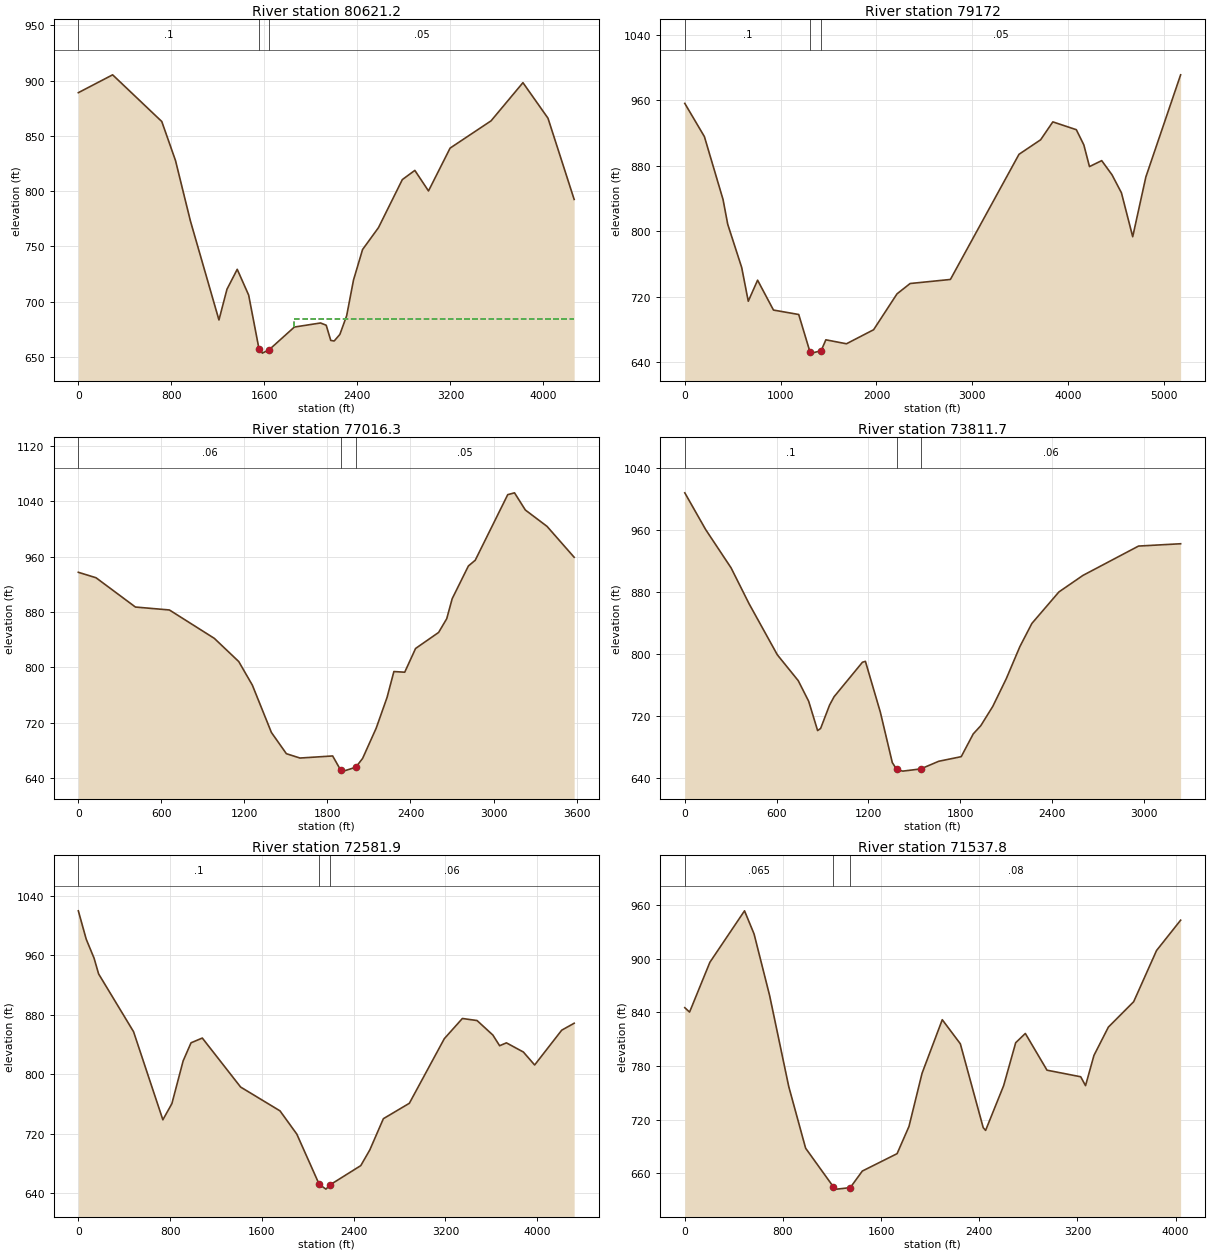
Type RM Length L Ch R = 1 ,80621.2 ,1446.5,1449.3,1452
XS GIS Cut Line= 5
     1502356.765      215467.391     1503320.307      216131.454
     1503749.994      216730.412     1504218.744      217576.766
      1505559.89      217941.349
#Sta/Elev= 30
       0  889.15     295  905.32   717.9  863.02   835.9  827.66   963.7   773.1
  1209.5   683.3  1278.3  711.08  1366.8  729.18  1465.1  705.82  1553.5  657.36
    1583  653.27    1642  656.41  1858.2  676.89  2083.3  680.57  2132.1  678.53
  2171.2  664.78  2200.5  664.25  2249.4  670.19    2308  687.14  2366.7  719.42
  2444.8  747.09  2581.7  766.94  2786.9  810.45  2894.4  818.76  3011.9  800.16
  3197.8  838.96  3550.2  863.66  3824.2  898.22  4039.6  866.04  4264.7  792.49
#Mann= 3 , 0 , 0
       0      .1       0  1553.5    .045       0    1642     .05       0
#XS Ineff= 2 , 0
                         1856.19          684.56
Permanent Ineff=
       F       F
Bank Sta=1553.5,1642
XS Rating Curve= 0 ,0
Exp/Cntr=0.3,0.1

Type RM Length L Ch R = 1 ,79172   ,2143.1,2155.6,2167.7
XS GIS Cut Line= 5
     1501380.203      215506.454      1501966.14      216222.599
     1502291.661      216834.579     1502877.598      217759.058
     1502916.661      220219.995
#Sta/Elev= 30
       0  956.39   204.5  915.84   399.3   838.9     448  808.78   594.1  755.84
   662.3  714.77   759.7  740.48   925.3     704  1188.9  698.57  1306.1     653
  1325.6   651.4  1423.2   654.4    1472  667.66  1686.9  662.82  1970.3  679.96
  2214.6  723.79  2351.4  736.41  2771.8  741.37  3487.6  894.22  3713.2  911.94
  3840.7  933.82  4085.8  924.26  4164.2  905.72  4223.1  879.21  4350.6   886.5
  4458.4  869.15  4556.5  847.21  4674.2  793.56  4811.4  866.54  5174.2  991.28
#Mann= 3 , 0 , 0
       0      .1       0  1306.1    .045       0  1423.2     .05       0
Bank Sta=1306.1,1423.2
XS Rating Curve= 0 ,0
Exp/Cntr=0.3,0.1

Type RM Length L Ch R = 1 ,77016.3 ,3188.1,3204.6,3220.6
XS GIS Cut Line= 4
     1500856.042      216240.047     1500845.191       217379.37
     1500790.938      218518.693      1500823.49      219820.776
#Sta/Elev= 30
       0  937.34   127.7  929.48   412.5   887.2   658.1  882.96   982.2  842.05
    1159  808.55  1257.4   774.5    1395  706.21  1503.2  675.56  1601.5  669.28
  1837.5  672.29  1896.5  651.57  1916.2   650.4  2004.7  656.04  2053.8  668.66
  2152.2  712.44  2230.8  756.86    2280  794.11  2358.3  793.15  2436.7   827.4
  2603.2  850.54  2661.9  870.42  2701.1  899.17  2818.6  946.54  2867.6  954.68
  3102.6 1049.38  3151.6 1052.02  3229.9 1027.22  3386.6  1003.6  3582.5  959.04
#Mann= 3 , 0 , 0
       0     .06       0  1896.5    .045       0  2004.7     .05       0
Bank Sta=1896.5,2004.7
XS Rating Curve= 0 ,0
Exp/Cntr=0.3,0.1

Type RM Length L Ch R = 1 ,73811.7 ,1233.2,1229.8,1226.7
XS GIS Cut Line= 4
     1499608.212      214992.217     1499054.826      215784.318
     1498588.247      216185.794     1498392.934      217835.099
#Sta/Elev= 30
       0  1007.9   136.6  960.52   302.6  911.24   419.7  865.23   605.1  799.21
   741.8   765.9   810.1  739.35   868.7  701.54   888.2  704.27   946.7  734.36
     976  745.08  1161.7  789.58  1181.2  790.76  1278.9  725.22  1357.1  660.27
  1386.4  651.45  1425.5   649.3  1542.7  652.13  1660.4  661.98  1807.8  667.94
  1886.4  697.25  1935.6  707.83  2014.2  732.72  2102.6  768.49  2191.1  809.65
  2269.7  839.56  2446.6  880.18  2603.8  901.49  2967.4   939.3  3242.6  942.28
#Mann= 3 , 0 , 0
       0      .1       0  1386.4    .045       0  1542.7     .06       0
Bank Sta=1386.4,1542.7
XS Rating Curve= 0 ,0
Exp/Cntr=0.3,0.1

Type RM Length L Ch R = 1 ,72581.9 ,1069.2,1044.1,1019
XS GIS Cut Line= 4
     1499076.528      213592.478     1498089.115      214927.113
     1497687.639      215480.499     1497579.132      217455.325
#Sta/Elev= 30
       0  1020.1    68.8  981.88   137.5  956.23   176.8  935.18   481.4  857.37
   736.8  738.77   815.4  760.52   913.6  818.09   982.4  842.42  1080.6  848.83
  1414.6  782.85  1757.9  750.79  1904.4  719.48  2099.7  651.81  2158.3  645.43
  2197.4  651.51    2462   677.1  2540.7  698.26  2658.8  740.26  2885.1  760.99
  3190.1  848.01  3347.5  875.17  3475.4  872.39  3613.2  852.85  3672.2  838.48
  3731.3  842.35  3878.9  830.04  3977.3  812.57  4213.4  859.44  4321.7  868.75
#Mann= 3 , 0 , 0
       0      .1       0  2099.7    .045       0  2197.4     .06       0
Bank Sta=2099.7,2197.4
XS Rating Curve= 0 ,0
Exp/Cntr=0.3,0.1

Type RM Length L Ch R = 1 ,71537.8 ,3000.6,3010.1,3019.4
XS GIS Cut Line= 5
     1496103.438      213917.999     1496667.674      214536.488
     1497014.896      215230.933     1497286.163      215632.408
     1497297.014      217574.683
#Sta/Elev= 30
       0  845.33    38.9  840.41   204.4  896.23   486.7   953.9   564.6  927.94
   691.2  858.97     847  757.01   984.6  687.86  1210.7  644.62  1240.1     642
  1348.2  643.65  1446.5  662.24  1729.9  681.75  1826.8  712.24  1933.4  771.85
  2098.1  831.87  2245.3  804.88  2431.7  710.93  2451.3  707.81  2598.4  758.05
  2696.5  806.09    2775  816.46  2951.6   775.3  3226.2  767.92  3265.5  757.97
  3334.2  791.87  3451.9  823.63  3657.9  852.05  3844.2  909.42  4040.4  943.41
#Mann= 3 , 0 , 0
       0    .065       0  1210.7    .045       0  1348.2     .08       0
Bank Sta=1210.7,1348.2
XS Rating Curve= 0 ,0
Exp/Cntr=0.3,0.1

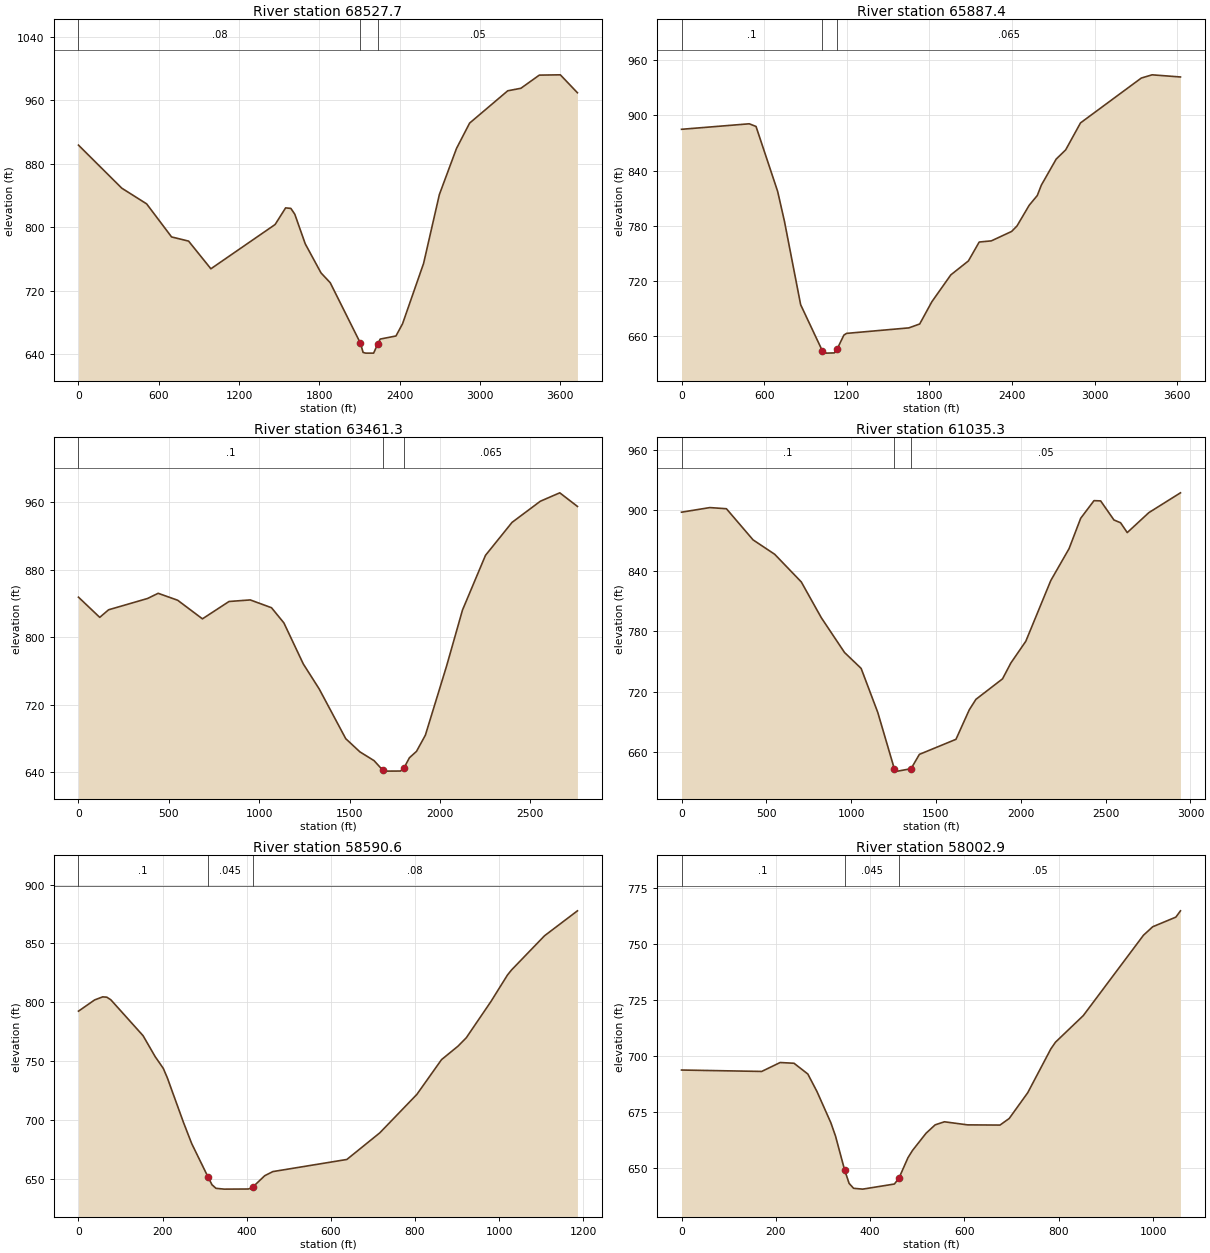
Type RM Length L Ch R = 1 ,68527.7 ,2646.4,2640.3,2634.2
XS GIS Cut Line= 4
     1495810.469      215154.978     1495441.545      216869.388
     1495452.396      217596.384     1495474.097      218844.214
#Sta/Elev= 30
       0  903.26   323.3  849.11   509.4  829.31   695.6  787.69   822.9  782.43
   989.5  747.58  1469.5  803.33  1547.9  824.26  1587.1  823.61  1616.5  816.31
  1694.9   778.9  1812.6  742.38  1881.4  730.03  2107.4  653.81    2127  642.26
  2146.7   641.4  2205.6   641.4  2235.1  652.44  2254.8  659.08  2372.6  662.99
  2421.8  678.35    2579  754.32  2696.9  841.02  2824.7  898.96  2922.9  930.98
  3207.9  971.68  3306.2  974.84  3443.8  991.41    3601  991.78  3728.8  969.21
#Mann= 3 , 0 , 0
       0     .08       0  2107.4    .045       0  2235.1     .05       0
Bank Sta=2107.4,2235.1
XS Rating Curve= 0 ,0
Exp/Cntr=0.3,0.1

Type RM Length L Ch R = 1 ,65887.4 ,2427.6,2426.1,2424.5
XS GIS Cut Line= 5
     1493607.778       214569.04     1493737.986      215154.978
     1493922.448       215816.87     1494172.014      216500.464
     1494508.386      218073.815
#Sta/Elev= 30
       0  884.87     492  890.86   541.2  887.97   698.4  817.24   747.5   784.9
   865.3  694.07  1022.3  644.11  1051.8   641.4  1110.7  641.63  1130.3  645.87
  1179.4  661.02    1199  662.88  1651.2  668.86  1729.9   673.1  1818.4  697.32
  1956.1  726.53  2083.7  741.69  2162.2  762.25  2250.5  763.52  2397.7  773.76
  2436.9  779.78  2525.2  802.23  2584.1  812.86  2613.5  824.14  2721.4  852.48
  2790.1  862.45    2898  891.84  3339.5  940.61    3418  944.13    3624  941.79
#Mann= 3 , 0 , 0
       0      .1       0  1022.3    .045       0  1130.3    .065       0
Bank Sta=1022.3,1130.3
XS Rating Curve= 0 ,0
Exp/Cntr=0.3,0.1

Type RM Length L Ch R = 1 ,63461.3 ,2405.5,2426,2446.2
XS GIS Cut Line= 4
     1492555.261      216012.183      1493010.99       216912.79
     1493379.913      217976.158     1493531.823      218583.797
#Sta/Elev= 30
       0  847.69   117.6  823.76   166.6  832.73   382.2  846.14     441  852.28
   548.8  844.06     686  821.99     833  842.57   950.6  844.43  1068.1  835.19
  1136.6  817.23  1244.2  768.48  1332.3  738.79  1479.1  679.85  1557.4  664.24
  1635.7  653.85  1684.7  642.32  1694.5   641.4  1782.6  641.51  1802.1  645.54
  1831.5  657.27  1870.6  664.85  1919.6     684    2037  765.99  2125.1  832.43
  2252.3  897.28  2399.1  936.34  2555.7  961.45  2663.4  971.44  2761.2  955.31
#Mann= 3 , 0 , 0
       0      .1       0  1684.7    .045       0  1802.1    .065       0
Bank Sta=1684.7,1802.1
XS Rating Curve= 0 ,0
Exp/Cntr=0.3,0.1

Type RM Length L Ch R = 1 ,61035.3 ,2446.3,2444.8,2443.1
XS GIS Cut Line= 4
     1491813.073      215451.419     1491370.365      216180.585
     1490966.719      216818.606     1490680.261       218120.69
#Sta/Elev= 30
       0  898.08   166.7  902.65   264.7  901.51   421.6  870.67   549.1  856.39
     706  828.96   823.6   793.6   960.9  759.01  1058.9  743.22    1157  699.54
    1255  643.42  1274.6   641.4  1353.1  643.81  1402.1     658  1617.8  672.93
  1696.2  702.16  1735.5  712.56  1892.3  732.88  1941.3  748.56  2029.6  770.16
  2176.6  830.26  2284.4  861.91  2353.1  892.05  2431.5  909.54  2470.7  909.27
  2549.1  890.37  2588.3   887.6  2627.5  877.87    2755  897.67  2941.2  917.28
#Mann= 3 , 0 , 0
       0      .1       0    1255    .045       0  1353.1     .05       0
Bank Sta=1255,1353.1
XS Rating Curve= 0 ,0
Exp/Cntr=0.3,0.1

Type RM Length L Ch R = 1 ,58590.6 ,591.3,587.6,584
XS GIS Cut Line= 4
     1489516.343       214723.41     1489406.968      214869.243
     1489264.896      215132.408     1488910.729      215741.783
#Sta/Elev= 30
       0   792.5    38.4  802.04    57.6  804.63    67.2  804.37    76.8  802.19
   153.5  771.69   182.3  753.89   201.6  743.92   211.2  735.92   249.8  697.84
   269.1   680.1   307.7   651.9   317.4   645.1     327  642.07   346.3   641.4
   404.2   641.5   413.8  642.96   442.8   652.8   462.1  656.29     638  666.58
   716.3  689.17   804.4   721.8   863.1  751.35   902.3  762.79   921.9  769.89
   980.6   800.7  1019.8  823.16  1029.6   827.5  1107.9  856.49  1186.2  877.68
#Mann= 3 , 0 , 0
       0      .1       0   307.7    .045       0   413.8     .08       0
Bank Sta=307.7,413.8
XS Rating Curve= 0 ,0
Exp/Cntr=0.3,0.1

Type RM Length L Ch R = 1 ,58002.9 ,117.9,117.9,117.9
XS GIS Cut Line= 5
     1489052.801      214592.333     1488899.445      214665.829
     1488786.597      214774.335     1488717.153      214973.988
     1488556.563       215468.78
#Sta/Elev= 30
       0  693.67   170.1  693.04   209.2  697.03   238.6   696.7   267.9  691.89
   287.5  683.96   316.8  670.05   326.6  664.14   345.8  649.07   355.4  642.97
     365  640.76   384.3   640.4   451.5  642.68   461.1   645.3   480.3  654.47
     490  657.73   518.8  665.44     538  669.16   557.6  670.52   606.7  669.14
   675.4  669.05     695     672   734.3  683.53   783.4  703.16   793.2  706.14
   852.1  718.02   979.7  753.96   999.3  757.75  1048.4  762.06  1058.2  764.88
#Mann= 3 , 0 , 0
       0      .1       0   345.8    .045       0   461.1     .05       0
Bank Sta=345.8,461.1
XS Rating Curve= 0 ,0
Exp/Cntr=0.3,0.1

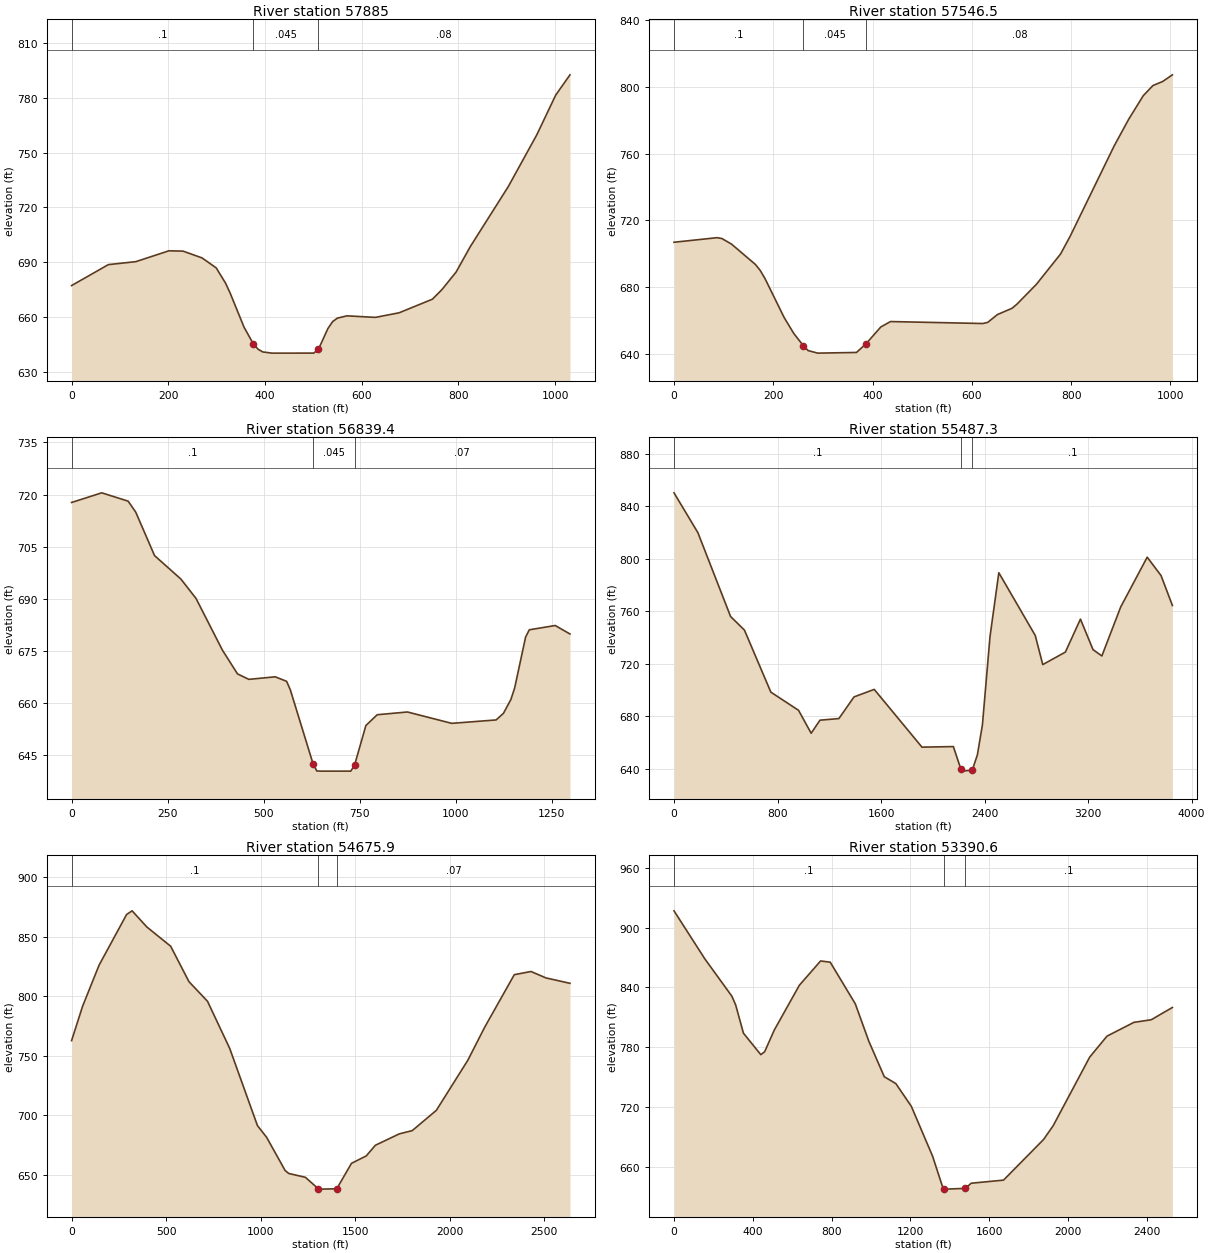
Type RM Length L Ch R = 1 ,57885   ,334.3,338.5,342.9
XS GIS Cut Line= 5
     1488933.009      214488.166     1488810.903      214561.662
     1488698.056      214670.169     1488628.611      214869.822
     1488468.021      215364.613
#Sta/Elev= 30
       0  677.32      76  688.77     133   690.4   201.2  696.32   230.6  696.14
   269.7  692.45   299.1  686.99   318.3  678.69   327.9  673.25   356.7  654.54
   375.9  645.45   385.6  642.55   395.2  641.06   414.4   640.4   500.8  640.41
   510.5  642.51   530.1  653.84   539.9  657.64   549.7  659.53   569.4  660.78
   628.2  659.93   677.3  662.44     746  669.85   765.6  675.03   795.1  684.67
   824.5  698.59   903.1  731.42     962  759.67  1001.2  781.43  1030.7   792.5
#Mann= 3 , 0 , 0
       0      .1       0   375.9    .045       0   510.5     .08       0
Bank Sta=375.9,510.5
XS Rating Curve= 0 ,0
Exp/Cntr=0.3,0.1

Type RM Length L Ch R = 1 ,57546.5 ,702.1,707,711.9
XS GIS Cut Line= 3
     1488490.301      214397.021     1488348.229      214660.186
     1487994.063      215269.561
#Sta/Elev= 30
       0  706.84    86.8  709.58    96.5  709.06   115.8  705.74     164  693.53
   173.6  689.97   183.3  685.07   221.9  661.72   241.2  652.21   260.5  644.86
   270.1  641.94   289.4   640.4   367.6   640.8   387.2  646.14   416.5  656.06
   436.1  659.32   622.1  658.14   631.9  658.82   651.5  663.52   680.8  667.25
   690.6  669.69   729.8  681.58   778.7  699.82   798.3  710.64   886.4  764.44
   915.8  780.51   945.2  794.65   964.7  800.74   984.3  803.17  1003.9  807.16
#Mann= 3 , 0 , 0
       0      .1       0   260.5    .045       0   387.2     .08       0
Bank Sta=260.5,387.2
XS Rating Curve= 0 ,0
Exp/Cntr=0.3,0.1

Type RM Length L Ch R = 1 ,56839.4 ,1309.9,1352.2,1394.1
XS GIS Cut Line= 4
     1488302.141       214321.38     1487816.029      214251.936
     1487559.085      214536.658     1487306.273      214876.187
#Sta/Elev= 30
       0  717.71    78.6  720.49   147.3  718.09     167  714.95   216.1  702.42
   284.8  695.66   324.1  690.09   392.8  675.22   432.1  668.38   461.6  666.81
   530.4  667.54   559.9  666.25   569.7  663.78   628.7  642.56   638.6  640.44
   648.4   640.4   727.1   640.4   736.9  642.12   766.4  653.53   795.9  656.63
   874.6  657.42     990  654.15  1105.5  655.13  1124.7  657.04    1144  661.02
  1153.6  664.23  1182.4     679    1192  681.07  1259.4  682.31  1297.9  679.87
#Mann= 3 , 0 , 0
       0      .1       0   628.7    .045       0   736.9     .07       0
Bank Sta=628.7,736.9
XS Rating Curve= 0 ,0
Exp/Cntr=0.3,0.1

Type RM Length L Ch R = 1 ,55487.3 ,817.2,811.3,805.1
XS GIS Cut Line= 6
     1490007.002      214753.672     1488999.189      214497.596
     1488708.757      214318.527       1487997.8       213454.28
     1487414.467      213693.863     1486933.009      214216.465
#Sta/Elev= 30
       0  850.08   184.6  819.74   437.3  755.86   544.2  745.54   748.4  698.26
   962.4  684.43  1059.8  666.96    1128   676.9  1274.2  678.14  1391.2  694.64
  1547.2  700.35  1916.2  656.36  2158.6   656.8  2217.2  639.48    2227   638.1
    2305  638.88  2344.1  650.41  2383.1  673.25  2441.7   740.5    2510  789.21
  2791.3  741.44  2849.5  719.26  3024.2  728.76  3140.6  753.87  3237.9  730.63
  3306.1  725.83  3452.1  763.21  3656.5  801.06  3763.6  787.05  3851.2  764.28
#Mann= 3 , 0 , 0
       0      .1       0  2217.2    .045       0    2305      .1       0
Bank Sta=2217.2,2305
XS Rating Curve= 0 ,0
Exp/Cntr=0.3,0.1

Type RM Length L Ch R = 1 ,54675.9 ,1329.3,1285.4,1241.2
XS GIS Cut Line= 6
     1490053.356      213888.307     1489436.777      213815.949
     1489209.606      213700.807     1488720.022      213225.113
     1488567.245      213249.419      1487654.05      213381.363
#Sta/Elev= 30
       0  762.81    58.2  791.68   145.5   826.2     291  868.75   320.1  871.81
   397.7  858.28   523.8   842.1   620.8   812.3   718.8  795.85   836.3  756.22
   982.8  691.46  1031.5  681.59    1129   653.8  1148.5  651.23  1236.3  648.04
  1304.6   638.4  1314.3   638.1  1402.1  638.37  1480.1  659.77  1558.1  665.97
  1606.5  674.93  1732.4  684.47  1801.2  687.23  1928.8  704.25  2095.6   746.4
    2184  773.93    2341  818.18  2429.4  820.86  2507.9  815.49  2635.5  810.94
#Mann= 3 , 0 , 0
       0      .1       0  1304.6    .045       0  1402.1     .07       0
Bank Sta=1304.6,1402.1
XS Rating Curve= 0 ,0
Exp/Cntr=0.3,0.1

Type RM Length L Ch R = 1 ,53390.6 ,1486.3,1470.4,1453.9
XS GIS Cut Line= 5
     1489268.079      211751.187     1488547.593      212428.271
     1488353.219      212910.318     1488268.634      213186.919
       1487560.3      213370.946
#Sta/Elev= 30
       0  916.73   156.6  868.61   293.7  831.26   313.2  822.38   352.4  794.26
   440.5  772.73   460.1  775.67     509  797.35   636.3  842.23     744  866.54
   792.9  865.31   920.2  823.62   988.7  786.24  1067.2  750.66    1126  743.75
  1204.5  721.04  1312.3  671.16  1361.4  641.46  1371.2   638.5    1381   638.1
    1479  638.88  1508.5  644.02  1672.4   647.1  1875.8   687.8  1924.6  701.64
    2110  770.32  2197.8  791.28  2334.4  805.08  2422.2  807.68  2529.6  819.97
#Mann= 3 , 0 , 0
       0      .1       0  1371.2    .045       0    1479      .1       0
Bank Sta=1371.2,1479
XS Rating Curve= 0 ,0
Exp/Cntr=0.3,0.1

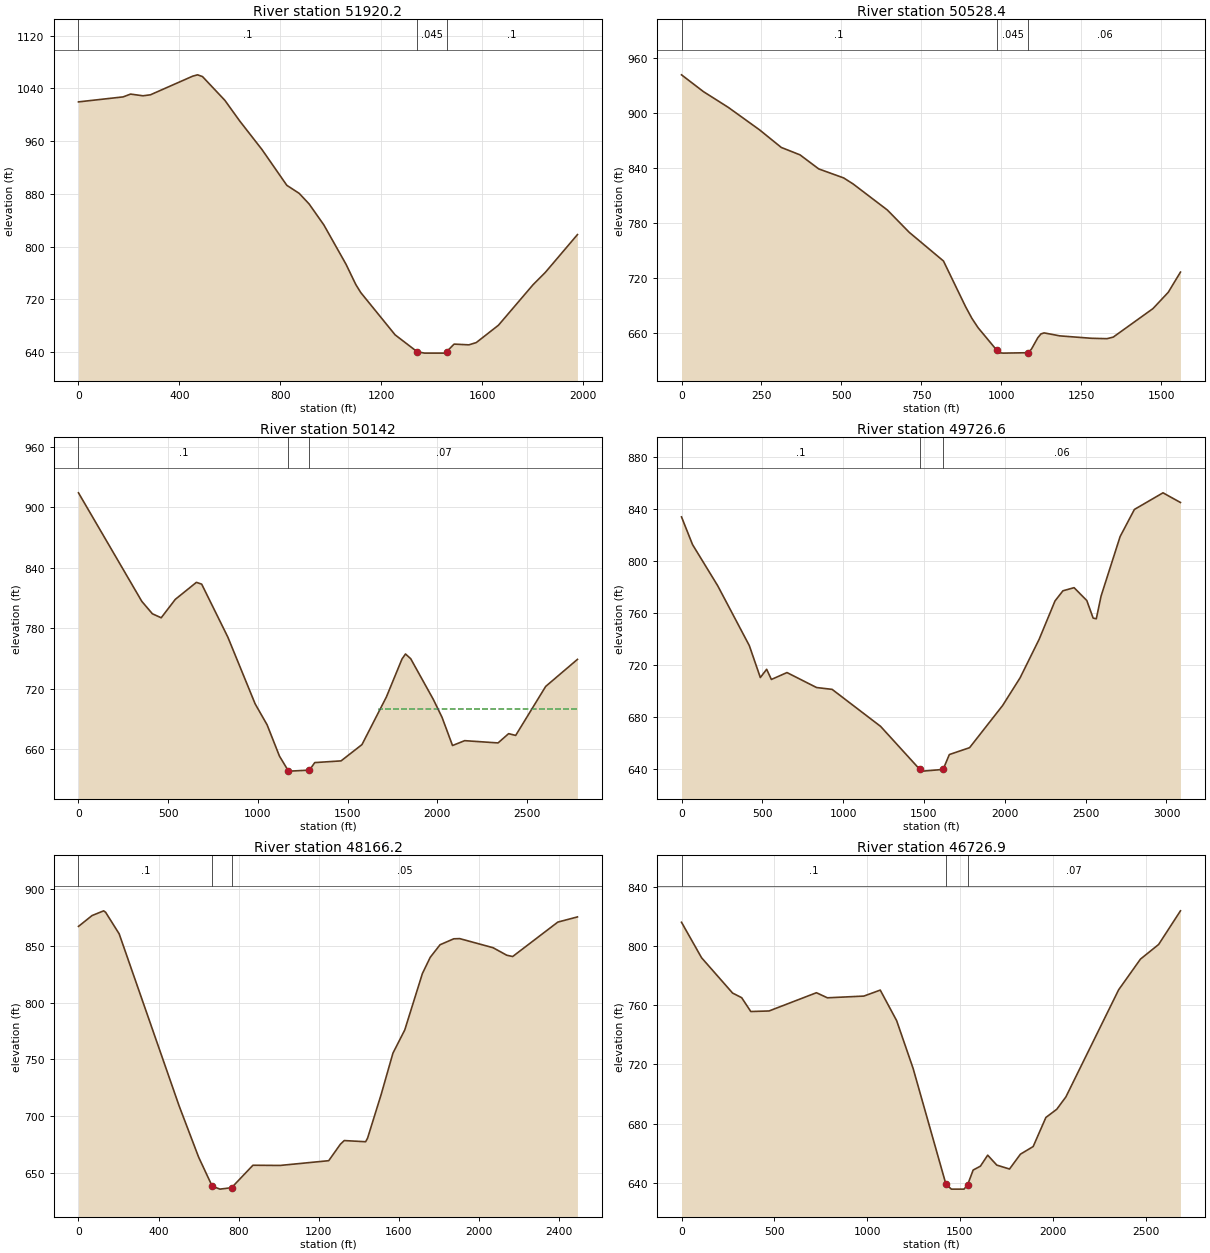
Type RM Length L Ch R = 1 ,51920.2 ,1413.6,1391.8,1369.9
XS GIS Cut Line= 4
     1486403.495      211725.146     1486811.482      212532.437
     1487002.454      213105.354     1487158.704      213548.062
#Sta/Elev= 30
       0  1019.6     177 1027.18   206.5 1031.45   255.6 1028.86   285.1 1030.34
   452.3 1058.58   471.9 1060.69   491.6 1058.01   580.1 1022.04   639.1  990.62
   727.6  947.11   825.9   892.9     875  880.66   914.3  864.57   972.7  832.76
  1060.4  773.15  1099.3  742.28  1118.8  730.16  1255.2  665.83  1342.8  640.16
  1372.1   638.1    1450   638.1  1459.7  640.48    1489  651.78  1547.6  650.68
  1576.9  654.14  1664.9   680.5  1801.9  741.95  1850.8  760.76  1977.9  818.07
#Mann= 3 , 0 , 0
       0      .1       0  1342.8    .045       0  1459.7      .1       0
Bank Sta=1342.8,1459.7
XS Rating Curve= 0 ,0
Exp/Cntr=0.3,0.1

Type RM Length L Ch R = 1 ,50528.4 ,383.5,386.4,389.4
XS GIS Cut Line= 4
     1485781.534      213372.281     1486111.395      214122.281
     1486611.829      214268.548     1486828.843      214303.271
#Sta/Elev= 30
       0  941.66    68.3   923.4   146.3  906.16   243.8  881.71   312.1  862.44
   370.6  854.37   429.2  839.02   507.2  829.19   536.5  822.68   643.8  794.21
     712  769.93   819.3  738.57   888.2  688.92   907.9   676.2   927.5  665.83
   986.6  641.02   996.4  638.41  1006.2   638.1  1084.9  638.56  1094.8  642.72
  1114.4  654.92  1124.3  659.08  1134.1  660.17  1183.3  656.91  1281.7   654.3
  1330.9  653.87  1350.3  655.58  1474.5  686.68  1522.3  704.44  1560.5  726.46
#Mann= 3 , 0 , 0
       0      .1       0   986.6    .045       0  1084.9     .06       0
Bank Sta=986.6,1084.9
XS Rating Curve= 0 ,0
Exp/Cntr=0.3,0.1

Type RM Length L Ch R = 1 ,50142   ,401.7,415.4,428.9
XS GIS Cut Line= 6
     1485684.311      213532.003     1486100.978      214497.281
     1486434.311      214643.114     1486830.145      214775.059
     1487100.978      215066.726     1487406.534      215525.059
#Sta/Elev= 30
       0  914.18   353.2  806.46   412.1  794.18   461.1  790.22   539.6  808.48
   657.4  825.38   686.8  823.58   832.3  771.18   984.8  704.84  1051.6  683.99
  1120.4  652.98  1169.6  638.46  1179.4   638.1  1287.6   639.1  1317.1  646.57
  1463.9  648.26  1580.4  664.43  1716.2  711.57  1803.6  749.37    1823   754.3
  1852.1   749.6  1978.3  709.17  2026.8  691.45  2085.1   663.5    2153  668.32
  2338.9  666.08  2397.9  675.28  2437.2  673.51  2604.5  722.14  2781.5  748.95
#Mann= 3 , 0 , 0
       0      .1       0  1169.6    .045       0  1287.6     .07       0
#XS Ineff= 2 , 0
                         1675.59          699.51
Permanent Ineff=
       F       F
Bank Sta=1169.6,1287.6
XS Rating Curve= 0 ,0
Exp/Cntr=0.3,0.1

Type RM Length L Ch R = 1 ,49726.6 ,1552.6,1560.4,1568
XS GIS Cut Line= 6
     1485392.645      213629.226     1485677.367      214129.226
     1485913.478      214504.226     1486087.089      214872.281
     1486350.978      215240.337     1486899.589      216316.726
#Sta/Elev= 30
       0  833.69    68.3  812.36   224.3  780.65   419.4  734.69   487.6   710.1
   526.6  716.47   555.9  708.62   652.4  713.93   835.5  702.41   931.8     701
  1231.7  672.51  1473.6  639.48  1492.9   638.1  1618.2   639.4  1656.7  650.85
    1782  656.14  1986.4   688.6  2094.4  709.88  2212.3  739.53  2310.5  769.06
  2359.6  776.85  2428.4  779.24    2507  769.37  2546.3  755.84  2565.9  755.32
  2595.4  772.79  2713.2  818.58  2801.6  839.44  2978.4  852.22  3086.5  844.79
#Mann= 3 , 0 , 0
       0      .1       0  1473.6    .045       0  1618.2     .06       0
Bank Sta=1473.6,1618.2
XS Rating Curve= 0 ,0
Exp/Cntr=0.3,0.1

Type RM Length L Ch R = 1 ,48166.2 ,1458.5,1439.2,1419
XS GIS Cut Line= 5
     1484804.971      213543.288     1485027.193      213994.677
     1485117.471      214411.344      1485256.36      214966.899
     1485791.082      215800.232
#Sta/Elev= 30
       0  867.15    67.7   876.7   125.8  880.87   135.5  879.59   203.2   860.6
   503.1  708.74     600  663.83   667.8  638.21   706.6   635.6   764.7  636.85
   871.3  656.64  1007.1  656.47  1249.8  660.66    1308  675.15  1327.4   678.4
  1434.2  677.37  1443.9   680.5  1511.9  719.08  1570.7  755.46  1629.6  775.84
  1717.8   825.6    1757  839.92    1806  850.98  1874.6  856.21    1904  856.39
  2070.7  848.37  2139.3  841.73  2168.7   840.6  2394.2  870.94  2492.2   875.5
#Mann= 3 , 0 , 0
       0      .1       0   667.8    .045       0   764.7     .05       0
Bank Sta=667.8,764.7
XS Rating Curve= 0 ,0
Exp/Cntr=0.3,0.1

Type RM Length L Ch R = 1 ,46726.9 ,577.8,601.2,624.3
XS GIS Cut Line= 4
     1483853.582      214300.232      1484256.36      215196.066
     1484513.304      215466.899     1485700.804      216071.066
#Sta/Elev= 30
       0  816.28     108  792.27     275  768.36   324.1  765.22   373.2  755.85
   471.5  756.23   726.8  768.58   785.8  765.14   982.2   766.3  1070.6  770.36
    1159  749.65  1247.5  717.39  1424.1  639.08  1453.5   635.6  1522.1   635.6
  1541.7  638.67  1571.1  648.52  1610.3  651.16  1649.4  658.59  1698.4  651.87
    1767  649.21  1825.8  659.27  1894.4  664.43  1962.9  684.12  2021.7   689.7
  2070.7  698.05  2354.8  770.55  2472.4  791.34  2570.3  801.25  2687.9  824.03
#Mann= 3 , 0 , 0
       0      .1       0  1424.1    .045       0  1541.7     .07       0
Bank Sta=1424.1,1541.7
XS Rating Curve= 0 ,0
Exp/Cntr=0.3,0.1