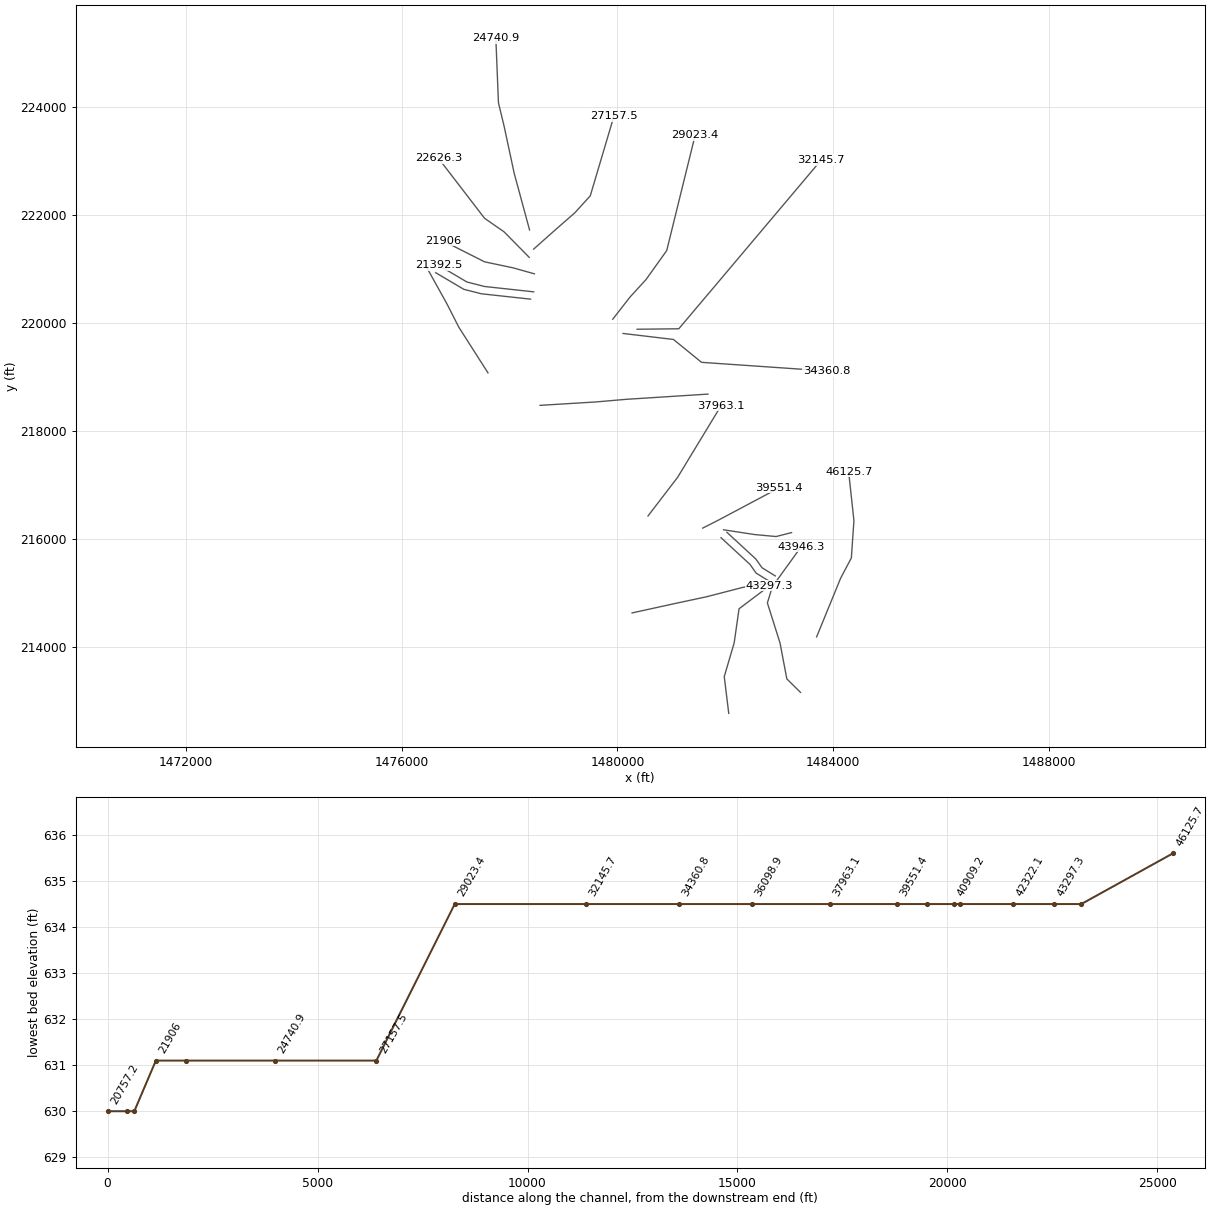
HEC-RAS study SFHGHSRV.prj: SFHGHSRV

--- SFHGHSRV.g01 (geometry) --- (continued)

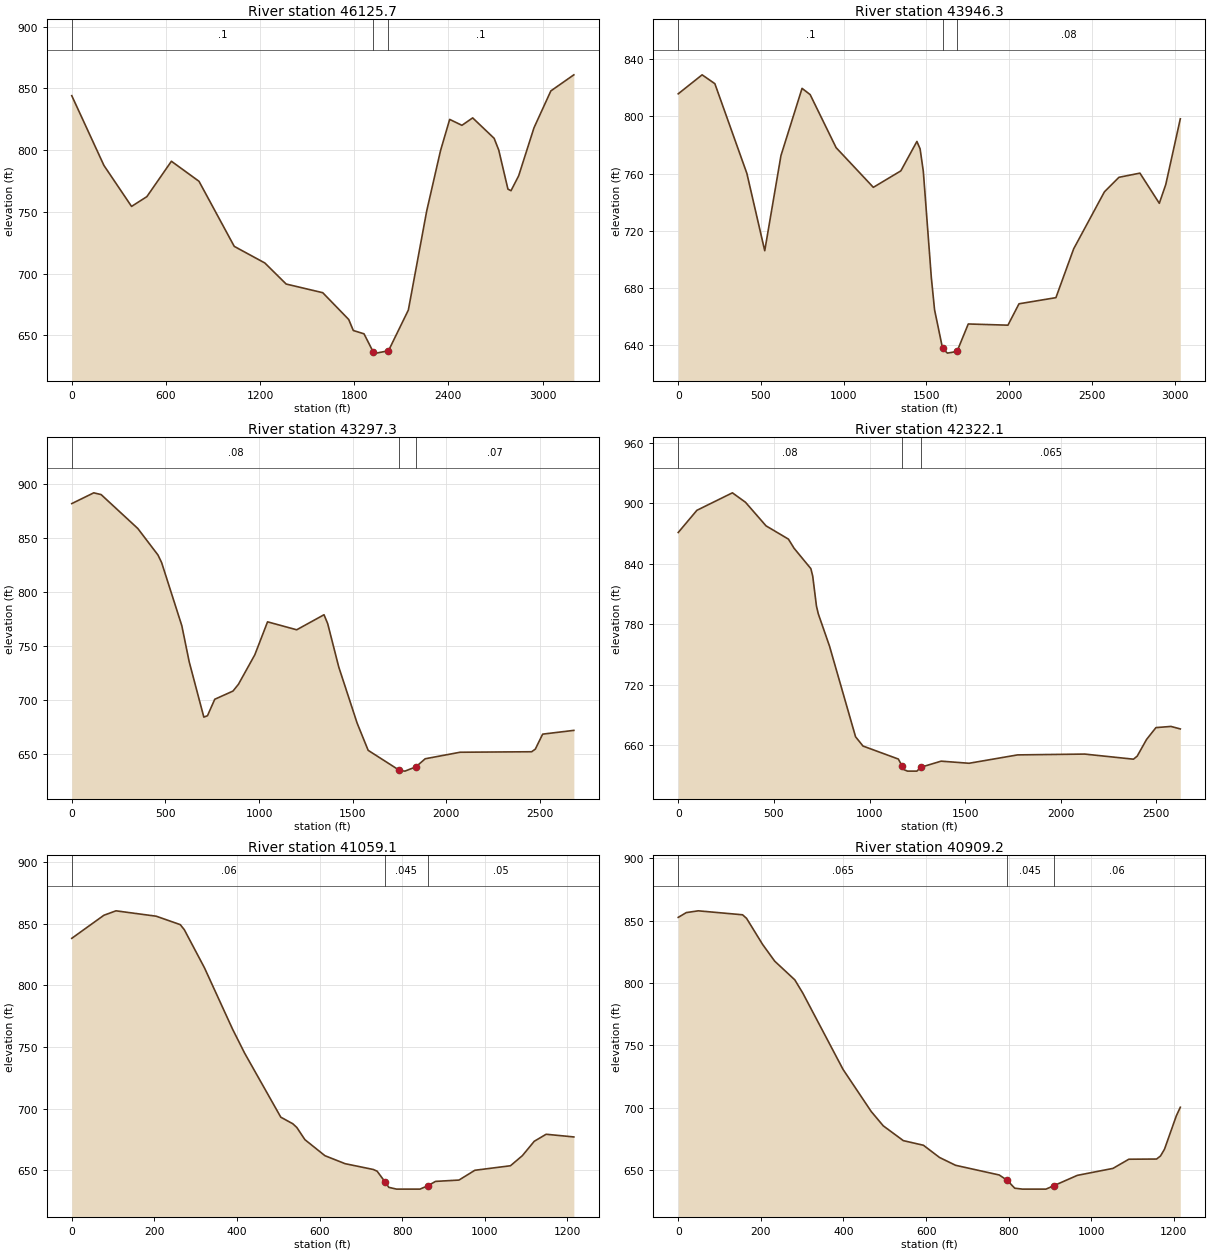
Type RM Length L Ch R = 1 ,46125.7 ,2171.5,2179.5,2187.4
XS GIS Cut Line= 5
     1483690.388      214195.776     1484134.606      215280.582
     1484334.259      215658.186     1484382.002       216348.29
     1484284.138      217251.621
#Sta/Elev= 30
       0  844.03   205.1  787.53     381  754.38   478.7   762.3     635  790.95
   810.8  774.73  1035.5  722.03  1230.5  708.58  1366.4  691.53  1599.4  684.53
    1765  662.83  1794.2  653.92  1862.4  651.24  1920.9  636.64  1940.4   635.6
  2018.3   637.5    2145  670.47  2261.9  750.65  2349.8  799.42  2408.4  824.83
  2486.5  820.04  2554.9  826.06  2691.7  809.52    2721  800.05  2779.6  768.41
  2799.2  767.11    2848  779.15  2945.7  818.04  3053.2   847.9  3199.7  860.92
#Mann= 3 , 0 , 0
       0      .1       0  1920.9    .045       0  2018.3      .1       0
Bank Sta=1920.9,2018.3
XS Rating Curve= 0 ,0
Exp/Cntr=0.3,0.1

Type RM Length L Ch R = 1 ,43946.3 ,658.6,649,638.9
XS GIS Cut Line= 6
     1483391.777      213167.999     1483138.304      213418.288
     1483012.376      214082.737     1482778.001      214824.925
     1482870.943      215126.332     1483402.193      215862.732
#Sta/Elev= 30
       0   815.8   144.4  829.07   221.4  822.87     415  760.09   522.8   706.1
   620.8  772.57   748.3  819.61   797.3  815.24   954.1  778.17  1179.2  750.41
  1345.5  761.92  1442.5   782.5  1461.9  777.26  1481.3  761.56  1529.8  687.19
  1549.2  664.81  1597.7  637.79  1626.8   634.5    1685  635.68  1752.9  654.88
  1992.7  654.04  2059.6  668.99  2282.7  673.28  2390.1  707.45  2575.6  747.23
  2663.5  757.42  2790.4  760.35  2907.6  739.25  2946.7  752.43  3034.5  798.32
#Mann= 3 , 0 , 0
       0      .1       0  1597.7    .045       0    1685     .08       0
Bank Sta=1597.7,1685
XS Rating Curve= 0 ,0
Exp/Cntr=0.3,0.1

Type RM Length L Ch R = 1 ,43297.3 ,1002.1,975.1,946.3
XS GIS Cut Line= 5
     1482061.916      212779.399     1481978.582      213459.955
      1482162.61      214084.665     1482252.888       214716.61
     1482816.196      215140.897
#Sta/Elev= 30
       0  881.71   117.5  891.66   156.7  890.03   352.6   858.7   460.4  834.17
     480  827.09   587.7  768.78   626.9  735.55   705.1  684.41   724.5  685.69
   763.4  700.91   860.6  708.46   889.8  714.74   977.2  741.98  1045.3  772.45
  1200.8   765.1  1346.7  778.99  1366.4  770.77  1425.3  730.79  1523.5  678.86
  1582.4  653.72  1749.4  635.22  1778.8   634.5  1837.8   638.5  1886.9  645.92
  2073.2  651.95  2455.2  652.41  2474.8  654.83    2514  668.68  2680.5  672.16
#Mann= 3 , 0 , 0
       0     .08       0  1749.4    .045       0  1837.8     .07       0
Bank Sta=1749.4,1837.8
XS Rating Curve= 0 ,0
Exp/Cntr=0.3,0.1

Type RM Length L Ch R = 1 ,42322.1 ,1289.4,1263,1236.5
XS GIS Cut Line= 5
     1480271.057       214639.74     1481034.138      214807.177
     1481652.193      214939.121     1482322.332      215112.443
     1482835.293      215194.717
#Sta/Elev= 30
       0   871.1    97.6  893.09   283.2  910.42   351.6  901.06     459  877.68
   576.2  864.51   605.5  855.48   693.4  835.24   703.1  827.85   722.6  798.14
   732.4  790.38     791  758.38   927.1  668.57     966  659.37  1150.7  646.48
  1170.2  639.64  1179.9  635.94  1199.3   634.5  1247.9   634.5  1267.4  638.27
  1374.3  644.38  1520.5  642.29  1773.9  650.59    2125   651.4  2379.9  646.34
  2399.5  649.36  2448.5  665.92  2497.5  677.64  2575.9  678.81  2624.9  676.33
#Mann= 3 , 0 , 0
       0     .08       0  1170.2    .045       0  1267.4    .065       0
Bank Sta=1170.2,1267.4
XS Rating Curve= 0 ,0
Exp/Cntr=0.3,0.1

Type RM Length L Ch R = 1 ,41059.1 ,149.9,149.9,149.9
XS GIS Cut Line= 4
     1481918.626      216033.258     1482455.084      215538.467
     1482569.668      215377.008     1482814.459      215225.967
#Sta/Elev= 30
       0  838.31    77.8  857.07     107  860.66   204.3   856.3   262.7  849.43
   272.5  845.29   321.1  814.45   389.2  764.55   418.4  745.04     506  692.97
   535.2  687.59   544.9  684.55   564.4  674.69     613  661.64   661.7  655.18
   729.8  650.47   739.2  649.07   758.1   640.5   767.5  635.94   786.4   634.5
   842.9   634.5   861.8  637.22   880.6  640.78   937.4  641.87   975.7  649.81
    1062   653.5  1090.8   661.7  1119.5  673.37  1148.3  679.09  1215.4  676.91
#Mann= 3 , 0 , 0
       0     .06       0   758.1    .045       0   861.8     .05       0
Bank Sta=758.1,861.8
XS Rating Curve= 0 ,0
Exp/Cntr=0.3,0.1

Type RM Length L Ch R = 1 ,40909.2 ,627,646.9,666.8
XS GIS Cut Line= 4
     1482028.001      216132.217     1482564.459      215637.425
     1482679.043      215475.967     1482923.834      215324.925
#Sta/Elev= 30
       0   852.7    19.5  856.54    48.6  857.96   155.7  854.78   165.4  851.92
   204.3  830.96   233.5  817.56   282.2  802.53   301.6  791.87     399  730.62
   467.1  696.86   496.3  685.33   544.9  673.44   593.6  669.72   632.5  659.92
   671.4  653.63   776.9  645.87   795.8  641.76   814.6  635.25   833.5   634.5
   890.1   634.5   908.9  637.22   966.1  645.55  1052.4  651.15  1090.8  658.51
  1157.9  658.66  1167.5  661.14  1177.1  666.54  1205.8  693.39  1215.4  700.24
#Mann= 3 , 0 , 0
       0    .065       0   795.8    .045       0   908.9     .06       0
Bank Sta=795.8,908.9
XS Rating Curve= 0 ,0
Exp/Cntr=0.3,0.1

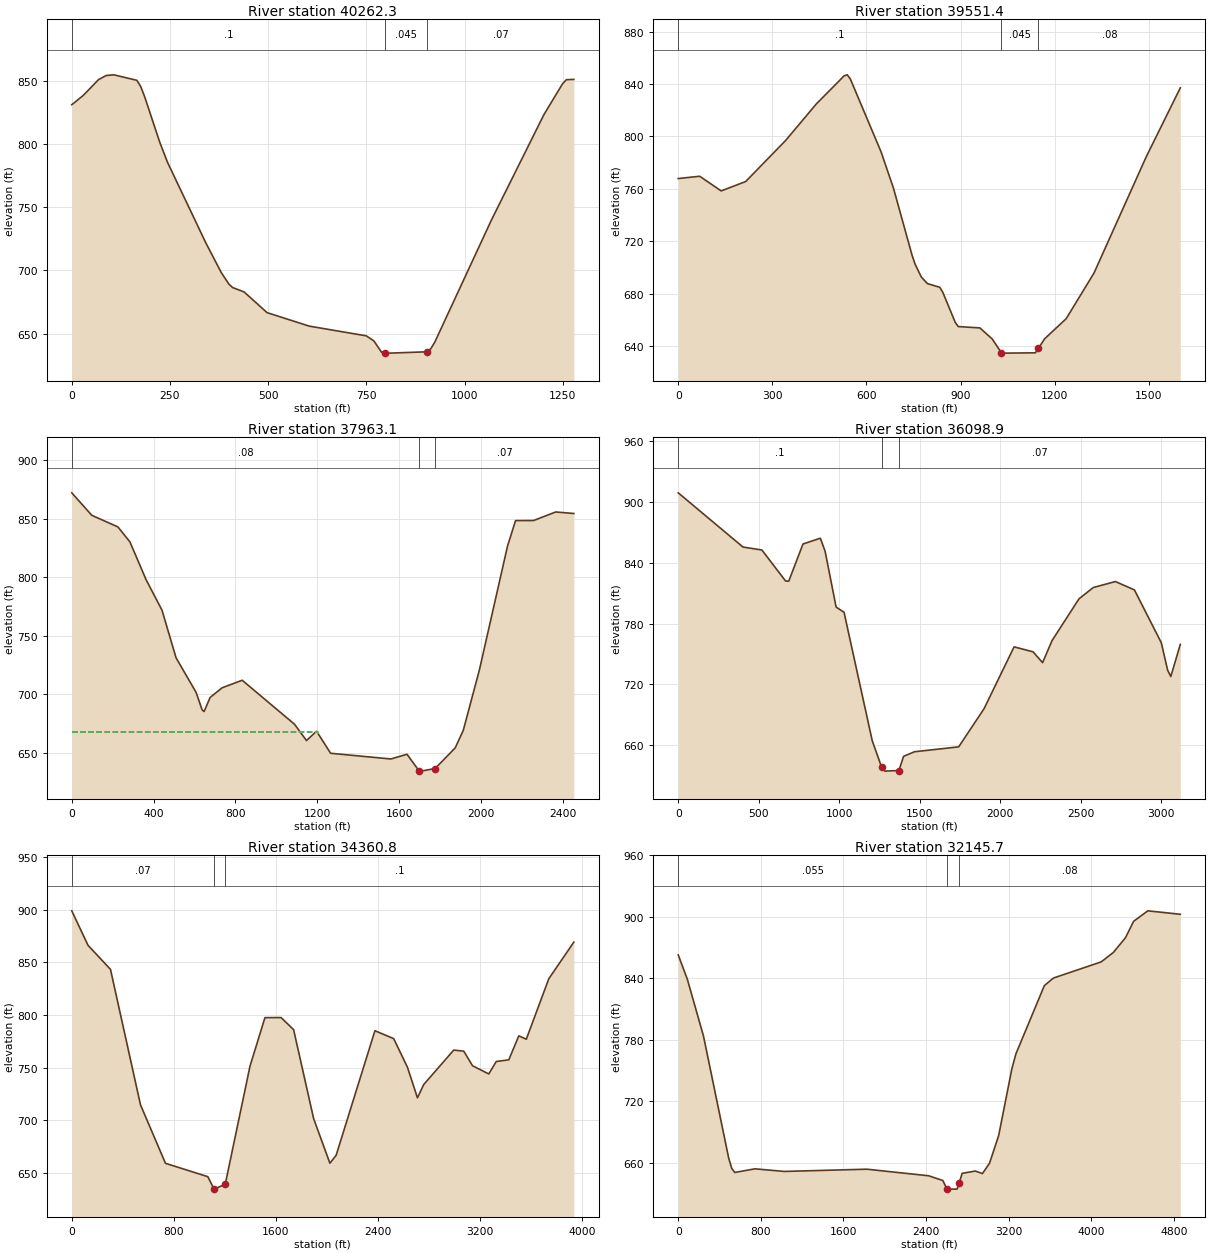
Type RM Length L Ch R = 1 ,40262.3 ,697.7,710.9,724.1
XS GIS Cut Line= 4
     1481965.501      216179.092     1482543.626       216090.55
     1482939.459      216054.092     1483225.918      216127.008
#Sta/Elev= 30
       0  831.12    29.2  838.47    68.2     851    87.7  854.25   107.2  854.79
   165.7  850.45   175.5  845.52   185.2  837.74   224.2  801.24   243.7  785.55
   341.2   721.8   380.2  698.47   399.7   689.2   409.4  686.42   438.6  682.96
   497.1  666.56   604.3  655.89   749.7  648.18   769.1  644.15   788.5  635.21
   798.2  634.54   807.9   634.5   904.8  635.56   914.5  638.27   924.2   643.3
  1068.2  739.84  1201.7   823.2  1249.4  847.78  1258.9  850.92    1278  851.18
#Mann= 3 , 0 , 0
       0      .1       0   798.2    .045       0   904.8     .07       0
Bank Sta=798.2,904.8
XS Rating Curve= 0 ,0
Exp/Cntr=0.3,0.1

Type RM Length L Ch R = 1 ,39551.4 ,1576.1,1588.3,1600.1
XS GIS Cut Line= 3
     1481580.084      216210.342     1481884.955      216365.532
     1482996.066       216955.81
#Sta/Elev= 30
       0  767.79    68.4  769.56   136.8  758.35     215  765.51   342.1  796.82
   440.4  824.83   528.9  846.24   538.7  846.99   548.5  843.86   646.8     788
   686.1   760.4   745.1  709.43   754.9  702.45   774.6  692.68   794.2   687.6
   833.6  684.77   843.4   680.9   882.7  658.11   892.6  654.77   961.4  653.76
  1000.7  645.35  1030.2   634.7    1040   634.5  1138.3  634.74  1148.1   638.2
  1167.8  645.42  1236.6  660.82    1325  695.53  1492.1  784.61  1600.3  837.06
#Mann= 3 , 0 , 0
       0      .1       0  1030.2    .045       0  1148.1     .08       0
Bank Sta=1030.2,1148.1
XS Rating Curve= 0 ,0
Exp/Cntr=0.3,0.1

Type RM Length L Ch R = 1 ,37963.1 ,1885.5,1864.2,1843
XS GIS Cut Line= 3
     1480565.511      216434.976     1481114.122      217150.254
     1481919.677      218476.643
#Sta/Elev= 30
       0  871.93      98  852.73   225.4  842.85   284.2  830.07   362.5  798.08
   440.9  771.82   509.5  731.22   607.5  701.69   636.9  686.75   646.7  685.38
   676.1  697.38   734.9  705.62   832.8  712.03  1088.1  674.54    1147   660.6
  1196.1  668.56  1264.8  649.74  1559.5  644.86  1638.1   648.9    1697  634.69
  1706.8   634.5  1775.6  636.74  1873.8  654.38  1913.1  669.32  1991.7  720.75
  2129.2  826.45  2168.5  848.24  2256.8  848.32  2364.9   855.6  2453.3  854.29
#Mann= 3 , 0 , 0
       0     .08       0    1697    .045       0  1775.6     .07       0
#XS Ineff= 2 , 0
         1204.01  667.65
Permanent Ineff=
       F       F
Bank Sta=1697,1775.6
XS Rating Curve= 0 ,0
Exp/Cntr=0.3,0.1

Type RM Length L Ch R = 1 ,36098.9 ,1754.7,1738.1,1719.6
XS GIS Cut Line= 4
     1478565.511      218483.588     1479593.289      218546.088
     1480155.789      218594.699     1481676.622      218691.921
#Sta/Elev= 30
       0  908.97   402.1  855.51   519.7  852.57   666.8  821.98   686.4  821.82
   774.7   858.5   882.6   864.2     912  851.48   980.6  796.28  1029.7  791.21
  1204.9  664.47  1263.3  638.38  1282.8   634.5  1370.4  635.09  1399.6  649.11
  1467.7  653.62  1741.8  658.44  1899.1     696  2085.9  757.07  2203.8  752.16
  2262.8  741.47  2321.8   763.3    2489  804.42  2577.5  815.57  2715.1  821.47
  2833.1  813.25  3000.2  761.12  3039.6  734.02  3059.2  727.83  3118.2   759.5
#Mann= 3 , 0 , 0
       0      .1       0  1263.3    .045       0  1370.4     .07       0
Bank Sta=1263.3,1370.4
XS Rating Curve= 0 ,0
Exp/Cntr=0.3,0.1

Type RM Length L Ch R = 1 ,34360.8 ,2179.1,2215.1,2251.1
XS GIS Cut Line= 4
     1480103.271      219814.751     1481037.299       219703.64
     1481558.132      219280.028     1483877.577      219120.306
#Sta/Elev= 30
       0  898.93   127.4  866.19   303.7  843.29   538.9  714.58   734.8  659.02
  1067.1  646.32  1115.8   634.5  1203.3  639.09  1397.9   751.5  1514.7  797.43
  1641.4  797.51  1739.5  786.04  1896.4  701.56    2024  659.15    2073  666.65
  2377.1  784.99  2524.3   777.5  2632.2  750.29  2710.7  721.25  2759.7  733.87
  2995.2  766.61  3073.6   765.6  3142.3  751.76  3269.8  743.93  3328.7  755.76
  3426.8  757.34  3505.3  780.14  3564.1  776.94  3740.7  834.42  3936.9  869.22
#Mann= 3 , 0 , 0
       0     .07       0  1115.8    .045       0  1203.3      .1       0
Bank Sta=1115.8,1203.3
XS Rating Curve= 0 ,0
Exp/Cntr=0.3,0.1

Type RM Length L Ch R = 1 ,32145.7 ,3122.2,3122.3,3120.7
XS GIS Cut Line= 4
     1480363.688      219892.876     1481136.257      219901.556
     1481848.063       220743.57     1483775.146      223026.556
#Sta/Elev= 30
       0  862.84      88  839.22   244.5  783.78     489  664.64   518.3  654.73
   547.7  650.74   743.3  654.29  1026.3  651.75  1826.4  653.94  2425.5  647.52
  2563.1  642.88  2602.4  634.53  2612.2   634.5  2700.7   634.5  2720.4  640.27
  2749.8  649.89  2877.6  652.14  2946.4  649.66  3015.2  659.79  3103.6   686.8
  3231.4   751.8  3270.7  766.44  3545.9  832.89  3634.3  840.33  4096.2  856.04
  4214.2  865.24  4332.1  879.68  4410.7  895.64  4548.3  905.85  4862.8  902.48
#Mann= 3 , 0 , 0
       0    .055       0  2602.4    .045       0  2720.4     .08       0
Bank Sta=2602.4,2720.4
XS Rating Curve= 0 ,0
Exp/Cntr=0.3,0.1

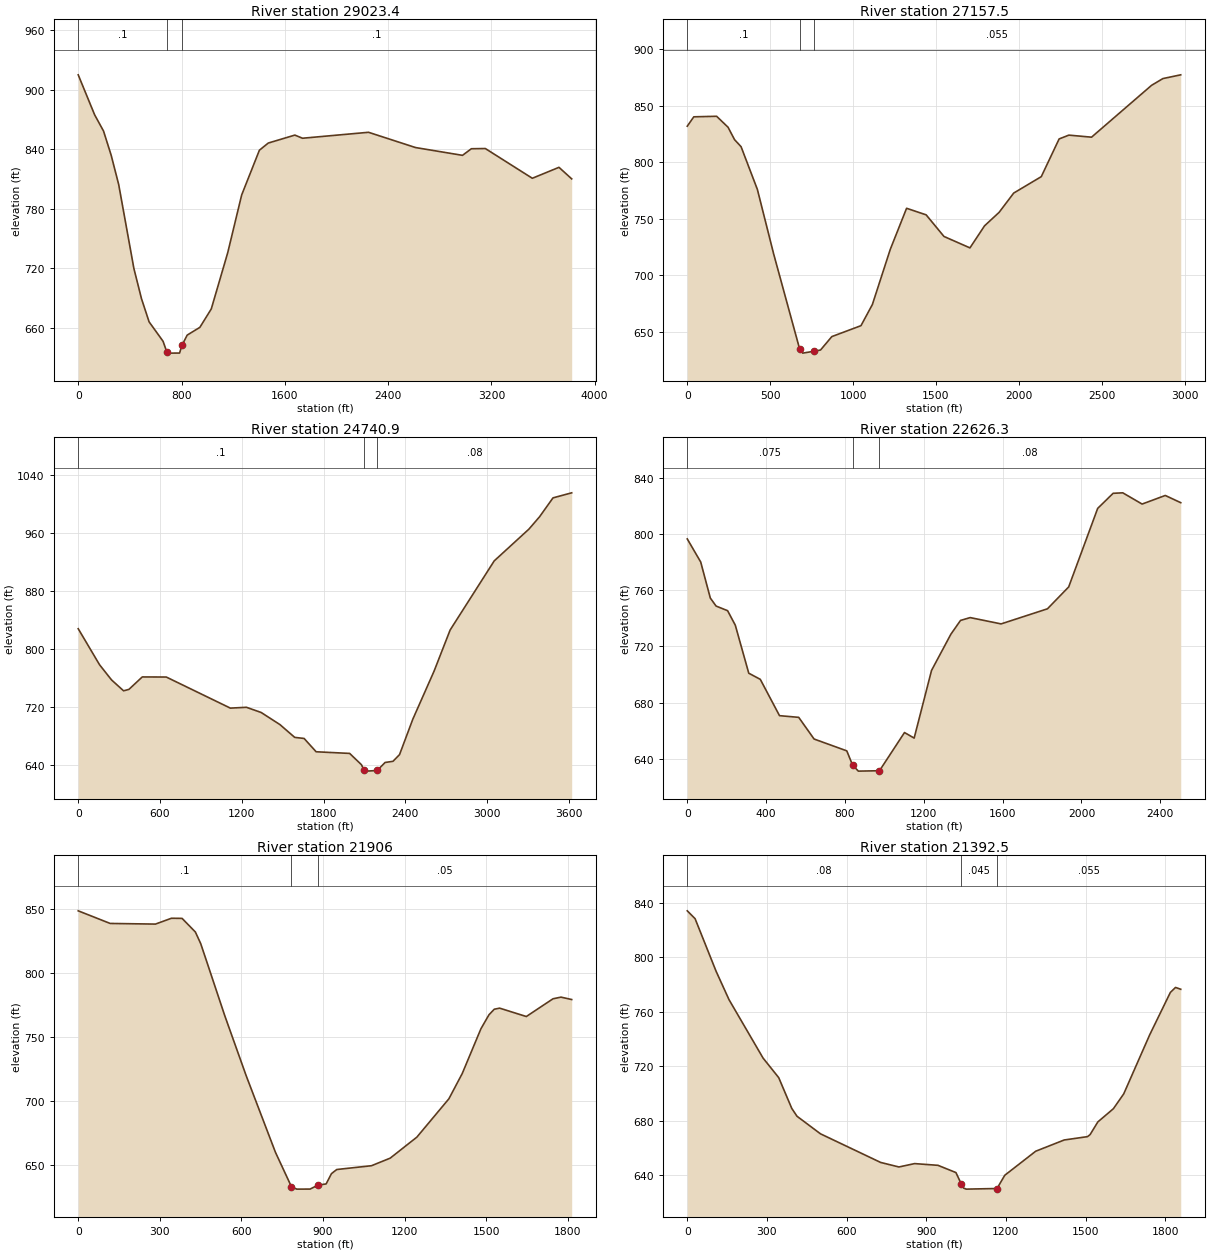
Type RM Length L Ch R = 1 ,29023.4 ,1868.3,1865.9,1862.6
XS GIS Cut Line= 5
     1479912.299       220078.64     1480231.743      220488.362
     1480530.355      220814.751     1480912.299      221349.473
     1481440.077      223488.362
#Sta/Elev= 30
       0  914.99   127.4  874.63     196  858.35   254.9  834.13   313.7  804.34
   431.3  719.76   490.1  689.39     549  666.03   657.2  646.44   686.7  635.51
   706.3   634.5     785  634.57   804.6  642.61     844  652.66   942.2  660.47
  1030.6  679.03  1158.1  735.74    1266  793.91  1403.3  838.99  1471.9  846.23
    1678  854.25  1737.1  851.08  2248.5  857.07  2612.4   841.7  2976.3  833.84
  3045.1  840.49  3153.3   840.7  3517.2  810.73  3723.7  821.76  3822.1  810.12
#Mann= 3 , 0 , 0
       0      .1       0   686.7    .045       0   804.6      .1       0
Bank Sta=686.7,804.6
XS Rating Curve= 0 ,0
Exp/Cntr=0.3,0.1

Type RM Length L Ch R = 1 ,27157.5 ,2421.5,2416.6,2470.3
XS GIS Cut Line= 5
     1478447.021      221377.251     1478822.021      221710.584
      1479210.91      222050.862     1479495.632      222363.362
     1479933.132      223835.584
#Sta/Elev= 30
       0   831.8    39.4  840.08   177.1  840.56     246  830.88   285.3  819.89
   324.6  813.67     423  775.88   521.2  718.81   677.2  635.16   696.7   631.1
     765  632.78     804  633.86   872.2  645.73    1048  655.37  1116.8  674.09
  1224.9  722.92  1323.2   759.2  1441.2  753.38  1548.8  734.27  1705.4  724.17
  1793.4  743.66  1881.4  755.61  1969.5  772.66  2135.8  787.18  2243.4  820.52
  2302.1  823.89    2439  822.08    2801  867.92  2869.5   873.9  2977.1  877.22
#Mann= 3 , 0 , 0
       0      .1       0   677.2    .045       0     765    .055       0
Bank Sta=677.2,765
XS Rating Curve= 0 ,0
Exp/Cntr=0.3,0.1

Type RM Length L Ch R = 1 ,24740.9 ,2044.7,2114.6,2073.4
XS GIS Cut Line= 5
     1478370.632      221731.417      1478085.91      222780.028
      1477898.41      223655.028     1477794.243      224085.584
     1477745.632      225280.028
#Sta/Elev= 30
       0     828   156.6  778.14   244.7  757.15   332.8  742.13     372  744.11
   469.9  761.32   646.1  761.18  1116.1  718.21  1234.1  719.35  1342.2  712.16
  1479.9  695.41  1588.1  677.75  1656.9  676.28  1745.4  657.85  1991.1  655.59
  2077.7  639.96    2097  632.41  2116.3   631.1  2193.3  631.99  2251.1  643.07
  2308.9  644.66    2357  653.93  2453.8  702.61  2610.6  769.45  2728.2   826.2
  3051.5  921.76  3306.3   965.7  3384.7  982.89  3482.7 1008.87  3619.8 1015.86
#Mann= 3 , 0 , 0
       0      .1       0    2097    .045       0  2193.3     .08       0
Bank Sta=2097,2193.3
XS Rating Curve= 0 ,0
Exp/Cntr=0.3,0.1

Type RM Length L Ch R = 1 ,22626.3 ,708.4,720.3,731.5
XS GIS Cut Line= 4
     1478363.688      221224.473      1477898.41      221696.695
     1477537.299      221946.695     1476683.132      223057.806
#Sta/Elev= 30
       0  796.58    68.2  780.13     117  754.43   146.2  748.73   204.7  745.43
   243.7   735.1     312  700.88   370.5  696.51     468  670.62   565.4  669.43
   643.4  653.98   809.3  645.54   838.6  635.45   867.9   631.1   975.2  631.38
  1102.1   658.6  1151.1  654.64  1239.3  702.86  1337.4  728.66  1386.4  738.49
  1435.4  740.51  1592.2  736.01  1827.4  746.77  1935.2  762.37  2082.2  818.32
  2160.6  829.08  2209.6  829.42  2307.6  821.41  2425.2  827.54  2503.6   822.4
#Mann= 3 , 0 , 0
       0    .075       0   838.6    .045       0   975.2     .08       0
Bank Sta=838.6,975.2
XS Rating Curve= 0 ,0
Exp/Cntr=0.3,0.1

Type RM Length L Ch R = 1 ,21906   ,513.4,513.6,513.4
XS GIS Cut Line= 4
      1478460.91      220918.917     1478065.077      221030.028
     1477537.299       221141.14     1476766.466      221530.028
#Sta/Elev= 30
       0  848.25   117.5   838.4   283.9   837.9   342.6  842.45   381.8  842.35
   430.7  831.72   450.4   822.6   538.6   766.5   617.1  719.77   724.9  659.88
   783.8  632.98   803.4   631.1   852.4  631.14   881.8  634.28   911.2  635.14
   930.9  643.19   950.5  646.41    1078  649.36  1146.7  655.26  1244.8  671.66
  1362.6  701.61  1411.6  721.31  1480.3  756.22  1509.7  767.09  1529.3  771.46
    1549  772.32  1647.1  765.78  1745.2  779.61  1774.6  780.91  1813.9  779.03
#Mann= 3 , 0 , 0
       0      .1       0   783.8    .045       0   881.8     .05       0
Bank Sta=783.8,881.8
XS Rating Curve= 0 ,0
Exp/Cntr=0.3,0.1

Type RM Length L Ch R = 1 ,21392.5 ,168.4,170.1,170.3
XS GIS Cut Line= 4
     1478447.021      220585.584     1477537.299      220684.542
     1477209.174      220767.876     1476688.341      221075.167
#Sta/Elev= 30
       0  834.14    29.5  828.37   108.2  789.98   157.4  768.92   285.4  726.15
   344.4  711.79   393.6   689.2   413.3  683.45   501.8  670.56   728.1  649.59
     797  646.25     856  648.72   944.1  647.46  1011.8  642.15  1031.2  634.09
  1040.8  630.78  1050.5     630  1166.6  630.45  1195.6  640.14  1312.2   657.8
  1419.4  666.04  1507.2   668.5    1517  669.98  1546.2  679.29  1604.8     689
  1643.8  699.91  1741.3  743.11  1819.3  774.28  1838.8  777.94  1858.4  776.62
#Mann= 3 , 0 , 0
       0     .08       0  1031.2    .045       0  1166.6    .055       0
Bank Sta=1031.2,1166.6
XS Rating Curve= 0 ,0
Exp/Cntr=0.3,0.1

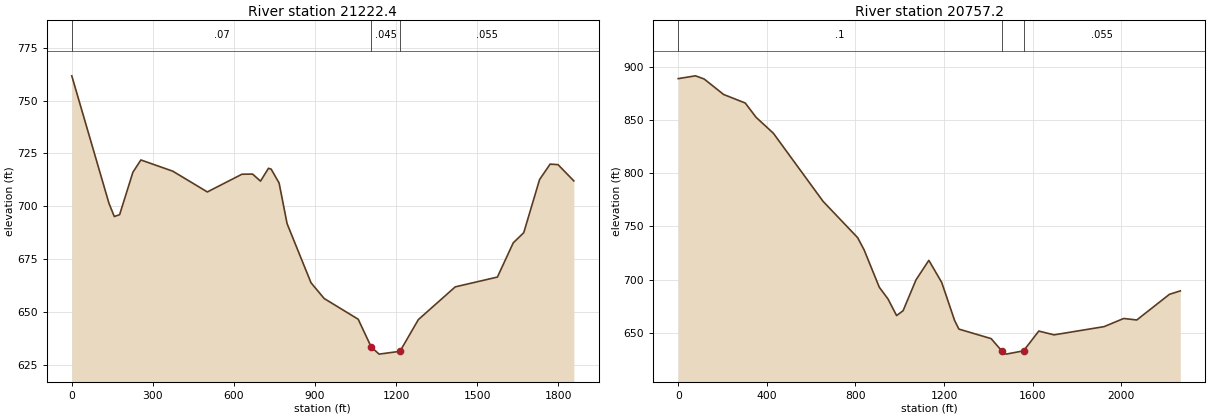
Type RM Length L Ch R = 1 ,21222.4 ,486.3,465.2,445.5
XS GIS Cut Line= 4
      1478389.73      220450.167     1477480.007      220549.126
     1477151.882      220632.459     1476631.049      220939.751
#Sta/Elev= 30
       0  761.75   137.8  701.37   157.4  695.15   177.1  696.01   226.3  716.11
   255.8  721.92   373.9  716.61   501.8  706.78   629.7  715.16   669.1  715.25
   698.6   711.9   728.1  717.98     738  717.59   767.5  710.99     797  691.76
   885.6  663.78   934.4  656.32  1060.2  646.52  1108.5  633.36  1137.6     630
  1214.9  631.33  1282.9  646.35  1419.4  661.84  1575.5  666.48    1634  682.66
    1673  687.51  1731.6  712.66  1770.6  719.95  1799.8  719.71  1858.4  712.01
#Mann= 3 , 0 , 0
       0     .07       0  1108.5    .045       0  1214.9    .055       0
Bank Sta=1108.5,1214.9
XS Rating Curve= 0 ,0
Exp/Cntr=0.3,0.1

Type RM Length L Ch R = 1 ,20757.2 ,915.4,899.2,879.4
XS GIS Cut Line= 4
     1477599.799      219085.584     1477058.132      219932.806
     1476842.855      220356.417      1476460.91      221043.917
#Sta/Elev= 30
       0   888.9    78.1  891.53   117.2  888.52     205     874   302.6  865.98
   351.5  852.56   429.6  837.57   654.1  773.57   810.3  739.42   839.6  727.86
     908  692.85     947  681.92     986  666.27  1015.3  670.76  1073.5   699.7
  1131.6  718.14  1189.8  697.38    1248  661.65  1267.4  653.52  1412.9  644.58
  1461.4  632.94  1480.8     630  1559.4  633.11  1628.2  651.67    1697  648.11
  1923.1  655.84  2011.6   663.5  2070.6  662.09  2218.1   686.2  2267.2  689.44
#Mann= 3 , 0 , 0
       0      .1       0  1461.4    .045       0  1559.4    .055       0
Bank Sta=1461.4,1559.4
XS Rating Curve= 0 ,0
Exp/Cntr=0.3,0.1