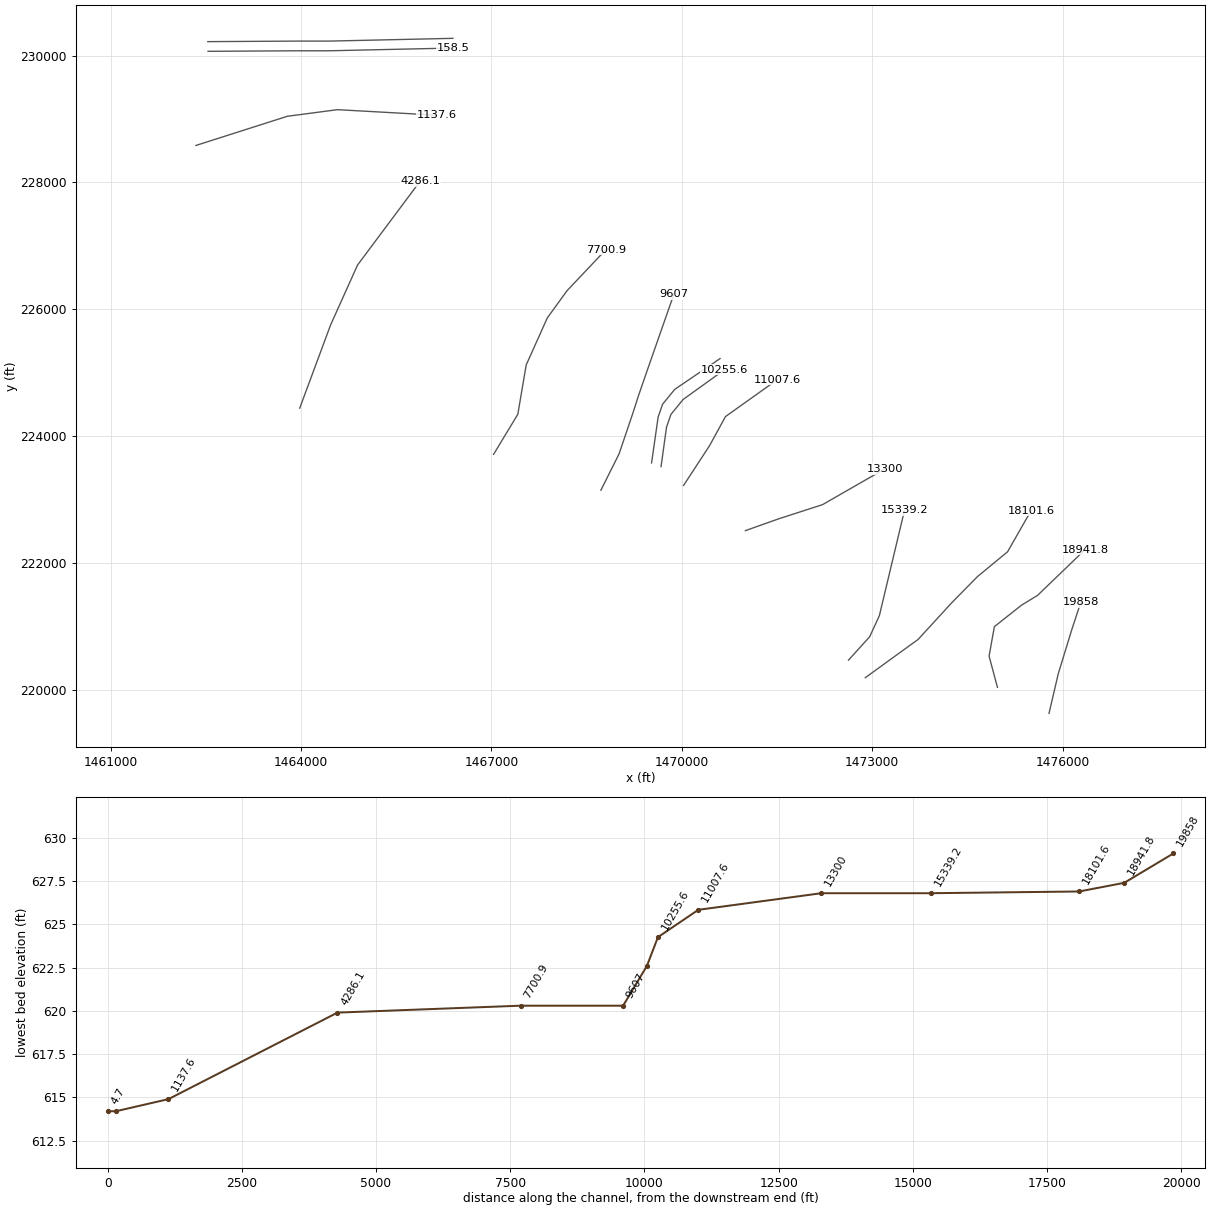
HEC-RAS study SFHGHSRV.prj: SFHGHSRV

--- SFHGHSRV.g01 (geometry) --- (continued)

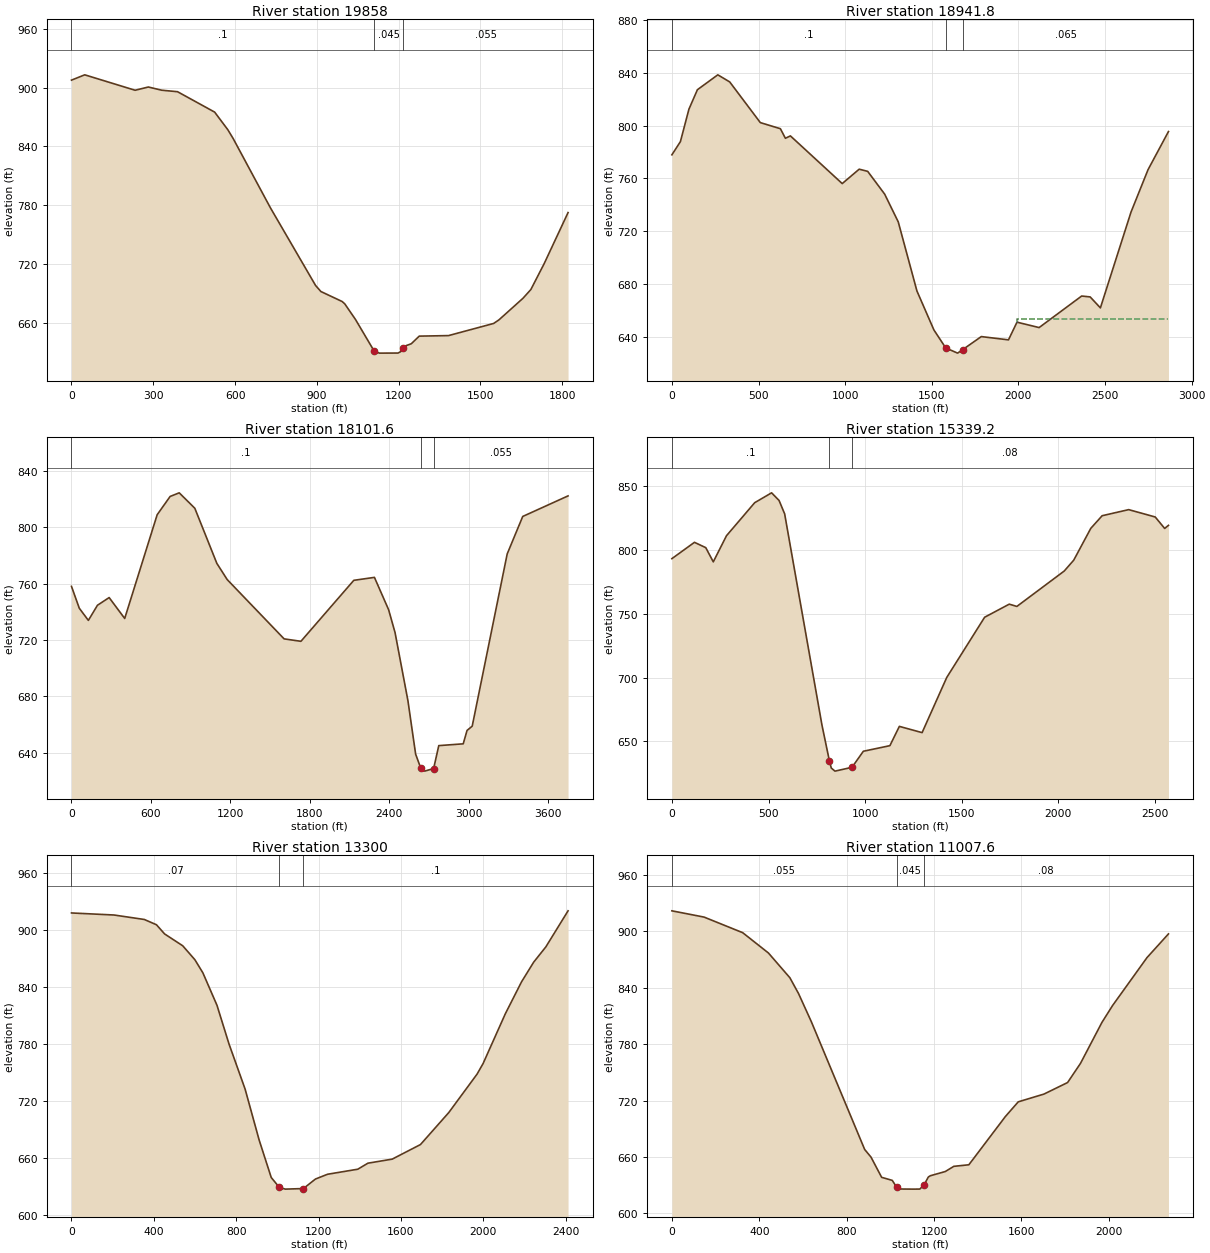
Type RM Length L Ch R = 1 ,19858   ,932.8,916.1,899.6
XS GIS Cut Line= 4
     1475787.299      219627.251     1475933.132      220252.251
     1476141.466      220932.806     1476287.299      221377.251
#Sta/Elev= 30
       0  907.58    48.6     913   233.4  897.26     282  900.57   330.6  897.31
     389  895.77   525.1  874.96   573.7  856.88   593.2  847.89   729.5   777.4
   895.3   698.1   914.8  691.94   992.8  681.74  1002.5   679.3  1041.5  663.49
  1109.8  631.38  1129.3   629.1  1197.5  629.18  1207.3  630.55    1217  634.11
  1226.8  636.68  1246.3  638.67  1275.5  646.44  1382.8  646.98  1548.4  659.37
  1567.9  663.06  1655.6  684.95  1684.8  693.95  1733.6  720.34  1821.3  772.48
#Mann= 3 , 0 , 0
       0      .1       0  1109.8    .045       0    1217    .055       0
Bank Sta=1109.8,1217
XS Rating Curve= 0 ,0
Exp/Cntr=0.3,0.1

Type RM Length L Ch R = 1 ,18941.8 ,836.9,840.2,843.1
XS GIS Cut Line= 6
     1474974.799      220036.973     1474842.855      220530.028
     1474926.188      220995.306     1475356.743      221335.584
     1475606.743      221488.362     1476356.743      222210.584
#Sta/Elev= 30
       0  777.97    49.1  787.97    98.2  812.58   147.2  827.38     265  838.69
   333.7   833.3   510.4  802.41   626.2  797.78   655.1  790.51     684  792.33
   983.1  756.12  1081.1  767.06  1130.1   765.4  1228.1  748.11  1306.5  727.04
  1414.3  674.58  1512.3     645  1580.7  631.32  1649.1   627.4  1678.4  630.06
  1785.8  639.96  1942.7  637.47  1991.8   650.9  2119.5   646.8  2365.1  670.75
  2414.2  670.07  2473.2  661.76    2650   734.5  2748.2  766.67  2866.1  795.63
#Mann= 3 , 0 , 0
       0      .1       0  1580.7    .045       0  1678.4    .065       0
#XS Ineff= 2 , 0
                         1990.78          653.54
Permanent Ineff=
       F       F
Bank Sta=1580.7,1678.4
XS Rating Curve= 0 ,0
Exp/Cntr=0.3,0.1

Type RM Length L Ch R = 1 ,18101.6 ,2750.7,2762.5,2778.7
XS GIS Cut Line= 6
     1472891.466      220189.751     1473724.799      220793.917
     1474252.577      221370.306     1474662.299      221786.973
     1475134.521      222175.862     1475502.577      222821.695
#Sta/Elev= 30
       0  758.04    58.8  742.54   127.4  733.89   196.1  744.62   284.3  750.09
   401.9  735.25     647  808.86     745  821.86   813.6  824.43   931.3   813.5
  1097.7  774.37  1175.8  762.88  1605.7  720.78  1732.7  719.03  2132.2  762.33
    2288  764.42  2395.2  741.44  2443.7  725.22  2540.8  676.97  2599.1  638.97
  2637.9  628.97  2667.1   626.9    2735  628.72  2773.9  645.01  2958.4  646.27
  2987.5  655.78  3026.5  658.83  3290.6  781.04    3408  807.66  3750.3  822.25
#Mann= 3 , 0 , 0
       0      .1       0  2637.9    .045       0    2735    .055       0
Bank Sta=2637.9,2735
XS Rating Curve= 0 ,0
Exp/Cntr=0.3,0.1

Type RM Length L Ch R = 1 ,15339.2 ,2058.7,2039.1,2013.7
XS GIS Cut Line= 4
     1472627.577      220467.528      1472960.91      220835.584
     1473113.688      221168.917     1473509.521       222828.64
#Sta/Elev= 30
       0  792.97   116.8  805.73   175.3  801.55   214.2  790.46   282.4  810.87
   428.4  836.72   515.9  844.44   554.5  838.48   583.4  828.01   776.4  662.89
     815  634.84   824.6  629.23   843.9   626.8   931.9  629.78   990.7  642.34
    1128  646.71    1177  661.79  1294.7  656.91  1422.2  700.04  1618.3  747.15
  1745.8  757.38    1785  755.59  2030.2  783.29  2079.2  791.75  2167.5  816.63
  2226.3  826.53  2363.6   831.3  2500.9  825.55  2549.9  816.58  2569.5     819
#Mann= 3 , 0 , 0
       0      .1       0     815    .045       0   931.9     .08       0
Bank Sta=815,931.9
XS Rating Curve= 0 ,0
Exp/Cntr=0.3,0.1

Type RM Length L Ch R = 1 ,13300   ,2274.7,2292.5,2309.5
XS GIS Cut Line= 4
     1471002.577      222509.195     1471530.355      222696.695
     1472217.855      222918.917     1473197.021      223481.417
#Sta/Elev= 30
       0  918.07   206.4  915.91   353.7   911.2   412.7  905.64     452  895.99
   540.4  883.43   599.2  868.79   638.2  854.91   706.6  820.71   765.1  779.86
   843.2  732.34   911.6  678.47   970.2  639.04  1009.2  628.71  1038.5   626.8
  1126.4   627.4    1185  637.45  1243.6  642.48  1390.6  647.81  1439.7  654.16
  1557.6  658.43    1695  673.82  1832.5  707.56    1970  748.15  1999.4  759.39
  2107.4  811.86    2186  845.47  2244.9  866.21  2303.8  882.25  2411.8  920.32
#Mann= 3 , 0 , 0
       0     .07       0  1009.2    .045       0  1126.4      .1       0
Bank Sta=1009.2,1126.4
XS Rating Curve= 0 ,0
Exp/Cntr=0.3,0.1

Type RM Length L Ch R = 1 ,11007.6 ,756,752,748
XS GIS Cut Line= 4
     1470028.618      223222.737     1470436.605      223847.737
     1470688.341      224307.806     1471504.313      224889.403
#Sta/Elev= 30
       0  921.94   147.3  915.27   324.1  898.68   441.9  877.06   540.1   850.7
   579.4  834.04   638.4  803.89   882.3  668.05   911.5  659.84     960   638.4
  1008.6  635.15    1028  628.17  1037.7  625.98  1105.7  625.84  1134.8  625.91
  1154.3  630.38  1173.7  638.74  1183.4  640.11  1251.4  644.58  1290.5   650.1
  1359.2  651.74  1526.2  703.03  1585.2   718.7  1703.1  726.98  1811.1  739.24
  1870.1  759.62  1968.3  803.23  2017.4  821.31  2174.6  872.19  2272.8  897.39
#Mann= 3 , 0 , 0
       0    .055       0    1028    .045       0  1154.3     .08       0
Bank Sta=1028,1154.3
XS Rating Curve= 0 ,0
Exp/Cntr=0.3,0.1

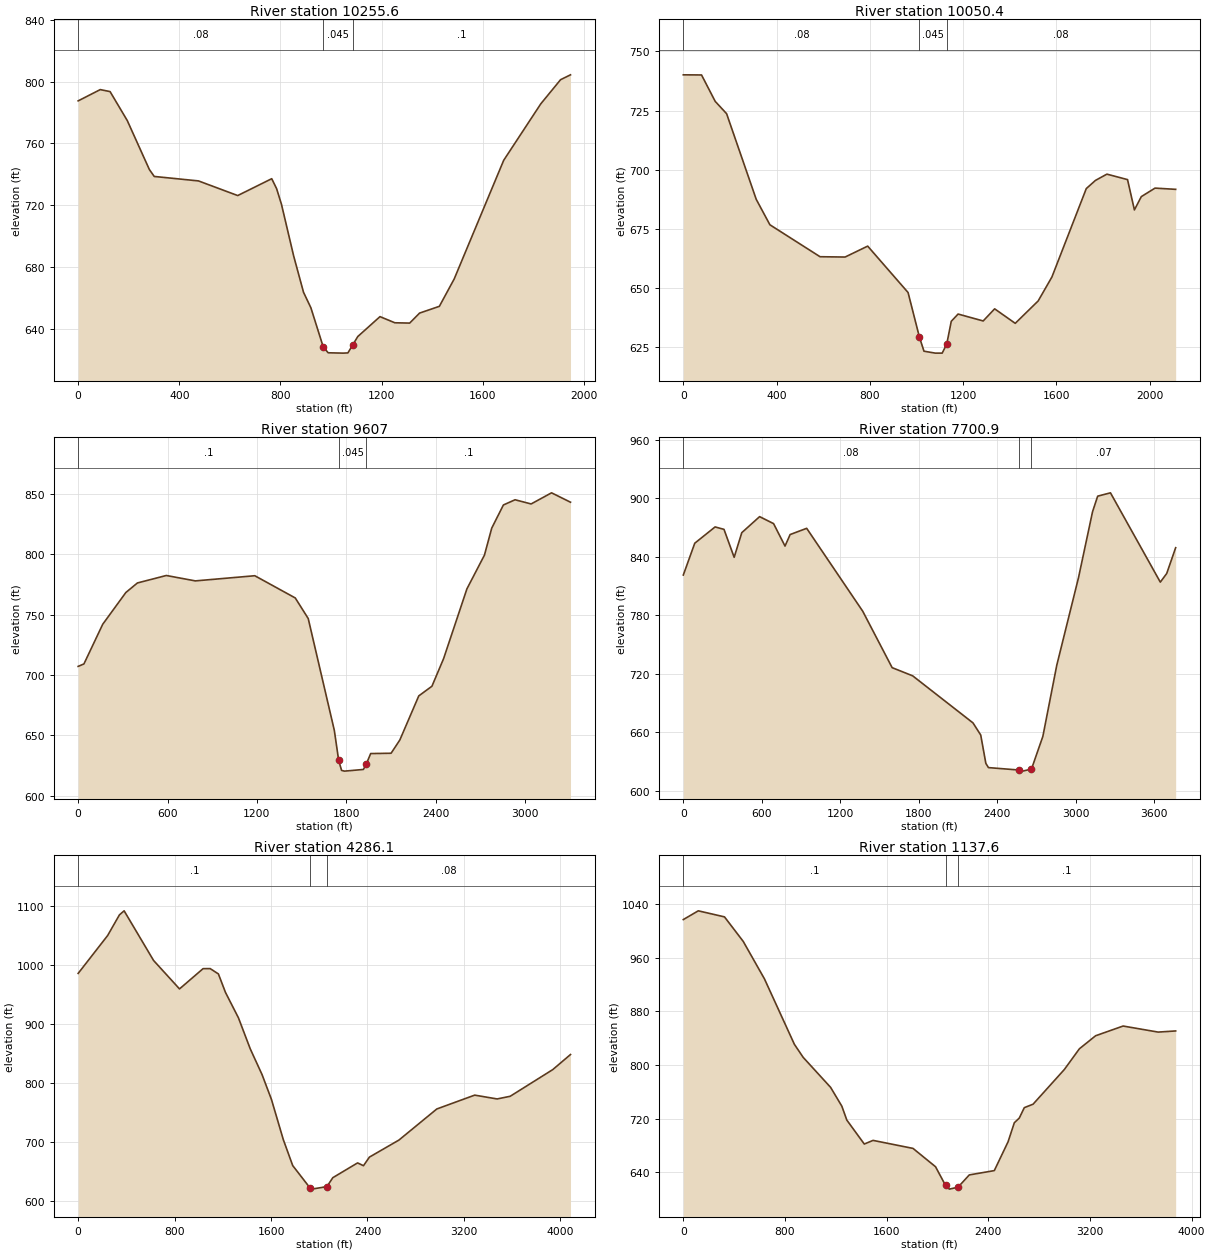
Type RM Length L Ch R = 1 ,10255.6 ,205.4,205.2,205
XS GIS Cut Line= 5
     1469672.716      223517.876     1469759.521      224142.876
     1469828.966      224342.528     1470019.938      224576.903
      1470670.98      225045.653
#Sta/Elev= 30
       0   787.5    87.4   794.8   126.2  793.51   194.2  774.78   281.5  743.11
   300.9  738.59   475.7  735.71     631  726.23   765.5  737.14   784.7  730.73
     804  720.58   852.1  687.22   891.2  663.64   920.4  653.58   969.2  628.26
   988.7  624.48  1047.2  624.26  1066.7   624.4  1086.2  629.64  1105.7  634.98
  1193.6  647.88  1252.3   643.9    1311   643.7  1350.2  650.17  1428.4  654.54
  1487.1  672.27  1682.8  749.04  1829.6  785.61  1907.8  801.22    1947  804.36
#Mann= 3 , 0 , 0
       0     .08       0   969.2    .045       0  1086.2      .1       0
Bank Sta=969.2,1086.2
XS Rating Curve= 0 ,0
Exp/Cntr=0.3,0.1

Type RM Length L Ch R = 1 ,10050.4 ,435.3,443.4,451.6
XS GIS Cut Line= 5
      1469523.41      223576.903     1469627.577      224302.598
     1469697.021      224502.251     1469887.993      224736.626
     1470603.271      225222.737
#Sta/Elev= 30
       0   740.1    78.2  740.04   136.8  728.89   185.7  723.69   312.8  687.52
   371.4  676.79   586.5   663.3     694  663.17   790.8  667.78     964  648.19
  1012.8  629.32  1032.3  623.41    1081   622.6  1110.3   622.6  1129.8  626.38
  1149.3  636.04  1178.6   639.1  1286.2  636.18  1335.3   641.3  1423.7  635.18
    1522  644.63    1581  654.75  1728.4  692.07  1767.7  695.52  1816.8  698.17
  1905.3  695.86  1934.8  683.06  1964.3  688.67  2023.2  692.27  2111.7  691.75
#Mann= 3 , 0 , 0
       0     .08       0  1012.8    .045       0  1129.8     .08       0
Bank Sta=1012.8,1129.8
XS Rating Curve= 0 ,0
Exp/Cntr=0.3,0.1

Type RM Length L Ch R = 1 ,9607    ,1912.6,1906.1,1899.3
XS GIS Cut Line= 6
     1468724.799      223146.348     1469011.257      223719.265
     1469230.007      224365.098     1469318.549       224641.14
     1469459.174       225047.39     1469875.841      226240.098
#Sta/Elev= 30
       0  707.15    38.8  709.19     165  742.09   320.3  768.43   397.9  776.34
     592  782.53   786.7  778.05    1186  782.33  1457.7   763.9  1544.7  746.83
  1719.8  654.18  1749.1  629.23  1768.6   620.9  1788.2   620.3  1915.2  621.68
  1934.7  626.23    1964  634.87    2101  635.12  2159.7   646.1    2287   682.7
  2375.2  690.69  2453.6  713.59  2610.2  771.46  2727.8  799.42  2776.7  821.78
  2855.1  841.01  2933.4  845.33  3041.2  841.85  3178.3  851.08  3305.6   843.3
#Mann= 3 , 0 , 0
       0      .1       0  1749.1    .045       0  1934.7      .1       0
Bank Sta=1749.1,1934.7
XS Rating Curve= 0 ,0
Exp/Cntr=0.3,0.1

Type RM Length L Ch R = 1 ,7700.9  ,3410,3414.7,3418.6
XS GIS Cut Line= 6
     1467033.827       223712.32     1467415.771      224344.265
     1467547.716      225122.042     1467881.049      225865.098
     1468193.549      226295.653      1468804.66      226941.487
#Sta/Elev= 30
       0  821.33    87.4  853.93   242.9  870.65   310.9  868.16   388.6  839.51
   446.9  864.75     583  881.19   689.8  874.04   777.4  851.02   816.3  862.84
   942.9  869.22  1371.5  784.17    1596  726.38    1753  717.99  2214.1  669.72
    2273  657.31  2312.2   628.3  2331.9  623.91  2564.2  621.44  2593.2   620.3
  2660.9  622.38    2748  655.98  2854.4  728.95  3020.3  818.62  3127.7  886.27
  3166.8  902.19  3264.5  905.61  3645.6  814.04  3694.4   822.9  3762.8  849.34
#Mann= 3 , 0 , 0
       0     .08       0  2564.2    .045       0  2660.9     .07       0
Bank Sta=2564.2,2660.9
XS Rating Curve= 0 ,0
Exp/Cntr=0.3,0.1

Type RM Length L Ch R = 1 ,4286.1  ,3179.6,3148.6,3141.7
XS GIS Cut Line= 4
     1463978.488      224441.161     1464464.599      225751.925
     1464889.947      226698.106     1465875.841      228019.612
#Sta/Elev= 30
       0  985.46   244.4 1049.59   342.2 1084.62   381.3 1091.52   625.7 1007.37
   840.8  959.18  1036.3  993.52  1094.9  993.63  1163.4  984.58    1222  953.28
  1329.6  910.19  1427.4  857.69  1525.2  814.11  1603.5  771.88  1701.4  704.02
  1779.7  659.85  1926.5  621.09  1936.3   619.9  2063.5  624.13  2112.4  639.29
    2318  664.34  2366.9  659.58  2415.8  674.12  2661.1  703.07  2975.2  755.74
  3289.2  779.18  3475.7  772.73  3583.6  777.22  3936.9  822.44  4084.1  847.99
#Mann= 3 , 0 , 0
       0      .1       0  1926.5    .045       0  2063.5     .08       0
Bank Sta=1926.5,2063.5
XS Rating Curve= 0 ,0
Exp/Cntr=0.3,0.1

Type RM Length L Ch R = 1 ,1137.6  ,981.2,979.1,975.3
XS GIS Cut Line= 4
     1462342.855      228583.848     1463783.827      229043.917
     1464573.757      229148.084     1466136.257      229061.278
#Sta/Elev= 30
       0 1016.96   117.9 1030.01   324.1 1020.98   471.5   984.4   638.4  928.55
   874.2  830.86   942.9  811.54    1159  766.72  1247.4  738.66  1286.7  717.86
  1424.2  682.14    1493   687.6  1807.7  675.63  1984.8  648.29  2063.5  620.42
    2093   614.9  2161.8   617.8  2250.4  636.09  2447.2  642.52  2555.5  685.49
  2604.7  713.88    2644  720.98  2683.4  736.44  2752.3  741.58  2998.4  793.33
  3116.5  824.16  3244.4  843.67  3460.9  858.17  3736.5  849.13  3874.3  850.83
#Mann= 3 , 0 , 0
       0      .1       0  2063.5    .045       0  2161.8      .1       0
Bank Sta=2063.5,2161.8
XS Rating Curve= 0 ,0
Exp/Cntr=0.3,0.1

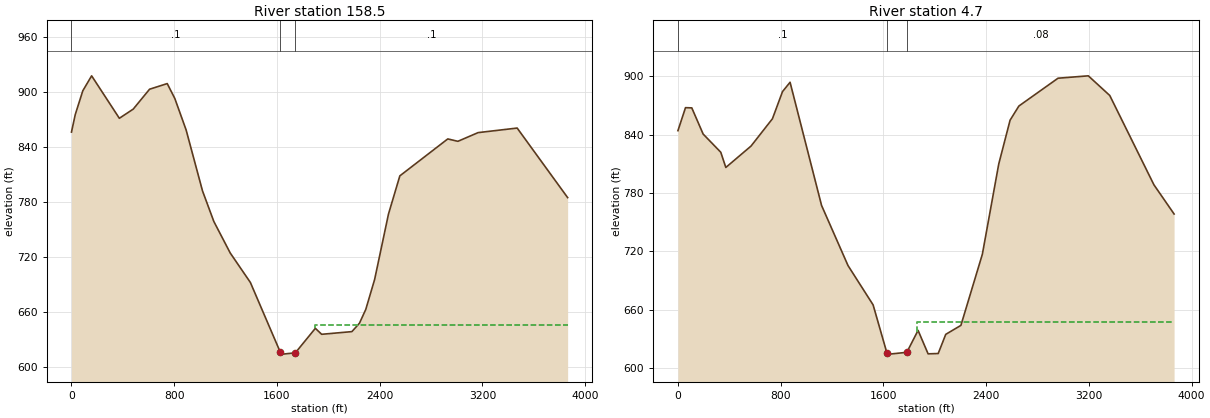
Type RM Length L Ch R = 1 ,158.5   ,153.6,153.8,153.6
XS GIS Cut Line= 4
     1462533.827      230068.223     1463966.118      230076.903
      1464452.23      230076.903     1466396.674      230120.306
#Sta/Elev= 30
       0  856.44    29.4  875.52    88.3  901.52     157  917.82   372.8   871.5
   480.7  881.49   608.2  903.22   745.6  909.35   804.4  893.22   892.8  858.74
  1020.3   792.3  1108.6  758.91  1236.1  724.56  1393.1  692.38  1626.8  616.07
  1646.2   614.2  1743.4  615.63    1899  642.35  1947.9  635.83  2183.6  638.76
  2242.6  647.96  2291.7  663.01  2360.5  695.62  2468.5  767.06  2556.9  808.68
  2930.2  848.99  3008.8  846.37  3165.9  855.85  3470.4  860.84  3863.4  784.98
#Mann= 3 , 0 , 0
       0      .1       0  1626.8    .045       0  1743.4      .1       0
#XS Ineff= 2 , 0
                         1898.02          645.69
Permanent Ineff=
       F       F
Bank Sta=1626.8,1743.4
XS Rating Curve= 0 ,0
Exp/Cntr=0.3,0.1

Type RM Length L Ch R = 1 ,4.7     ,3.1,4.7,6.3
XS GIS Cut Line= 4
     1462530.355      230221.001     1463962.646      230229.681
     1464448.757      230229.681     1466393.202      230273.084
#Sta/Elev= 30
       0  844.15    58.9  867.81   107.9  867.58   196.2  840.67   333.6  821.93
   372.8  806.27     569  828.28   735.8  856.38   814.3  884.35   873.1  893.96
  1118.4  767.19  1324.4   705.3  1519.8  664.86  1626.8  615.55  1646.2   614.2
  1782.3  616.06  1869.8  638.64  1947.9   614.5  2026.5  614.82  2085.4  634.55
  2203.3  643.78  2370.3  716.93    2498  809.83  2586.4  854.96  2655.1  869.53
  2959.6  898.11  3195.4  900.57  3362.4  880.34  3706.2  788.46  3863.4  758.38
#Mann= 3 , 0 , 0
       0      .1       0  1626.8    .045       0  1782.3     .08       0
#XS Ineff= 2 , 0
                         1863.96          647.74
Permanent Ineff=
       F       F
Bank Sta=1626.8,1782.3
XS Rating Curve= 0 ,0
Exp/Cntr=0.3,0.1

Chan Stop Cuts=-1
Use User Specified Reach Order=0
Composite Channel Slope=5